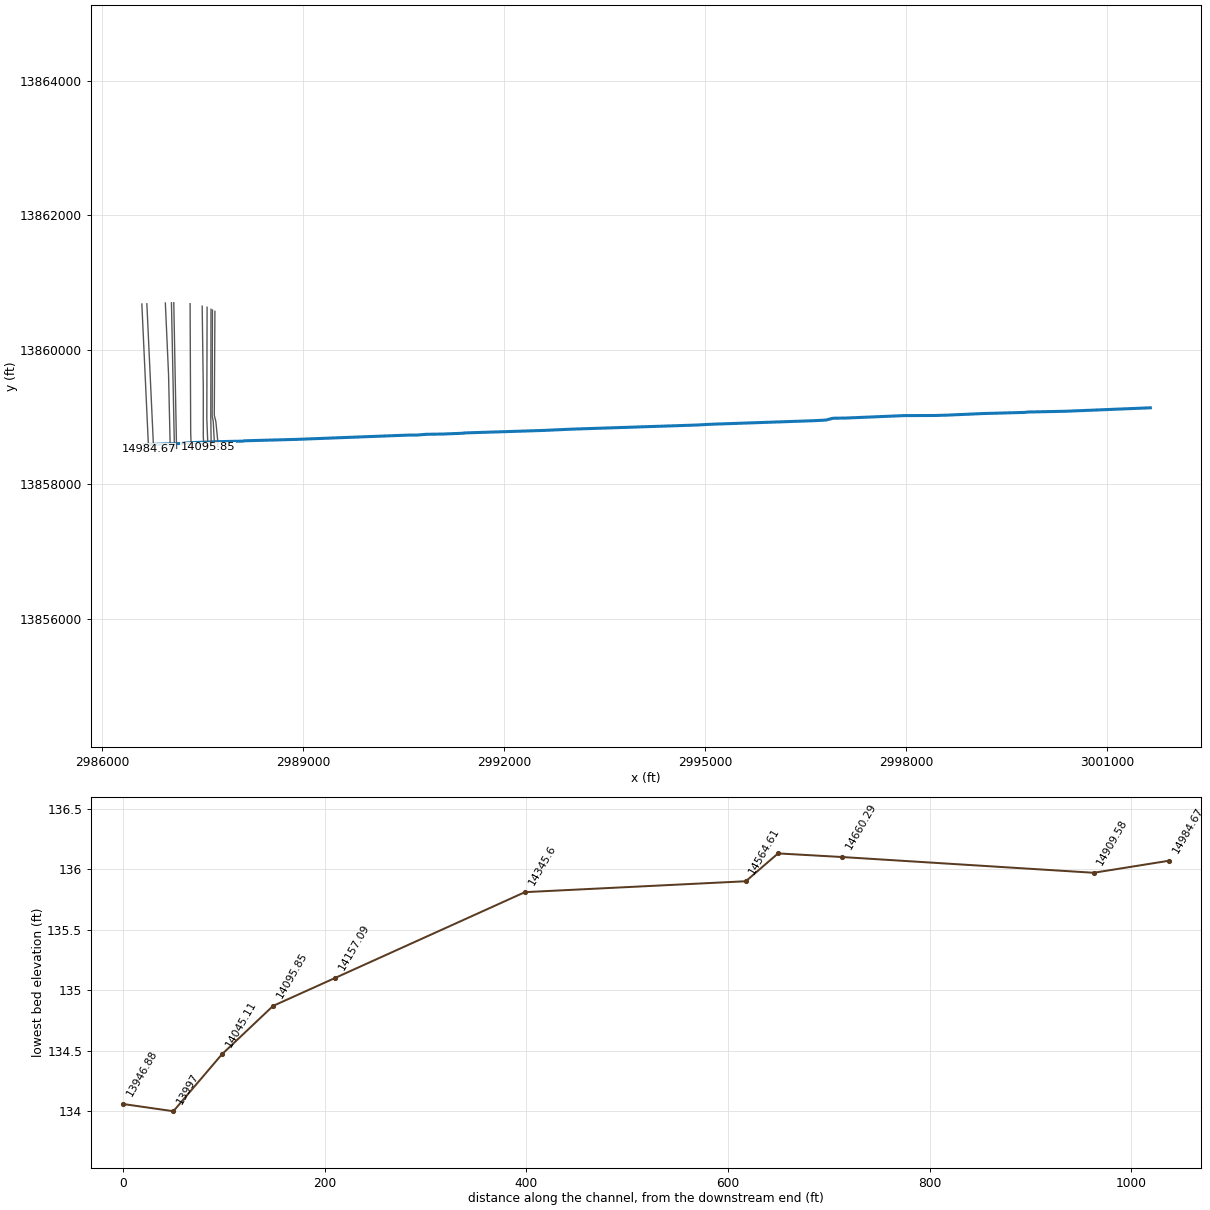
--- U101-07-00.prj (project) ---

Proj Title=U101-07-00 2019 (Re-Study)
Current Plan=p01
Default Exp/Contr=0.3,0.1
English Units
Geom File=g01
Flow File=f01
Flow File=f02
Flow File=f03
Plan File=p01
Plan File=p02
Plan File=p03
Y Axis Title=Elevation
X Axis Title(PF)=Main Channel Distance
X Axis Title(XS)=Station
BEGIN DESCRIPTION:
Tributary 9.4 to South Mayde Creek (U101-07-00)
(Flood Hazard & Floodway) Model
10-, 2-, 1-, and 0.2% Events
FILENAME: U101_07_00.prj
PREPARED BY:  LAN                               DATE: 06/26/2012
REVIEWED BY: GA                                  DATE: 06/12/2012
STATUS: 2nd (FW)
ADDICKS WATERSHED MODEL UPDATE
HARRIS COUNTY, TEXAS
END DESCRIPTION:
DSS Export Rating Curves= 0
DSS Export Rating Curve Sorted= 0
DSS Export Volume Flow Curves= 0
DXF OffsetX= 0
DXF OffsetY= 0
DXF ScaleX= 1
DXF ScaleY= 10

--- U101-07-00.p01 (plan) ---

Plan Title=Effective Multi-Profile 2019 (Re-Study)
Program Version=4.10
Short Identifier=Eff+ReStudy+MP
Geom File=g01
Flow File=f01
Subcritical Flow
K Sum by GR= 0
Std Step Tol= 0.01
Critical Tol= 0.01
Num of Std Step Trials= 20
Max Error Tol= 0.3
Flow Tol Ratio= 0.001
Split Flow NTrial= 30
Split Flow Tol= 0.02
Split Flow Ratio= 0.02
Log Output Level= 0
Friction Slope Method= 1
Unsteady Friction Slope Method= 2
Unsteady Bridges Friction Slope Method= 1
Parabolic Critical Depth
Global Vel Dist= 0 , 0 , 0
Global Log Level= 0
CheckData=True
Encroach Param=-1 ,0,0, 0
Computation Interval=1HOUR
Output Interval=1HOUR
Run HTab= 0
Run UNet= 0
Run PostProcess= 0
Run WQNet= 0
UNET Theta= 1
UNET Theta Warmup= 1
UNET ZTol= 0.02
UNET ZSATol= 0.05
UNET MxIter= 20
UNET MaxInSteps= 0
UNET DtIC= 0
UNET DtMin= 0
UNET MaxCRTS= 20
UNET WFStab= 2
UNET SFStab= 1
UNET WFX= 1
UNET SFX= 1
UNET DSS MLevel= 4
UNET DZMax Abort= 100
UNET Convert EG Bridges= 0
UNET Use Existing IB Tables=-1
UNET Froude Reduction=False
UNET Froude Limit= 1
UNET Froude Power= 10
UNET Time Slicing=0,0, 5
UNET Junction Losses=0
Instantaneous Interval=1HOUR
Write IC File= 0
Write IC File at Sim End=0
Echo Input=False
Echo Parameters=False
Echo Output=False
Write Detailed= 0
WQ AD Non Conservative
WQ ULTIMATE=-1
WQ Max Comp Step=1HOUR
WQ Output Interval=15MIN
WQ Output Selected Increments= 0
WQ Output face flow=0
WQ Output face velocity=0
WQ Output face area=0
WQ Output face dispersion=0
WQ Output cell volume=0
WQ Output cell surface area=0
WQ Output cell continuity=0
WQ Output cumulative cell continuity=0
WQ Output face conc=0
WQ Output face dconc_dx=0
WQ Output face courant=0
WQ Output face peclet=0
WQ Output face adv mass=0
WQ Output face disp mass=0
WQ Output cell mass=0
WQ Output cell source sink temp=0
WQ Output cell source sink nsm=0
WQ Output MaxMinRange=-1
WQ Daily Max Min Mean=-1
WQ Daily Range=0
WQ Daily Time=0
WQ Create Restart=0
WQ Fixed Restart=0
WQ System Summary=0
WQ Use Fixed Temperature=0
Sorting and Armoring Iterations= 10
XS Update Threshold= 0.02
Hydraulics Update Threshold= 0.02
Energy Slope Method= 1
Volume Change Method= 0
XS Weighting Method= 0
Number of US Weighted Cross Sections= 1
Number of DS Weighted Cross Sections= 1
Upstream XS Weight=0.25
Main XS Weight=0.5
Downstream XS Weight=0.25
Number of DS XS's Weighted with US Boundary= 1
Upstream Boundary Weight= 1
Weight of XSs Associated with US Boundary= 0
Number of US XS's Weighted with DS Boundary= 1
Downstream Boundary Weight= 0.5
Weight of XSs Associated with DS Boundary= 0.5
Sediment Output Level= 4
Mass or Volume Output= 0
Output Increment Type= 1
Profile and TS Output Increment= 10
XS Output Flag= 0
XS Output Increment= 10
Disregard all LS=0
Disregard all Conn=0
Disregard all Breaches=0
Disregard all Pumps=0

--- U101-07-00.p02 (plan) ---

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Plan Title=Effective Floodway 2019 (FW)
Short Identifier=Eff+ReStudy+FW
Geom File=g01
Flow File=f02
Encroach Param=-1 ,0,0, 2
Encroach River=U101-07-00
Encroach Reach=U101-07-00_0001
Encroach Node=14984.67
       1  2074.4 2114.35
Encroach Node=14909.58
       1 2079.39 2119.34
Encroach Node=14660.29
       1 2075.41 2122.39
Encroach Node=14596.61
       1 2087.84 2106.17
Encroach Node=14564.61
       1 2077.24  2115.7
Encroach Node=14345.6
       1 2049.81 2099.13
Encroach Node=14157.09
       1 2009.41 2054.08
Encroach Node=14095.85
       1 1992.57 2036.46
Encroach Node=14045.11
       1 1959.65 2003.06
Encroach Node=13997
       1 1949.01 1988.51
Encroach Node=13946.88
       1 1925.98 1965.94
Encroach Node=13910.27
       1 1897.52 1946.98
Encroach Node=13784.01
       1 1895.04  1944.5
Encroach Node=13749.12
       1 1871.47 1909.51
Encroach Node=13699.69
       1 1859.84  1898.8
Encroach Node=13648.78
       1 1846.09 1893.32
Encroach Node=13599.75
       1 1836.13 1880.96
Encroach Node=12903.38
       1 1590.62 1625.65
Encroach Node=12825.57
       1 1595.98 1634.22
Encroach Node=12795.55
       1 1600.41 1634.22
Encroach Node=12678.13
       1 1588.48 1619.22
Encroach Node=12461.48
       1 1438.23 1466.79
Encroach Node=12418.11
       1 1434.13 1473.72
Encroach Node=12393.27
       1 1432.08 1473.72
Encroach Node=12333.3
       1 1371.32    1415
Encroach Node=12191.24
       1 1373.25    1415
Encroach Node=12143.35
       1 1432.02 1473.72
Encroach Node=12117.91
       1  1429.6 1468.76
Encroach Node=12065.24
       1  1426.4 1468.76
Encroach Node=11200.33
       1 2018.14 2083.99
Encroach Node=10701.13
       1 2294.73 2354.27
Encroach Node=10347.76
       1 2298.01 2397.47
Encroach Node=10297.19
       1 2310.07 2397.75
Encroach Node=10246.85
       1 2317.42 2411.06
Encroach Node=10196.72
       1 2333.87 2449.67
Encroach Node=10150.29
       1 2395.01 2460.01
Encroach Node=10099.74
       1 2390.01 2455.01
Encroach Node=10046.98
       1 2417.74  2449.1
Encroach Node=10003.84
       1    2313 2414.61
Encroach Node=9954.988
       1 2300.94 2423.72
Encroach Node=9900.212
       1 2296.85 2417.71
Encroach Node=9392.124
       1 2533.83 2606.58
Encroach Node=9085.937
       1  105.58  180.34
Encroach Node=9017.523
       1    48.8   97.48
Encroach Node=8992.246
       1   36.21   85.83
Encroach Node=8955.833
       1       0   46.39
Encroach Node=8945.833
       1       0   46.39
Encroach Node=8928.141
       1    1.18   43.07
Encroach Node=8905.655
       1    5.63   48.93
Encroach Node=8868.345
       1   10.74    57.8
Encroach Node=8819.565
       1     7.7   56.59
Encroach Node=8229.257
       1    4.77   51.92
Encroach Node=7668.068
       1   20.35   69.11
Encroach Node=7302.581
       1   29.12    72.8
Encroach Node=7239.441
       1  543.12  592.95
Encroach Node=6995.219
       1  626.29  675.66
Encroach Node=6943.219
       1  577.94  632.07
Encroach Node=6894.923
       1  570.15  622.79
Encroach Node=6844.391
       1  558.89  602.31
Encroach Node=6822.419
       1  551.05  606.98
Encroach Node=6677.314
       1  544.81  600.74
Encroach Node=6645.719
       1  457.04  512.25
Encroach Node=6596.198
       1  350.72  404.33
Encroach Node=6546.031
       1  322.66  378.71
Encroach Node=6497.662
       1  314.01  368.02
Encroach Node=5743.321
       1  170.02  209.34
Encroach Node=5638.31
       1   24.47   78.32
Encroach Node=5333.757
       1   19.89   79.55
Encroach Node=5322.362
       1   24.02   74.58
Encroach Node=5211.394
       1   29.89   89.67
Encroach Node=5196.791
       1   29.89   89.67
Encroach Node=4974.61
       1 1421.49 1470.68
Encroach Node=4907.297
       1 1380.13 1475.99
Encroach Node=4704.912
       1 1390.14    1486
Encroach Node=4419.56
       1  1351.2 1436.52
Encroach Node=3680.687
       1 1777.06 1871.04
Encroach Node=3515.556
       1 1972.77 2052.11
Encroach Node=3295.503
       1 1979.96 2052.11
Encroach Node=3093.946
       1   84.85  174.29
Encroach Node=2350.281
       1   37.12  115.03
Encroach Node=1688.528
       1   39.32  115.32
Encroach Node=1123.231
       1    27.6     113
Encroach Node=1118.2
       1   27.55     113
Encroach Node=1098.213
       1   27.79     113
Encroach Node=1093.222
       1      28     113
Encroach Node=1073.229
       1   28.37     113
Encroach Node=1068.218
       1    29.1     113
Encroach Node=870.9581
       1   34.75  114.19
Encroach Node=864.3873
       1   34.75  113.86
Encroach Node=843.7701
       1   29.33  112.43
Encroach Node=838.4837
       1   29.63   113.6
Encroach Node=821.0098
       1   29.88  114.55
Encroach Node=815.2426
       1   29.23  112.06
Encroach Node=468.3679
       1   57.97   135.4
Encroach Node=320.0495
       1    74.5  149.01
Encroach Node=218.8394
       1  134.96   219.2
Encroach Node=210.4193
       1     125  224.15
Encroach Node=163.4989
       1     125  224.15
Encroach Node=114.7056
       1    4.96   99.23

--- U101-07-00.p03 (plan) ---

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Plan Title=Storage Routing (SV-SQ)
Short Identifier=SV-SQ
Geom File=g01
Flow File=f03

--- U101-07-00.f01 (steady flow) ---

Flow Title=Effective Multi-Profile 2019 (Re-Study)
Program Version=4.10
Number of Profiles= 4
Profile Names=10YR,50YR,100YR,500YR
River Rch & RM=U101-07-00,U101-07-00_0001 ,14984.67
       2       5      25      47
River Rch & RM=U101-07-00,U101-07-00_0001 ,14345.6
       3       7      31      56
River Rch & RM=U101-07-00,U101-07-00_0001 ,13648.78
       4      11      38      68
River Rch & RM=U101-07-00,U101-07-00_0001 ,12903.38
       6      15      44      77
River Rch & RM=U101-07-00,U101-07-00_0001 ,12418.11
       8      18      49      84
River Rch & RM=U101-07-00,U101-07-00_0001 ,12065.24
      14      30      64     104
River Rch & RM=U101-07-00,U101-07-00_0001 ,11200.33
      20      40      74     118
River Rch & RM=U101-07-00,U101-07-00_0001 ,10701.13
      26      49      83     129
River Rch & RM=U101-07-00,U101-07-00_0001 ,10347.76
      36      63      95     144
River Rch & RM=U101-07-00,U101-07-00_0001 ,9900.212
      51      84     110     164
River Rch & RM=U101-07-00,U101-07-00_0001 ,9392.124
      66     104     123     180
River Rch & RM=U101-07-00,U101-07-00_0001 ,9017.523
      68     106     124     181
River Rch & RM=U101-07-00,U101-07-00_0001 ,8992.246
      53      53      53      52
River Rch & RM=U101-07-00,U101-07-00_0001 ,8955.833
      58      65      68      71
River Rch & RM=U101-07-00,U101-07-00_0001 ,8229.257
      66      86      96     108
River Rch & RM=U101-07-00,U101-07-00_0001 ,7239.441
      74     107     124     148
River Rch & RM=U101-07-00,U101-07-00_0001 ,6497.662
      82     133     161     204
River Rch & RM=U101-07-00,U101-07-00_0001 ,5743.321
      86     149     186     243
River Rch & RM=U101-07-00,U101-07-00_0001 ,5333.757
      86     150     187     244
River Rch & RM=U101-07-00,U101-07-00_0001 ,5322.362
      86     150     187     244
River Rch & RM=U101-07-00,U101-07-00_0001 ,5211.394
      87     150     187     245
River Rch & RM=U101-07-00,U101-07-00_0001 ,4974.61
      92     156     192     256
River Rch & RM=U101-07-00,U101-07-00_0001 ,4907.297
     103     167     201     276
River Rch & RM=U101-07-00,U101-07-00_0001 ,4419.56
     126     190     219     317
River Rch & RM=U101-07-00,U101-07-00_0001 ,3515.556
       2      66      95     193
River Rch & RM=U101-07-00,U101-07-00_0001 ,3295.503
       2      67      97     196
River Rch & RM=U101-07-00,U101-07-00_0001 ,3093.946
       4      73     105     210
River Rch & RM=U101-07-00,U101-07-00_0001 ,2350.281
       8      79     112     222
River Rch & RM=U101-07-00,U101-07-00_0001 ,1688.528
      13      85     119     234
River Rch & RM=U101-07-00,U101-07-00_0001 ,1093.222
      24      91     127     247
River Rch & RM=U101-07-00,U101-07-00_0001 ,468.3679
      33      95     132     255
Boundary for River Rch & Prof#=U101-07-00,U101-07-00_0001 , 1
Up Type= 0
Dn Type= 3
Dn Slope=0.0024
Boundary for River Rch & Prof#=U101-07-00,U101-07-00_0001 , 2
Up Type= 0
Dn Type= 3
Dn Slope=0.0024
Boundary for River Rch & Prof#=U101-07-00,U101-07-00_0001 , 3
Up Type= 0
Dn Type= 3
Dn Slope=0.0024
Boundary for River Rch & Prof#=U101-07-00,U101-07-00_0001 , 4
Up Type= 0
Dn Type= 3
Dn Slope=0.0024
Observed WS=U101-07-00      ,U101-07-00_0001 ,14984.67,0,140,140.64,140.86,141.08
Observed WS=U101-07-00      ,U101-07-00_0001 ,14345.6 ,0,139.66,140.43,140.66,141.02
Observed WS=U101-07-00      ,U101-07-00_0001 ,14157.09,0,139.56,140.33,140.56,140.88
Observed WS=U101-07-00      ,U101-07-00_0001 ,14095.85,0,139.46,140.02,140.21,140.55
Observed WS=U101-07-00      ,U101-07-00_0001 ,14045.11,0,139.13,139.63,139.81,139.78
Observed WS=U101-07-00      ,U101-07-00_0001 ,13997   ,0,138.76,139.24,139.43,139.7
Observed WS=U101-07-00      ,U101-07-00_0001 ,13599.75,0,138.4,138.88,139.07,139.41
Observed WS=U101-07-00      ,U101-07-00_0001 ,12903.38,0,138.14,138.65,138.84,139.2
Observed WS=U101-07-00      ,U101-07-00_0001 ,12678.13,0,137.75,138.34,138.55,139.14
Observed WS=U101-07-00      ,U101-07-00_0001 ,12461.48,0,137.75,138.34,138.55,139.13
Observed WS=U101-07-00      ,U101-07-00_0001 ,12418.11,0,137.74,138.34,138.55,139.13
Observed WS=U101-07-00      ,U101-07-00_0001 ,12393.27,0,137.66,138.25,138.47,139.05
Observed WS=U101-07-00      ,U101-07-00_0001 ,12333.3 ,0,137.38,137.98,138.19,138.76
Observed WS=U101-07-00      ,U101-07-00_0001 ,12065.24,0,137.26,137.86,138.07,138.63
Observed WS=U101-07-00      ,U101-07-00_0001 ,11200.33,0,137.13,137.75,137.96,138.53
Observed WS=U101-07-00      ,U101-07-00_0001 ,10701.13,0,136.31,136.99,137.16,137.62
Observed WS=U101-07-00      ,U101-07-00_0001 ,10347.76,0,135.99,136.68,136.81,137.17
Observed WS=U101-07-00      ,U101-07-00_0001 ,10046.98,0,135.81,136.51,136.62,136.88
Observed WS=U101-07-00      ,U101-07-00_0001 ,10003.84,0,135.77,136.46,136.56,136.78
Observed WS=U101-07-00      ,U101-07-00_0001 ,9954.988,0,135.51,135.96,136.09,136.44
Observed WS=U101-07-00      ,U101-07-00_0001 ,9900.212,0,135.39,135.87,136.03,136.45
Observed WS=U101-07-00      ,U101-07-00_0001 ,9085.937,0,134.41,135.1,135.47,136.35
Observed WS=U101-07-00      ,U101-07-00_0001 ,8819.565,0,133.25,134.25,134.86,136.3
Observed WS=U101-07-00      ,U101-07-00_0001 ,5638.31 ,0,129.5,130.67,130.88,131.88
Observed WS=U101-07-00      ,U101-07-00_0001 ,5196.791,0,129.41,130.65,130.86,131.85
Observed WS=U101-07-00      ,U101-07-00_0001 ,4974.61 ,0,129.19,130.31,130.51,131.45
Observed WS=U101-07-00      ,U101-07-00_0001 ,4907.297,0,127.88,129.31,129.56,130.76
Observed WS=U101-07-00      ,U101-07-00_0001 ,4704.912,0,126.09,127.08,127.26,127.8
Observed WS=U101-07-00      ,U101-07-00_0001 ,4419.56 ,0,124.43,125.58,125.67,126.58
Observed WS=U101-07-00      ,U101-07-00_0001 ,3680.687,0,121.8,123.69,124.1,125.98
Observed WS=U101-07-00      ,U101-07-00_0001 ,3515.556,0,121.42,123.45,123.91,125.89
Observed WS=U101-07-00      ,U101-07-00_0001 ,3295.503,0,128.27,129.49,129.72,130.38
Observed WS=U101-07-00      ,U101-07-00_0001 ,3093.946,0,127.86,129.07,129.31,129.69
Observed WS=U101-07-00      ,U101-07-00_0001 ,2350.281,0,126.53,127.72,127.98,127.72
Observed WS=U101-07-00      ,U101-07-00_0001 ,1688.528,0,124.61,125.54,125.76,125.54
Observed WS=U101-07-00      ,U101-07-00_0001 ,1123.231,0,124.57,125.48,125.71,125.48
Observed WS=U101-07-00      ,U101-07-00_0001 ,1118.2  ,0,123.91,124.57,124.76,124.57
Observed WS=U101-07-00      ,U101-07-00_0001 ,1098.213,0,123.75,124.3,124.43,124.3
Observed WS=U101-07-00      ,U101-07-00_0001 ,1093.222,0,123.63,124.2,124.36,124.2
Observed WS=U101-07-00      ,U101-07-00_0001 ,1073.229,0,122.22,123.14,123.38,123.14
Observed WS=U101-07-00      ,U101-07-00_0001 ,1068.218,0,122.21,123.13,123.37,123.13
Observed WS=U101-07-00      ,U101-07-00_0001 ,870.9581,0,121.32,121.99,122.17,121.99
Observed WS=U101-07-00      ,U101-07-00_0001 ,843.7701,0,121.09,121.72,121.89,121.72
Observed WS=U101-07-00      ,U101-07-00_0001 ,838.4837,0,120.89,121.46,121.62,121.46
Observed WS=U101-07-00      ,U101-07-00_0001 ,821.0098,0,119.23,119.86,120.03,120.5
Observed WS=U101-07-00      ,U101-07-00_0001 ,815.2426,0,119.03,119.6,119.76,120.49
Observed WS=U101-07-00      ,U101-07-00_0001 ,163.4989,0,117.74,119.07,119.44,120.27
Observed WS=U101-07-00      ,U101-07-00_0001 ,114.7056,0,117.49,118.45,119,119.58
DSS Import GetInterval= 0
DSS Import GetPeak= 0
DSS Import FillOption= 0

--- U101-07-00.f02 (steady flow) ---

Flow Title=Effective Floodway 2019 (Re-Study)
Program Version=4.10
Number of Profiles= 2
Profile Names=100YR,FW
River Rch & RM=U101-07-00,U101-07-00_0001 ,14984.67
      25      25
River Rch & RM=U101-07-00,U101-07-00_0001 ,14345.6
      31      31
River Rch & RM=U101-07-00,U101-07-00_0001 ,13648.78
      38      38
River Rch & RM=U101-07-00,U101-07-00_0001 ,12903.38
      44      44
River Rch & RM=U101-07-00,U101-07-00_0001 ,12418.11
      49      49
River Rch & RM=U101-07-00,U101-07-00_0001 ,12065.24
      64      64
River Rch & RM=U101-07-00,U101-07-00_0001 ,11200.33
      74      74
River Rch & RM=U101-07-00,U101-07-00_0001 ,10701.13
      83      83
River Rch & RM=U101-07-00,U101-07-00_0001 ,10347.76
      95      95
River Rch & RM=U101-07-00,U101-07-00_0001 ,9900.212
     110     110
River Rch & RM=U101-07-00,U101-07-00_0001 ,9392.124
     123     123
River Rch & RM=U101-07-00,U101-07-00_0001 ,9017.523
     124     124
River Rch & RM=U101-07-00,U101-07-00_0001 ,8992.246
      53      53
River Rch & RM=U101-07-00,U101-07-00_0001 ,8955.833
      68      68
River Rch & RM=U101-07-00,U101-07-00_0001 ,8229.257
      96      96
River Rch & RM=U101-07-00,U101-07-00_0001 ,7239.441
     124     124
River Rch & RM=U101-07-00,U101-07-00_0001 ,6497.662
     161     161
River Rch & RM=U101-07-00,U101-07-00_0001 ,5743.321
     186     186
River Rch & RM=U101-07-00,U101-07-00_0001 ,5333.757
     187     187
River Rch & RM=U101-07-00,U101-07-00_0001 ,5322.362
     187     187
River Rch & RM=U101-07-00,U101-07-00_0001 ,5211.394
     187     187
River Rch & RM=U101-07-00,U101-07-00_0001 ,4974.61
     192     192
River Rch & RM=U101-07-00,U101-07-00_0001 ,4907.297
     201     201
River Rch & RM=U101-07-00,U101-07-00_0001 ,4419.56
     219     219
River Rch & RM=U101-07-00,U101-07-00_0001 ,3515.556
      95      95
River Rch & RM=U101-07-00,U101-07-00_0001 ,3295.503
      97      97
River Rch & RM=U101-07-00,U101-07-00_0001 ,3093.946
     105     105
River Rch & RM=U101-07-00,U101-07-00_0001 ,2350.281
     112     112
River Rch & RM=U101-07-00,U101-07-00_0001 ,1688.528
     119     119
River Rch & RM=U101-07-00,U101-07-00_0001 ,1093.222
     127     127
River Rch & RM=U101-07-00,U101-07-00_0001 ,468.3679
     132     132
Boundary for River Rch & Prof#=U101-07-00,U101-07-00_0001 , 1
Up Type= 0
Dn Type= 3
Dn Slope=0.0024
Boundary for River Rch & Prof#=U101-07-00,U101-07-00_0001 , 2
Up Type= 0
Dn Type= 3
Dn Slope=0.0024
Observed WS=U101-07-00      ,U101-07-00_0001 ,14984.67,0,140,140.64
Observed WS=U101-07-00      ,U101-07-00_0001 ,14345.6 ,0,139.66,140.43
Observed WS=U101-07-00      ,U101-07-00_0001 ,14157.09,0,139.56,140.33
Observed WS=U101-07-00      ,U101-07-00_0001 ,14095.85,0,139.46,140.02
Observed WS=U101-07-00      ,U101-07-00_0001 ,14045.11,0,139.13,139.63
Observed WS=U101-07-00      ,U101-07-00_0001 ,13997   ,0,138.76,139.24
Observed WS=U101-07-00      ,U101-07-00_0001 ,13599.75,0,138.4,138.88
Observed WS=U101-07-00      ,U101-07-00_0001 ,12903.38,0,138.14,138.65
Observed WS=U101-07-00      ,U101-07-00_0001 ,12678.13,0,137.75,138.34
Observed WS=U101-07-00      ,U101-07-00_0001 ,12461.48,0,137.75,138.34
Observed WS=U101-07-00      ,U101-07-00_0001 ,12418.11,0,137.74,138.34
Observed WS=U101-07-00      ,U101-07-00_0001 ,12393.27,0,137.66,138.25
Observed WS=U101-07-00      ,U101-07-00_0001 ,12333.3 ,0,137.38,137.98
Observed WS=U101-07-00      ,U101-07-00_0001 ,12065.24,0,137.26,137.86
Observed WS=U101-07-00      ,U101-07-00_0001 ,11200.33,0,137.13,137.75
Observed WS=U101-07-00      ,U101-07-00_0001 ,10701.13,0,136.31,136.99
Observed WS=U101-07-00      ,U101-07-00_0001 ,10347.76,0,135.99,136.68
Observed WS=U101-07-00      ,U101-07-00_0001 ,10046.98,0,135.81,136.51
Observed WS=U101-07-00      ,U101-07-00_0001 ,10003.84,0,135.77,136.46
Observed WS=U101-07-00      ,U101-07-00_0001 ,9954.988,0,135.51,135.96
Observed WS=U101-07-00      ,U101-07-00_0001 ,9900.212,0,135.39,135.87
Observed WS=U101-07-00      ,U101-07-00_0001 ,9085.937,0,134.41,135.1
Observed WS=U101-07-00      ,U101-07-00_0001 ,8819.565,0,133.25,134.25
Observed WS=U101-07-00      ,U101-07-00_0001 ,5638.31 ,0,129.5,130.67
Observed WS=U101-07-00      ,U101-07-00_0001 ,5196.791,0,129.41,130.65
Observed WS=U101-07-00      ,U101-07-00_0001 ,4974.61 ,0,129.19,130.31
Observed WS=U101-07-00      ,U101-07-00_0001 ,4907.297,0,127.88,129.31
Observed WS=U101-07-00      ,U101-07-00_0001 ,4704.912,0,126.09,127.08
Observed WS=U101-07-00      ,U101-07-00_0001 ,4419.56 ,0,124.43,125.58
Observed WS=U101-07-00      ,U101-07-00_0001 ,3680.687,0,121.8,123.69
Observed WS=U101-07-00      ,U101-07-00_0001 ,3515.556,0,121.42,123.45
Observed WS=U101-07-00      ,U101-07-00_0001 ,3295.503,0,128.27,129.49
Observed WS=U101-07-00      ,U101-07-00_0001 ,3093.946,0,127.86,129.07
Observed WS=U101-07-00      ,U101-07-00_0001 ,2350.281,0,126.53,127.72
Observed WS=U101-07-00      ,U101-07-00_0001 ,1688.528,0,124.61,125.54
Observed WS=U101-07-00      ,U101-07-00_0001 ,1123.231,0,124.57,125.48
Observed WS=U101-07-00      ,U101-07-00_0001 ,1118.2  ,0,123.91,124.57
Observed WS=U101-07-00      ,U101-07-00_0001 ,1098.213,0,123.75,124.3
Observed WS=U101-07-00      ,U101-07-00_0001 ,1093.222,0,123.63,124.2
Observed WS=U101-07-00      ,U101-07-00_0001 ,1073.229,0,122.22,123.14
Observed WS=U101-07-00      ,U101-07-00_0001 ,1068.218,0,122.21,123.13
Observed WS=U101-07-00      ,U101-07-00_0001 ,870.9581,0,121.32,121.99
Observed WS=U101-07-00      ,U101-07-00_0001 ,843.7701,0,121.09,121.72
Observed WS=U101-07-00      ,U101-07-00_0001 ,838.4837,0,120.89,121.46
Observed WS=U101-07-00      ,U101-07-00_0001 ,821.0098,0,119.23,119.86
Observed WS=U101-07-00      ,U101-07-00_0001 ,815.2426,0,119.03,119.6
Observed WS=U101-07-00      ,U101-07-00_0001 ,163.4989,0,117.74,119.07
Observed WS=U101-07-00      ,U101-07-00_0001 ,114.7056,0,117.49,118.45
DSS Import GetInterval= 0
DSS Import GetPeak= 0
DSS Import FillOption= 0

--- U101-07-00.f03 (steady flow) ---

Flow Title=Storage Routing Flows
Program Version=4.10
Number of Profiles= 8
Profile Names=0.2,0.4,0.6,0.8,1,1.2,1.5,2
River Rch & RM=U101-07-00,U101-07-00_0001 ,14984.67
      25      50      74      99     124     149     186     248
River Rch & RM=U101-07-00,U101-07-00_0001 ,8992.246
      37      75     112     150     187     224     281     374
River Rch & RM=U101-07-00,U101-07-00_0001 ,5322.362
      44      88     131     175     219     263     329     438
River Rch & RM=U101-07-00,U101-07-00_0001 ,3295.503
      26      53      79     106     132     158     198     264
Boundary for River Rch & Prof#=U101-07-00,U101-07-00_0001 , 1
Up Type= 0
Dn Type= 3
Dn Slope=0.0024
Boundary for River Rch & Prof#=U101-07-00,U101-07-00_0001 , 2
Up Type= 0
Dn Type= 3
Dn Slope=0.0024
Boundary for River Rch & Prof#=U101-07-00,U101-07-00_0001 , 3
Up Type= 0
Dn Type= 3
Dn Slope=0.0024
Boundary for River Rch & Prof#=U101-07-00,U101-07-00_0001 , 4
Up Type= 0
Dn Type= 3
Dn Slope=0.0024
Boundary for River Rch & Prof#=U101-07-00,U101-07-00_0001 , 5
Up Type= 0
Dn Type= 3
Dn Slope=0.0024
Boundary for River Rch & Prof#=U101-07-00,U101-07-00_0001 , 6
Up Type= 0
Dn Type= 3
Dn Slope=0.0024
Boundary for River Rch & Prof#=U101-07-00,U101-07-00_0001 , 7
Up Type= 0
Dn Type= 3
Dn Slope=0.0024
Boundary for River Rch & Prof#=U101-07-00,U101-07-00_0001 , 8
Up Type= 0
Dn Type= 3
Dn Slope=0.0024
DSS Import GetInterval= 0
DSS Import GetPeak= 0
DSS Import FillOption= 0

--- U101-07-00.g01 (geometry) ---

Geom Title=U101-07-00 2019 (Re-Study)
Program Version=4.10

River Reach=U101-07-00      ,U101-07-00_0001
Reach XY= 30
2986626.4557337813858591.79086022987205.4020824413858609.6792759
2987226.8252679413858614.95288742987334.9306947713858621.2150139
2987648.7004084413858634.3987146 2988096.942622213858643.6270426
2988130.8903889513858648.90065412988893.2317120313858669.6647202
2990586.9937444513858734.26432852990694.7491063613858733.7932009
2990840.7780137813858745.47034292991083.06394653 13858749.140283
 2991390.520680713858761.29183352991395.1479680213858765.2458939
2992581.0422497813858802.5962128 2993017.389474213858822.2648087
 2994859.149570213858882.59408442995089.8502242713858894.7745062
2996637.8838736113858948.0686909 2996808.661419213858957.7261519
2996914.1300402713858984.42294892997110.2359472813858987.3894784
2997969.8064066213859023.31460342998443.4268504413859025.2922898
2998618.4389676213859030.56557322999157.9775866913859054.2961688
2999769.3667838613859070.77546652999823.7426593613859076.7062289
3000381.7513858713859087.99918543001651.4873634413859139.4839905

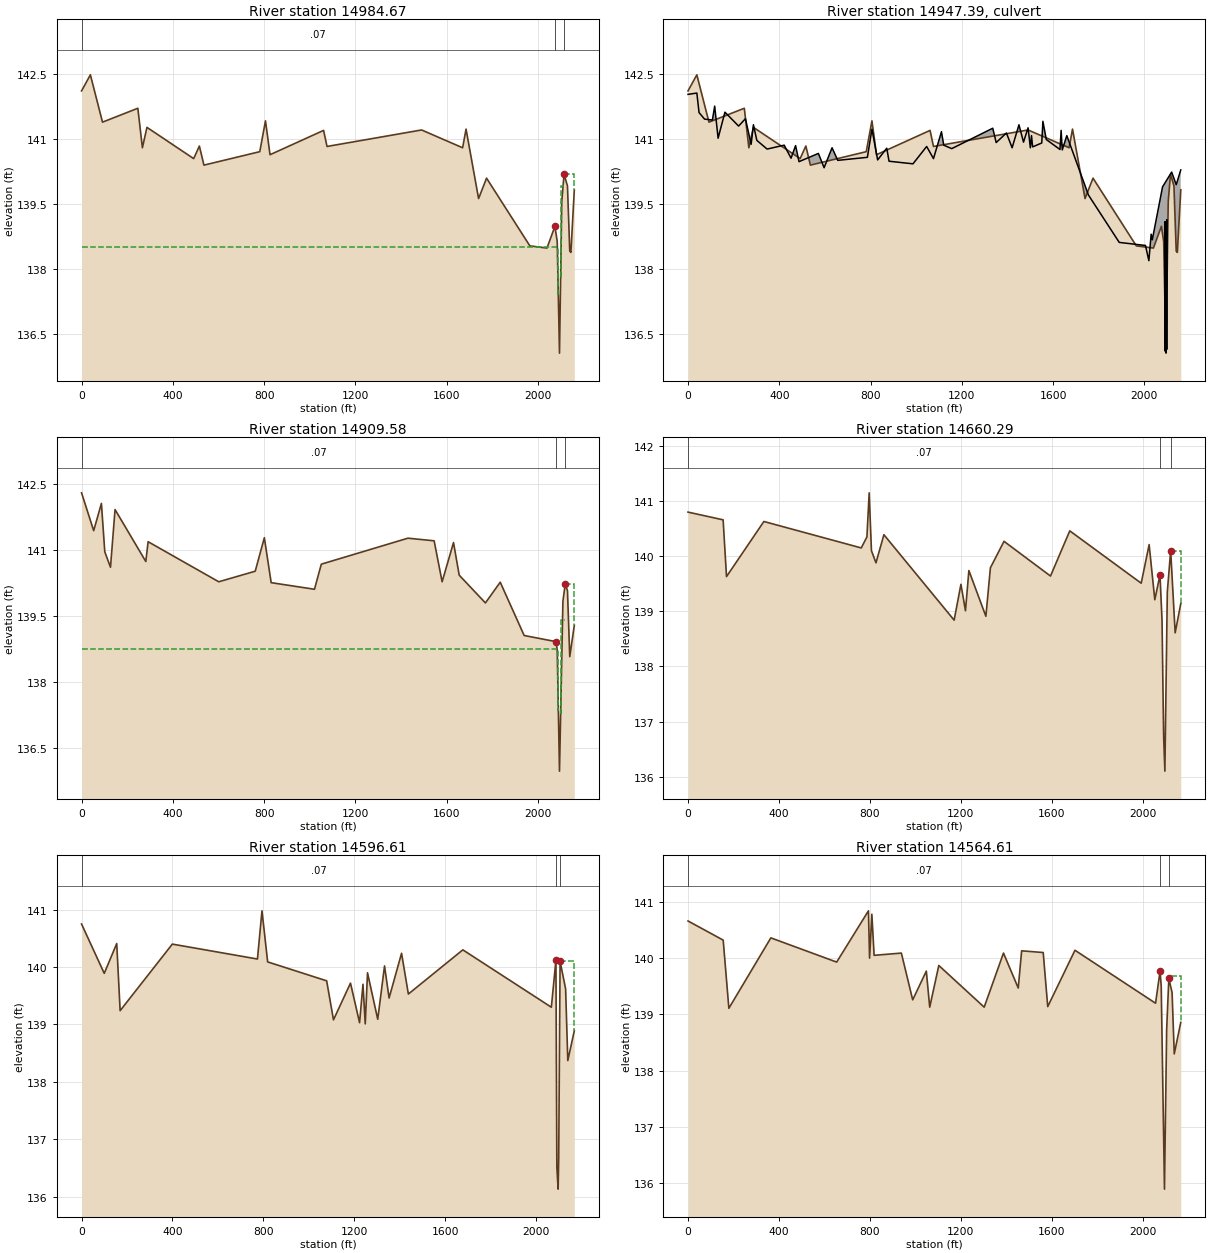
Type RM Length L Ch R = 1 ,14984.67,75.72,75.09,75.01
BEGIN DESCRIPTION:
Upstream Section - ACCESS RD #2
FL lowered to 136.07 (WBS survey notes)
END DESCRIPTION:
Node Name=W
XS GIS Cut Line= 3
 2986590.112958713860683.56292342986594.3855879513860591.8117945
2986690.5596081913858526.6010299
#Sta/Elev= 30
       0  142.11   38.67  142.48   91.85  141.39  246.66  141.71  266.63   140.8
  286.61  141.27  491.36  140.55  516.33  140.84   536.3   140.4     781  140.71
  805.97  141.42  825.94  140.64 1060.65   141.2 1075.64  140.83 1490.12  141.21
  1669.9   140.8 1684.88  141.23 1739.81  139.63 1774.77   140.1 1964.54  138.54
 2039.44  138.49  2074.4  138.99 2084.39  138.64 2094.38  136.07 2104.36  139.56
 2114.35  140.19 2129.33  139.92 2139.32  138.42 2144.31  138.39 2159.29  139.83
#Mann= 3 ,-1 , 0
       0     .07       0  2074.4     .04       0 2114.35     .07       0
#XS Ineff= 3 ,-1
       0 2089.38  138.51 2099.37 2114.35  139.93 2114.35 2159.29  140.19
Permanent Ineff=
       F       F       F
Bank Sta=2074.4,2114.35
XS Rating Curve= 0 ,0
Exp/Cntr=0.5,0.3

Type RM Length L Ch R = 2 ,14947.39,,,
BEGIN DESCRIPTION:
ACCESS RD #2
3-36" CMPs
END DESCRIPTION:
Node Name=ACCESS RD #2
Bridge Culvert--1,0,-1,-1, 0
Deck Dist Width WeirC Skew NumUp NumDn MinLoCord MaxHiCord MaxSubmerge Is_Ogee
24.5,25.5,2.6,0, 60, 60, , , 0.98, 0, 0,0,,
       0   38.67   48.34   72.51  106.83  116.82   131.8  161.76  221.69  251.65
  276.62  286.61  301.59  346.54  421.44  451.41  471.38  486.36  571.26  596.23
  631.19  656.15  785.99  805.97  830.94  870.89  880.88  985.75 1045.67 1075.64
 1110.59 1120.58 1155.54 1335.31  1350.3 1395.24 1420.21 1450.17 1470.15 1490.12
 1500.11  1505.1  1510.1 1550.05 1555.04 1570.02 1629.95 1634.94 1639.94 1659.91
  1754.8 1889.63 2004.49 2019.47 2029.45 2034.45 2079.39 2119.34 2139.32 2159.29
  142.03  142.06  141.61  141.46  141.44  141.76  141.02  141.62   141.3  141.47
  140.88  141.33  140.97  140.77  140.86  140.56  140.85  140.48  140.67  140.34
   140.8  140.51  140.58  141.23  140.52  140.79  140.49  140.43  140.83  140.55
  141.17  140.86  140.78  141.25  140.92  141.14   140.8  141.33  140.93  141.26
   140.8  141.08  140.82  140.91  141.41  140.99  140.76   141.2  140.75  141.08
  139.71  138.62  138.55   138.2  138.81  138.68   139.9  140.24  139.95  140.29
                                                                                
                                                                                
                                                                                
                                                                                
                                                                                
                                                                                
       0   38.67   48.34   72.51  106.83  116.82   131.8  161.76  221.69  251.65
  276.62  286.61  301.59  346.54  421.44  451.41  471.38  486.36  571.26  596.23
  631.19  656.15  785.99  805.97  830.94  870.89  880.88  985.75 1045.67 1075.64
 1110.59 1120.58 1155.54 1335.31  1350.3 1395.24 1420.21 1450.17 1470.15 1490.12
 1500.11  1505.1  1510.1 1550.05 1555.04 1570.02 1629.95 1634.94 1639.94 1659.91
  1754.8 1889.63 2004.49 2019.47 2029.45 2034.45 2079.39 2119.34 2139.32 2159.29
  142.03  142.06  141.61  141.46  141.44  141.76  141.02  141.62   141.3  141.47
  140.88  141.33  140.97  140.77  140.86  140.56  140.85  140.48  140.67  140.34
   140.8  140.51  140.58  141.23  140.52  140.79  140.49  140.43  140.83  140.55
  141.17  140.86  140.78  141.25  140.92  141.14   140.8  141.33  140.93  141.26
   140.8  141.08  140.82  140.91  141.41  140.99  140.76   141.2  140.75  141.08
  139.71  138.62  138.55   138.2  138.81  138.68   139.9  140.24  139.95  140.29
                                                                                
                                                                                
                                                                                
                                                                                
                                                                                
                                                                                
BR Coef=-1 , 0 , 0 ,, 0 ,,,0.8,-1,,0,
WSPro=,,,, 1 ,,,, 0 ,,,, 0 ,,,,-1 ,-1 ,-1 , 0 , 0 , 0 , 0 , 0
Culvert=1,3,,32,0.024,0.9,1,2,3,136.11,2090.88,135.9,2090.87,Culvert #1  , 0 ,21.5
Culvert Bottom n=0.024
Culvert=1,3,,32,0.024,0.9,1,2,3,136.07,2094.38,135.97,2094.37,Culvert #2  , 0 ,21.5
Culvert Bottom n=0.024
Culvert=1,3,,32,0.024,0.9,1,2,3,136.15,2097.88,136.01,2097.87,Culvert #3  , 0 ,21.5
Culvert Bottom n=0.024
BC Design=,, 0 ,, 0 ,,,,,,
BC Use User HTab Curves=0
BC User HTab FreeFlow(D)= 0

Type RM Length L Ch R = 1 ,14909.58,254.5,249.29,248.98
BEGIN DESCRIPTION:
Downstream Section - ACCESS RD #2
FL lowered to 135.97 (WBS survey notes)
END DESCRIPTION:
XS GIS Cut Line= 3
2986665.0393180313860687.05208962986669.3119472713860595.3009608
2986765.4859675313858530.0901962
#Sta/Elev= 30
       0  142.29   53.18  141.43   87.02  142.05  101.84  140.95  126.81   140.6
  146.78  141.91  281.62  140.73   291.6  141.18  601.22  140.27  761.03  140.51
  800.98  141.27  830.94  140.25  1020.7   140.1 1050.67  140.67  1430.2  141.26
 1545.05   141.2 1580.01  140.27 1629.95  141.16 1654.92  140.42 1769.78  139.79
  1834.7  140.26 1939.57  139.05 2079.39  138.91 2084.39  138.72 2094.37  135.97
 2109.36  139.83 2119.34  140.21 2129.33  140.07 2139.32  138.57 2159.29  139.28
#Mann= 3 ,-1 , 0
       0     .07       0 2079.39     .04       0 2119.34     .07       0
#XS Ineff= 3 ,-1
       0 2089.38  138.75 2099.37 2119.34   139.4 2119.34 2159.29  140.21
Permanent Ineff=
       F       F       F
Bank Sta=2079.39,2119.34
XS Rating Curve= 0 ,0
Exp/Cntr=0.5,0.3

Type RM Length L Ch R = 1 ,14660.29,63.16,63.68,63.7
XS GIS Cut Line= 5
2986941.0148159413860698.29681782986988.9599300313859633.8799834
2987011.53993736 13858642.0499462987011.53993736 13858601.920105
2987013.5087654413858532.8546264
#Sta/Elev= 30
       0   140.8  154.35  140.66  169.28  139.63  333.59  140.63  761.78  140.15
  786.67  140.35  796.63  141.15  806.59   140.1  826.51  139.88  861.36  140.39
 1170.19  138.84  1200.1  139.49 1220.04  139.01    1235  139.74 1309.78  138.91
 1329.72  139.79 1389.54  140.27 1593.94  139.64 1678.69  140.46 1992.77  139.51
 2027.67  140.21 2052.59  139.21 2075.41  139.66 2084.33  138.84  2091.5  136.72
  2096.9   136.1 2107.58  139.35 2122.39   140.1 2142.13  138.61  2166.8  139.14
#Mann= 3 ,-1 , 0
       0     .07       0 2075.41     .04       0 2122.39     .07       0
#XS Ineff= 2 ,-1
       0 1890.21   139.4 2122.39  2166.8   140.1
Permanent Ineff=
       F       F
Bank Sta=2075.41,2122.39
XS Rating Curve= 0 ,0
Exp/Cntr=0.3,0.1

Type RM Length L Ch R = 1 ,14596.61,32.44,32,32
XS GIS Cut Line= 3
 2987032.090421213860702.07666582987074.8101520213858619.8298461
 2987077.080160613858533.8001625
#Sta/Elev= 30
       0  140.75   99.89  139.89  154.83  140.41  169.81  139.24  399.56   140.4
  774.14  140.14  794.12  140.98  819.09  140.09  1078.8  139.76 1108.77  139.08
 1183.69  139.72 1223.64  139.03 1238.63   139.7 1248.62  139.01  1258.6   139.9
 1303.55  139.09 1333.52  140.02  1353.5  139.46 1408.44  140.24 1438.41  139.53
 1678.14   140.3 2067.71   139.3 2087.84  140.12 2091.95  136.51 2097.54  136.13
 2100.09  136.68 2106.17   140.1  2130.5  139.62 2140.07  138.37 2168.75  138.89
#Mann= 3 ,-1 , 0
       0     .07       0 2087.84     .04       0 2106.17     .07       0
#XS Ineff= 2 ,-1
       0 1845.09   138.7 2106.17 2168.75   140.1
Permanent Ineff=
       F       F
Bank Sta=2087.84,2106.17
XS Rating Curve= 0 ,0
Exp/Cntr=0.3,0.1

Type RM Length L Ch R = 1 ,14564.61,219.64,219.01,218.59
XS GIS Cut Line= 3
2987067.1477657713860702.83880342987106.7900749413858620.9899488
2987109.0600835213858534.9599371
#Sta/Elev= 30
       0  140.66  154.79  140.32  179.76  139.11  364.51  140.36  654.13  139.93
  793.94  140.84  798.94     140  808.92  140.78  818.91  140.05  938.75  140.09
  988.68  139.26  1048.6  139.77 1063.58  139.13 1103.53  139.87 1303.26  139.13
 1388.15  140.09 1453.07  139.47 1468.05  140.13 1562.92   140.1 1582.89  139.14
 1702.74  140.14 2057.27   139.2 2077.24  139.77 2082.23   139.5 2096.55   135.9
 2106.14  138.73  2115.7  139.64 2130.04  139.39 2139.61   138.3 2168.29  138.86
#Mann= 3 ,-1 , 0
       0     .07       0 2077.24     .04       0  2115.7     .07       0
#XS Ineff= 2 ,-1
       0 1821.01   138.6 2120.48 2168.29  139.68
Permanent Ineff=
       F       F
Bank Sta=2077.24,2115.7
XS Rating Curve= 0 ,0
Exp/Cntr=0.3,0.1

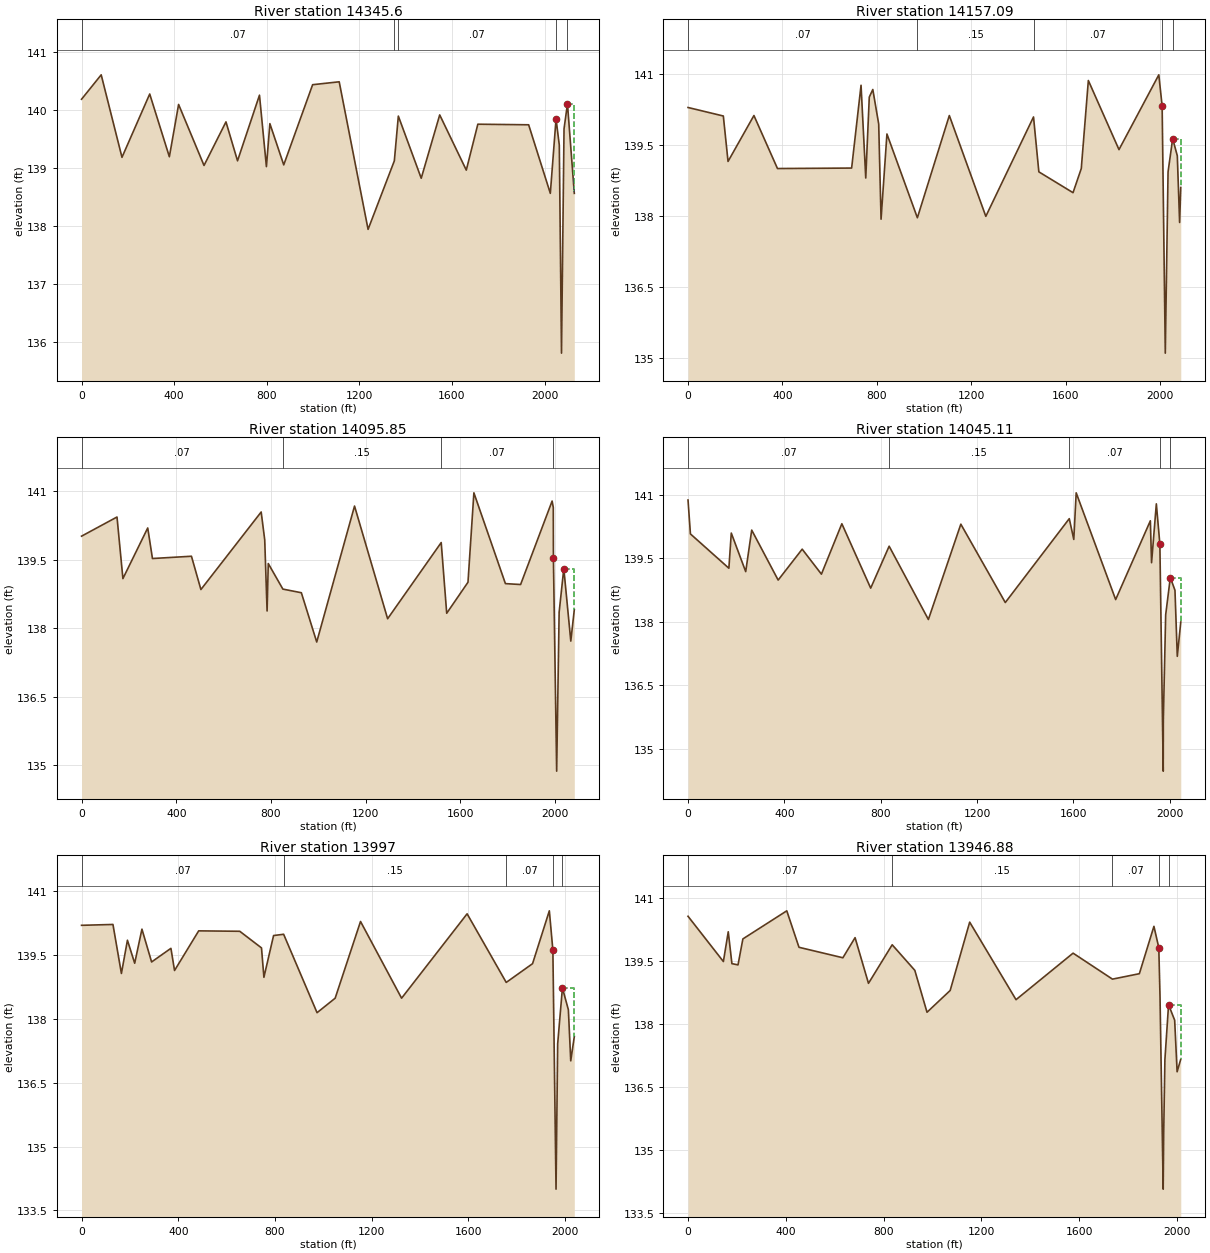
Type RM Length L Ch R = 1 ,14345.6 ,192.11,188.51,188.13
XS GIS Cut Line= 3
2987310.6082368613860687.99631342987319.6761321113858771.3800679
2987327.52618203 13858559.439875
#Sta/Elev= 30
       0  140.18   84.85   140.6  174.69  139.18  294.48  140.27  379.33  139.19
  419.26  140.09  529.07  139.04  623.91  139.79  673.82  139.12  768.65  140.25
   798.6  139.02  813.57  139.76  873.47  139.05  998.25  140.43 1113.05  140.48
 1237.83  137.94 1351.28  139.12 1368.55  139.89 1467.43  138.82 1547.29  139.91
 1662.09  138.96    1712  139.75 1931.44  139.74 2025.15  138.56 2049.81  139.84
 2063.88  139.39 2073.39  135.81 2084.34  139.67 2099.13   140.1 2128.73  138.56
#Mann= 5 ,-1 , 0
       0     .07       0 1351.28     .15       0 1368.55     .07       0
 2049.81     .04       0 2099.13     .07       0
#XS Ineff= 2 ,-1
       0 1637.52   138.5 2099.13 2128.73   140.1
Permanent Ineff=
       F       F
Bank Sta=2049.81,2099.13
XS Rating Curve= 0 ,0
Exp/Cntr=0.3,0.1

Type RM Length L Ch R = 1 ,14157.09,61.9,61.24,61.03
XS GIS Cut Line= 4
2987491.16561852 13860650.9435662987507.6600081213859428.8600522
2987507.66000812 13858709.6600472987517.1301335213858562.9798942
#Sta/Elev= 30
       0  140.29  149.66  140.11  169.61  139.15  279.36  140.12  379.13     139
  693.41  139.01  733.32  140.76  753.27   138.8  768.24  140.51   783.2  140.67
  808.15  139.94  818.12  137.93  843.07  139.73  972.08  137.96 1107.46  140.12
 1262.15  137.99 1464.27  140.09  1486.9  138.93 1631.74  138.49  1666.7     139
 1696.67  140.86 1826.52   139.4 1995.29  140.98 2009.41  140.32 2022.77   135.1
 2034.48  138.93 2054.08  139.63 2073.68  139.27 2083.48  137.86 2088.38   138.6
#Mann= 5 ,-1 , 0
       0     .07       0  972.08     .15       0 1464.27     .07       0
 2009.41     .04       0 2054.08     .07       0
#XS Ineff= 2 ,-1
       0 1684.08   139.4 2054.08 2088.38  139.63
Permanent Ineff=
       F       F
Bank Sta=2009.41,2054.08
XS Rating Curve= 0 ,0
Exp/Cntr=0.3,0.1

Type RM Length L Ch R = 1 ,14095.85,51.43,50.74,50.54
XS GIS Cut Line= 4
2987564.5171778613860635.31958152987560.43221228 13858978.533525
2987573.0299561213858658.27990042987577.10015795 13858554.809963
#Sta/Elev= 30
       0  140.02  149.71  140.44  174.66  139.09  279.46   140.2  299.42  139.53
   464.1  139.58  504.02  138.85  758.53  140.55   773.5  139.94  783.48  138.38
  788.47  139.42  850.14  138.86   928.2  138.78  993.08   137.7 1152.77  140.68
 1292.49  138.21 1518.75  139.88 1542.01  138.33 1631.84  139.01 1656.79  140.97
 1789.92  138.98 1854.02  138.96 1987.15  140.79 1992.06  140.65 1992.57  139.54
 2006.33  134.87 2016.74  138.35 2036.46  139.31 2066.04  137.72 2080.84  138.41
#Mann= 4 ,-1 , 0
       0     .07       0  850.14     .15       0 1518.75     .07       0
 1992.57     .04       0
#XS Ineff= 2 ,-1
       0 1736.82  138.21 2036.46 2080.84  139.31
Permanent Ineff=
       F       F
Bank Sta=1992.57,2036.46
XS Rating Curve= 0 ,0
Exp/Cntr=0.3,0.1

Type RM Length L Ch R = 1 ,14045.11,46.84,48.11,48.28
XS GIS Cut Line= 4
 2987623.032152713860604.92102032987619.6509258613859007.7053827
 2987624.549866213858654.96986772987625.8900866113858558.4700607
#Sta/Elev= 30
       0  140.87    9.98  140.07   169.7  139.26  179.69  140.09  239.58  139.18
  264.54  140.16  374.35  138.98  474.17  139.71  554.04  139.12  638.89  140.31
  758.68  138.79  835.31  139.78  998.26  138.05 1133.03   140.3  1317.7  138.45
  1583.4  140.43 1602.18  139.94 1612.12  141.04 1776.08  138.52 1920.17  140.38
 1925.14  139.39 1945.01  140.78 1959.65  139.83 1973.65  134.47 1974.11   135.7
 1983.76  138.16 2003.06  139.04 2022.37  138.74 2032.02  137.18 2046.49  137.99
#Mann= 5 ,-1 , 0
       0     .07       0  835.31     .15       0  1583.4     .07       0
 1959.65     .04       0 2003.06     .07       0
#XS Ineff= 2 ,-1
       0 1778.05  138.21 2003.06 2046.49  139.04
Permanent Ineff=
       F       F
Bank Sta=1959.65,2003.06
XS Rating Curve= 0 ,0
Exp/Cntr=0.3,0.1

Type RM Length L Ch R = 1 ,13997   ,50.83,50.13,49.85
XS GIS Cut Line= 6
2987644.4222017813860593.80883782987640.0596776913859015.6919153
2987642.4868381913859004.50755442987655.7056437713858943.5942904
2987671.4999035313858656.56008762987676.9001551913858558.4198639
#Sta/Elev= 30
       0  140.19  129.85  140.21   164.8  139.06  189.77  139.84  219.74   139.3
   249.7   140.1  289.66  139.33  369.56  139.65  384.54  139.13  484.42  140.06
  654.22  140.05  744.11  139.66   754.1  138.97  794.05  139.95  835.65  139.98
  973.84  138.14 1048.75  138.48 1153.63  140.28 1323.43  138.48 1594.36  140.46
 1756.17  138.85 1865.02  139.29 1934.41  140.53 1949.01  139.61 1962.08     134
 1968.86  137.41 1988.51  138.72 2013.09  138.21 2022.91  137.01 2037.66  137.58
#Mann= 5 ,-1 , 0
       0     .07       0  835.65     .15       0 1756.17     .07       0
 1949.01     .04       0 1988.51     .07       0
#XS Ineff= 2 ,-1
       0 1821.29  138.21 1988.51 2037.66  138.72
Permanent Ineff=
       F       F
Bank Sta=1949.01,1988.51
XS Rating Curve= 0 ,0
Exp/Cntr=0.3,0.1

Type RM Length L Ch R = 1 ,13946.88,35.33,36.6,37.09
XS GIS Cut Line= 5
2987681.3932564413860574.60185522987672.0530520213859028.2115753
2987695.4535957713858934.76786452987722.0900254413858662.8300882
2987724.7199414413858562.9700517
#Sta/Elev= 30
       0  140.57  144.67  139.49  164.62   140.2  179.58  139.44  204.53  139.41
  224.48  140.03  404.06   140.7  453.95  139.83  633.53  139.58  683.42  140.06
  738.29  138.97  835.25  139.89  927.85  139.28  977.74  138.28 1072.52   138.8
 1152.33  140.43 1341.89  138.58 1575.32  139.69 1736.46  139.07 1846.44   139.2
 1906.05  140.33 1925.98  139.82 1930.97  138.65 1943.96  134.06 1945.96  135.38
 1950.95  137.15 1965.94  138.46 1990.91  138.09  2000.9  136.86 2015.89  137.16
#Mann= 5 ,-1 , 0
       0     .07       0  835.25     .15       0 1736.46     .07       0
 1925.98     .04       0 1965.94     .07       0
#XS Ineff= 2 ,-1
       0 1868.28  138.21 1965.94 2015.89  138.46
Permanent Ineff=
       F       F
Bank Sta=1925.98,1965.94
XS Rating Curve= 0 ,0
Exp/Cntr=0.5,0.3