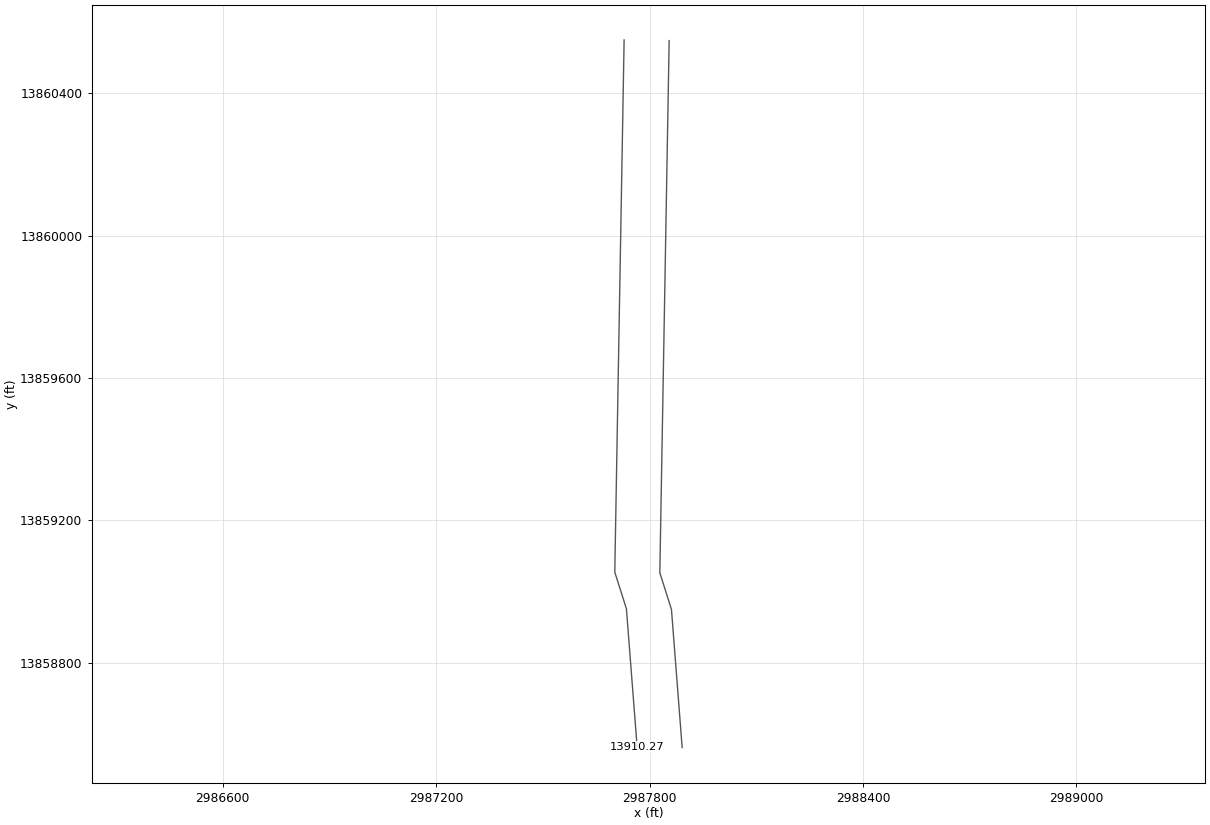
HEC-RAS study U101-07-00.prj: U101-07-00 2019 (Re-Study)

--- U101-07-00.g01 (geometry) --- (continued)

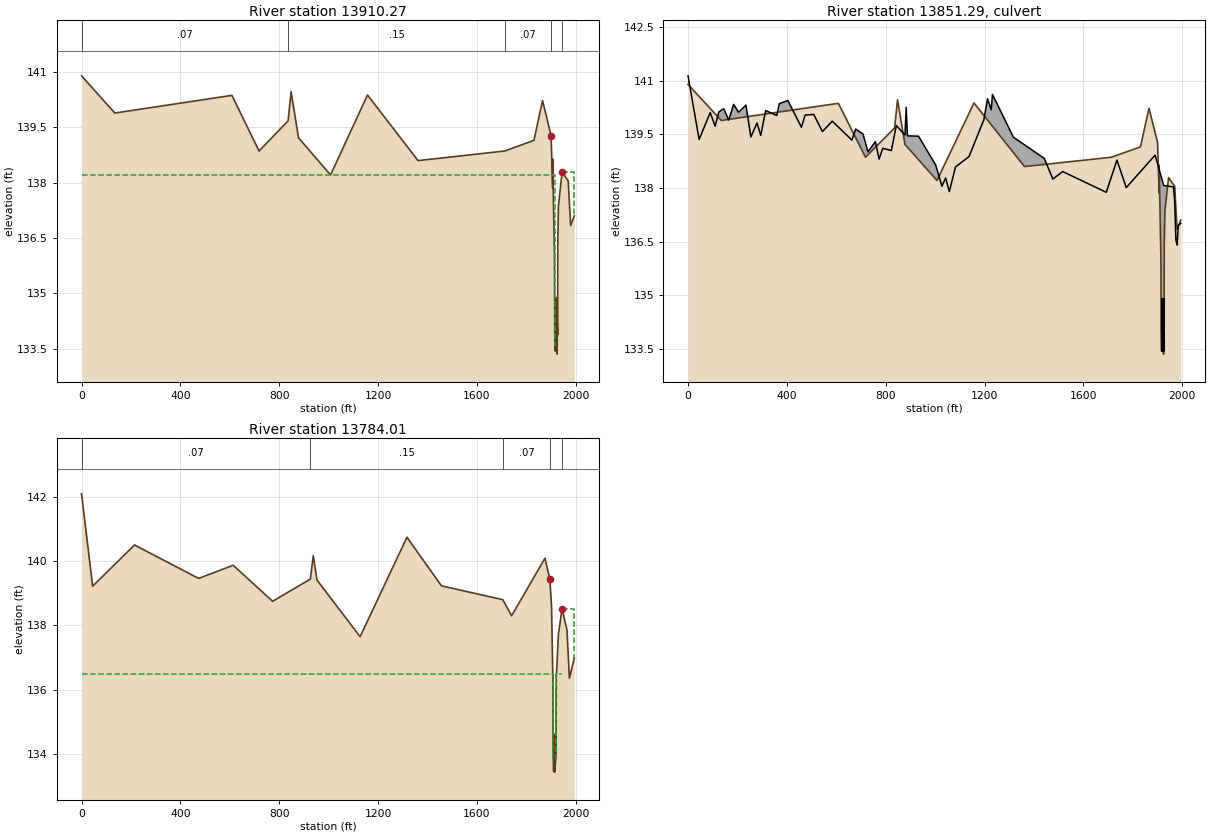
Type RM Length L Ch R = 1 ,13910.27,126.21,126.26,126.26
BEGIN DESCRIPTION:
Upstream Section - WINCHESTER RANCH TRAIL
END DESCRIPTION:
Node Name=V
XS GIS Cut Line= 6
2987728.6215084513860550.06679932987702.3955110313859054.0008938
2987735.0926241113858950.93318652987744.8770533713858824.7493838
2987750.6772386113858749.94999272987765.2070651913858562.5701181
#Sta/Elev= 30
       0   140.9  134.67  139.89  608.49  140.37  718.22  138.86   835.9  139.68
   847.9  140.47  877.83  139.22  1007.5  138.21 1157.13  140.38 1361.63   138.6
 1712.35  138.86 1830.74  139.15 1865.36  140.23 1899.99  139.28 1906.35  137.86
 1906.46  138.64 1913.83  135.93 1914.64  133.95 1916.53  133.44 1920.33  134.88
 1920.75  133.44 1924.77  133.35 1924.79   134.2 1926.54  133.87 1927.17  136.39
 1929.66  137.36  1944.5  138.29 1969.23  138.05 1979.12  136.84 1993.96   137.1
#Mann= 5 ,-1 , 0
       0     .07       0   835.9     .15       0 1712.35     .07       0
 1899.99     .04       0  1944.5     .07       0
#XS Ineff= 2 ,-1
       0 1916.06  138.21  1944.5 1993.96  138.29
Permanent Ineff=
       F       F
Bank Sta=1899.99,1944.5
XS Rating Curve= 0 ,0
Exp/Cntr=0.5,0.3

Type RM Length L Ch R = 2 ,13851.29,,,
BEGIN DESCRIPTION:
WINCHESTER RANCH TRAIL
END DESCRIPTION:
Node Name=WINCHESTER RANCH
Bridge Culvert--1,0,-1,-1, 0
Deck Dist Width WeirC Skew NumUp NumDn MinLoCord MaxHiCord MaxSubmerge Is_Ogee
34,47,2.6,0, 60, 60, , , 0.98, 0, 0,0,,
       0   44.89   89.78  109.73  124.69  144.64  164.59  184.54  204.49  234.42
  254.37  279.31  294.27  314.22  359.11  369.09     404  458.86  473.83  508.74
  543.65  583.56  663.36  678.32  708.25   728.2  758.12  773.09  788.05  822.96
  842.91  877.83  882.81   887.8  932.69 1002.52 1027.45 1042.42 1057.38 1082.32
 1137.18 1197.04    1212 1226.96 1231.95 1316.74 1441.43 1476.35 1515.96 1692.46
 1735.68 1773.19 1890.09 1924.71 1964.28 1969.23 1974.17 1979.12 1984.07 1993.96
  141.14  139.36  140.11  139.73  140.13  140.22   139.9  140.34  140.12  140.32
  139.43  139.82  139.47  140.17  140.03  140.36  140.45   139.7  140.04  140.06
  139.58  139.87  139.34  139.65  139.51  139.01   139.3  138.81  139.11  139.05
  139.75  139.48  140.26  139.46  139.45  138.64  138.05  138.28   137.9  138.59
  138.88  139.91   140.5  140.19  140.62  139.42  138.83  138.25  138.46  137.88
  138.78  138.01  138.92  138.07  138.03  137.64  136.54   136.4  136.96  137.01
       0       0       0       0       0       0       0       0       0       0
       0       0       0       0       0       0       0       0       0       0
       0       0       0       0       0       0       0       0       0       0
       0       0       0       0       0       0       0       0       0       0
       0       0       0       0       0       0       0       0       0       0
       0       0       0       0       0       0       0       0       0       0
       0   44.89   89.78  109.73  124.69  144.64  164.59  184.54  204.49  234.42
  254.37  279.31  294.27  314.22  359.11  369.09     404  458.86  473.83  508.74
  543.65  583.56  663.36  678.32  708.25   728.2  758.12  773.09  788.05  822.96
  842.91  877.83  882.81   887.8  932.69 1002.52 1027.45 1042.42 1057.38 1082.32
 1137.18 1197.04    1212 1226.96 1231.95 1316.74 1441.43 1476.35 1515.96 1692.46
 1735.68 1773.19 1890.09 1924.71 1964.28 1969.23 1974.17 1979.12 1984.07 1993.96
  141.14  139.36  140.11  139.73  140.13  140.22   139.9  140.34  140.12  140.32
  139.43  139.82  139.47  140.17  140.03  140.36  140.45   139.7  140.04  140.06
  139.58  139.87  139.34  139.65  139.51  139.01   139.3  138.81  139.11  139.05
  139.75  139.48  140.26  139.46  139.45  138.64  138.05  138.28   137.9  138.59
  138.88  139.91   140.5  140.19  140.62  139.42  138.83  138.25  138.46  137.88
  138.78  138.01  138.92  138.07  138.03  137.64  136.54   136.4  136.96  137.01
       0       0       0       0       0       0       0       0       0       0
       0       0       0       0       0       0       0       0       0       0
       0       0       0       0       0       0       0       0       0       0
       0       0       0       0       0       0       0       0       0       0
       0       0       0       0       0       0       0       0       0       0
       0       0       0       0       0       0       0       0       0       0
BR Coef=-1 , 0 , 0 ,, 0 ,,,0.8,-1,,0,
WSPro=,,,, 1 ,,,, 0 ,,,, 0 ,,,,-1 ,-1 ,-1 , 0 , 0 , 0 , 0 , 0
Culvert=1,1.5,,97.8,0.013,0.7,1,1,1,133.42,1916.81,133.41,1917.98,Culvert #1  , 0 ,13.65
Culvert Bottom n=0.013
Culvert=1,1.5,,97.8,0.013,0.7,1,1,1,133.42,1921.12,133.48,1909.56,Culvert #2  , 0 ,13.65
Culvert Bottom n=0.013
Culvert=1,1.5,,97.8,0.013,0.7,1,1,1,133.42,1925.37,133.43,1913.85,Culvert #3  , 0 ,13.65
Culvert Bottom n=0.013
BC Design=,, 0 ,, 0 ,,,,,,
BC Use User HTab Curves=0
BC User HTab FreeFlow(D)= 0

Type RM Length L Ch R = 1 ,13784.01,36.7,34.89,34.16
BEGIN DESCRIPTION:
Downstream Section - WINCHESTER RANCH TRAIL
END DESCRIPTION:
Node Name=U
XS GIS Cut Line= 6
2987855.2278825313860548.37881052987829.00188512 13859052.312905
 2987861.698998213858949.24519782987871.48342745 13858823.061395
 2987877.283612713858748.26200392987891.8134392813858560.8821294
#Sta/Elev= 30
       0  142.09   44.89  139.22  214.47   140.5  473.83  139.46  613.48  139.87
  773.09  138.75  925.79  139.44  937.68  140.17  952.64  139.41 1127.21  137.65
 1316.74  140.74  1456.4  139.23 1704.72   138.8 1740.37   138.3 1875.26  140.09
 1895.04  139.43 1901.91  138.58 1907.61  136.08 1908.59  133.98 1910.31  133.46
 1914.31  134.62 1914.33  133.44 1920.42  133.98 1920.47  135.28 1921.15  136.39
 1929.66  137.73  1944.5  138.52 1964.28  137.86 1974.17  136.36 1993.96  136.99
#Mann= 5 ,-1 , 0
       0     .07       0  925.79     .15       0 1704.72     .07       0
 1895.04     .04       0  1944.5     .07       0
#XS Ineff= 3 ,-1
       0 1908.81   136.5 1918.73  1944.5   136.5  1944.5 1993.96  138.52
Permanent Ineff=
       F       F       F
Bank Sta=1895.04,1944.5
XS Rating Curve= 0 ,0
Exp/Cntr=0.5,0.3