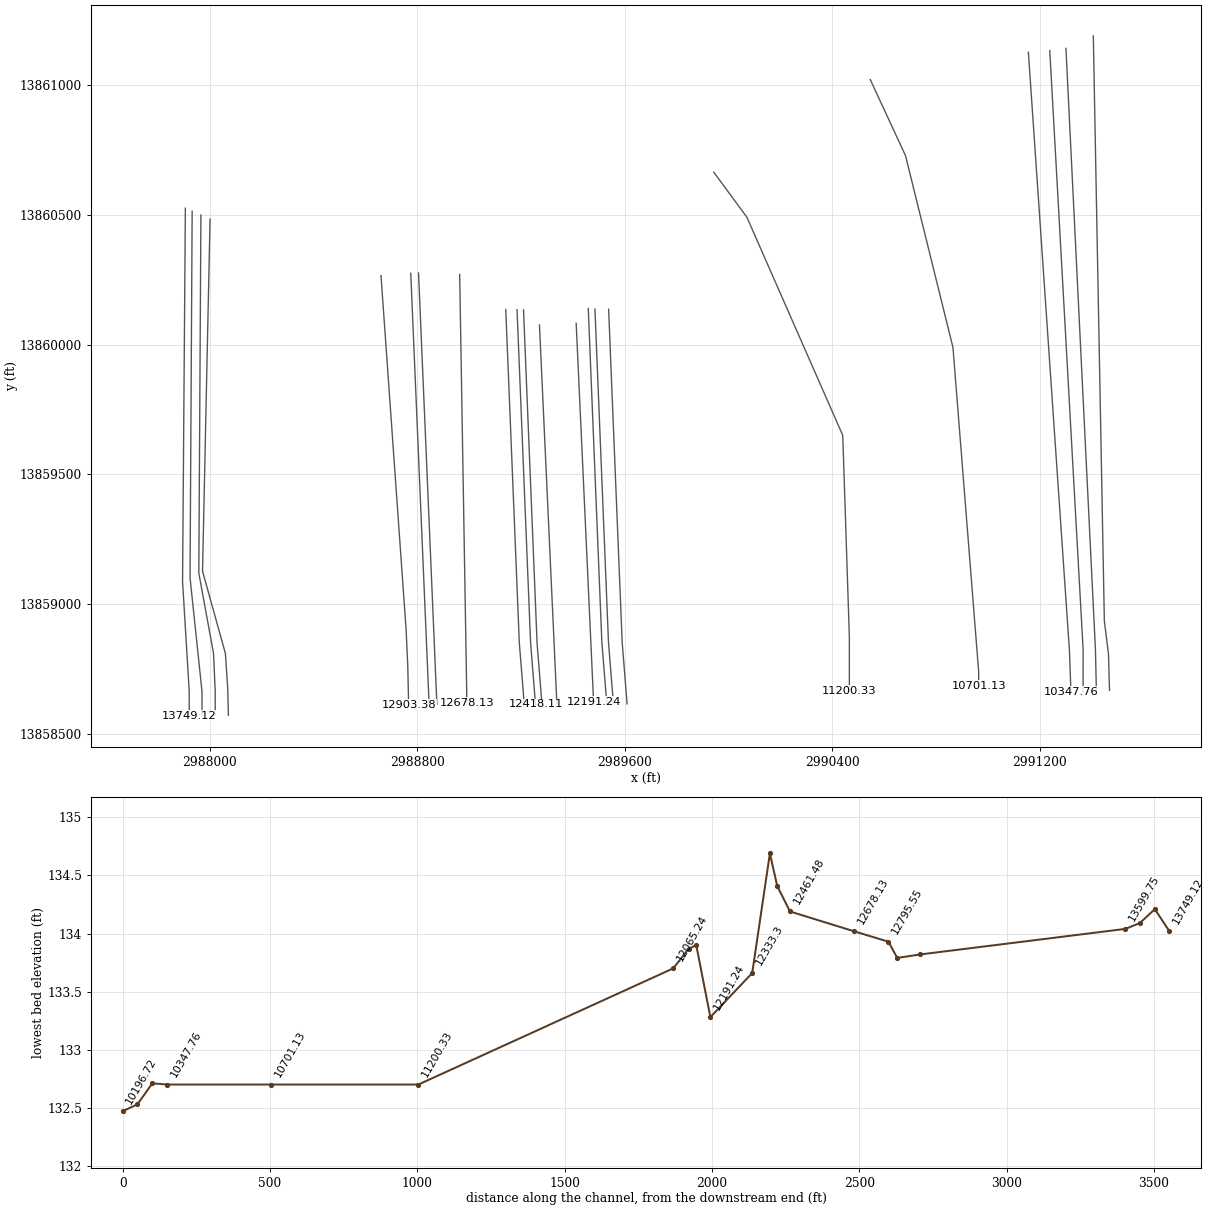
HEC-RAS study U101-07-00.prj: U101-07-00 2019 (Re-Study)

--- U101-07-00.g01 (geometry) --- (continued)

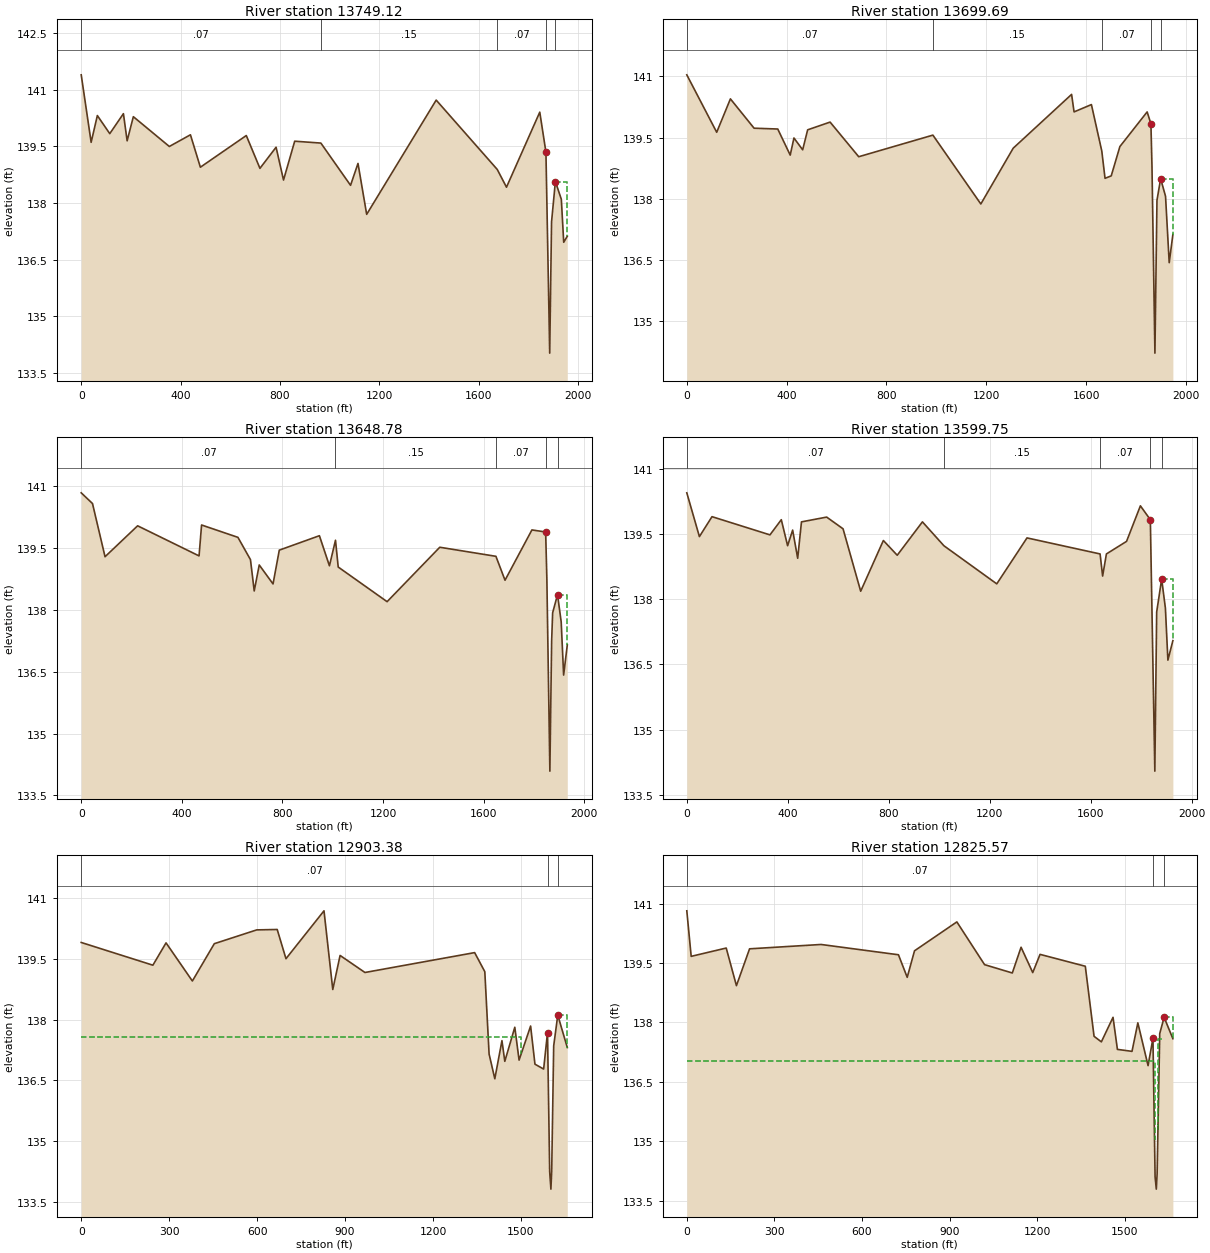
Type RM Length L Ch R = 1 ,13749.12,48.82,49.43,49.43
XS GIS Cut Line= 4
2987905.6519942713860526.14558732987894.86559853 13859086.678978
2987920.42985186 13858665.4199782987920.5299172713858569.4900518
#Sta/Elev= 30
       0   141.4   39.99  139.61   64.98  140.32  114.96  139.84  169.94  140.37
  184.94  139.65  209.93  140.29  354.88   139.5  439.85  139.81  479.84  138.95
  664.77  139.79  719.75  138.92  784.73  139.48  814.72  138.61  859.71  139.64
   965.1  139.59 1084.63  138.47 1114.62  139.05 1149.61   137.7 1429.51  140.73
  1675.5  138.89 1712.59  138.42 1846.65  140.41 1871.47  139.35 1886.68  134.02
 1894.07   137.5 1909.51  138.57 1933.49   138.1 1943.09  136.96 1957.48  137.12
#Mann= 5 ,-1 , 0
       0     .07       0   965.1     .15       0  1675.5     .07       0
 1871.47     .04       0 1909.51     .07       0
#XS Ineff= 2 ,-1
       0 1829.14   136.5 1909.51 1957.48  138.57
Permanent Ineff=
       F       F
Bank Sta=1871.47,1909.51
XS Rating Curve= 0 ,0
Exp/Cntr=0.3,0.1

Type RM Length L Ch R = 1 ,13699.69,51.47,50.91,50.92
XS GIS Cut Line= 4
2987931.8441991113860514.59672592987923.6729556213859101.7101159
 2987969.850028613858662.39012842987969.9500940313858569.1898555
#Sta/Elev= 30
       0  141.04  119.82  139.63  174.74  140.45   269.6  139.73  364.46  139.71
  414.39  139.07  429.36  139.49  464.31   139.2  484.28  139.69  574.15  139.88
  688.98  139.03  986.16  139.56 1178.26  137.87 1308.07  139.24 1541.96  140.56
 1551.89  140.13 1621.37  140.31 1662.96  139.17 1675.97   138.5 1700.79  138.56
 1735.53  139.28 1844.72  140.13 1859.84  139.84 1864.14  138.78 1875.87  134.21
 1884.08  137.96  1898.8  138.49 1918.42  138.06 1933.14  136.43 1947.85  137.12
#Mann= 5 ,-1 , 0
       0     .07       0  986.16     .15       0 1662.96     .07       0
 1859.84     .04       0  1898.8     .07       0
#XS Ineff= 2 ,-1
       0  1774.9   136.5  1898.8 1947.85  138.49
Permanent Ineff=
       F       F
Bank Sta=1859.84,1898.8
XS Rating Curve= 0 ,0
Exp/Cntr=0.3,0.1

Type RM Length L Ch R = 1 ,13648.78,48.51,49.03,49.22
XS GIS Cut Line= 5
2987965.5708376913860499.72569262987957.5226254513859119.3721541
 2988014.137669713858810.29567252988020.7800448513858665.0899262
2988020.8000579513858572.9099924
#Sta/Elev= 30
       0  140.84   44.85  140.58   94.68  139.29  224.25  140.04  468.43  139.31
   478.4  140.06  622.91  139.76  672.75  139.22   687.7  138.46  707.63  139.09
  762.45  138.63  787.36  139.45  946.83   139.8  986.69  139.07 1010.74  139.69
 1021.58  139.04 1215.93   138.2 1425.27  139.52 1648.47   139.3 1684.62  138.72
  1791.5  139.94 1846.09  139.89 1850.92  138.76  1862.9  134.09 1869.92  137.25
 1873.92  137.93 1893.32  138.37 1907.88  137.71 1917.58  136.42 1932.14  137.15
#Mann= 5 ,-1 , 0
       0     .07       0 1010.74     .15       0 1648.47     .07       0
 1846.09     .04       0 1893.32     .07       0
#XS Ineff= 2 ,-1
       0 1708.85  137.57 1893.32 1932.14  138.37
Permanent Ineff=
       F       F
Bank Sta=1846.09,1893.32
XS Rating Curve= 0 ,0
Exp/Cntr=0.3,0.1

Type RM Length L Ch R = 1 ,13599.75,727.91,696.37,695.83
XS GIS Cut Line= 5
2988000.9214887813860484.13878152987971.8834891213859126.8652494
2988060.0424335313858809.41280032988069.1798824413858670.1200999
2988071.5401139413858571.3899824
#Sta/Elev= 30
       0  140.46   49.91  139.45   99.82  139.91  329.41  139.49  374.33  139.84
  399.29  139.24  419.25   139.6  439.22  138.95  454.19  139.79  554.01   139.9
   618.9  139.63  688.77  138.19  778.61  139.36  833.52  139.02  933.34  139.79
 1018.27  139.24 1227.82  138.36  1347.6  139.42 1637.05  139.05 1647.12  138.54
 1662.09  139.05 1741.89  139.34 1796.73  140.16 1836.13  139.84 1853.92  134.04
 1861.21  137.71 1880.96  138.47 1895.78   137.8 1905.65   136.6  1925.4  137.05
#Mann= 5 ,-1 , 0
       0     .07       0 1018.27     .15       0 1637.05     .07       0
 1836.13     .04       0 1880.96     .07       0
#XS Ineff= 2 ,-1
       0  1660.5  137.57 1880.96  1925.4  138.47
Permanent Ineff=
       F       F
Bank Sta=1836.13,1880.96
XS Rating Curve= 0 ,0
Exp/Cntr=0.3,0.1

Type RM Length L Ch R = 1 ,12903.38,76.11,77.81,78
XS GIS Cut Line= 5
2988659.9677428613860266.10509682988756.6801478613858902.5198975
2988763.18997736 13858761.4001012988765.3599205313858662.6201148
2988766.4501414413858611.5998757
#Sta/Elev= 30
       0   139.9  244.47  139.34  289.37  139.89  379.17  138.95  454.01  139.87
  598.69  140.21  668.54  140.22  698.47   139.5  828.19  140.68  858.12  138.74
  883.07  139.58  967.88  139.16 1342.07  139.65 1376.76  139.18 1391.37  137.15
 1410.86  136.54 1435.21  137.48 1444.96  136.97 1479.06  137.81 1493.67     137
 1532.98  137.84 1547.81   136.9 1577.45  136.78 1590.62  137.68 1598.04  134.25
 1602.21  133.82 1604.95  134.27 1611.73  137.35 1625.65  138.11 1658.12  137.31
#Mann= 3 ,-1 , 0
       0     .07       0 1590.62     .04       0 1625.65     .07       0
#XS Ineff= 2 ,-1
       0 1501.03  137.57 1625.65 1658.12  138.11
Permanent Ineff=
       F       F
Bank Sta=1590.62,1625.65
XS Rating Curve= 0 ,0
Exp/Cntr=0.5,0.3

Type RM Length L Ch R = 1 ,12825.57,30,30.02,30
BEGIN DESCRIPTION:
Upstream Section - ACCESS RD #1
END DESCRIPTION:
XS GIS Cut Line= 2
2988774.6653481113860275.19136482988845.4493272813858612.4922623
#Sta/Elev= 30
       0  140.82   14.99  139.67  134.94  139.88  169.92  138.93   214.9  139.86
  459.78  139.97  724.65  139.71  754.64  139.14  779.63  139.81  924.56  140.54
 1019.51  139.46 1114.47  139.25 1144.45   139.9 1184.44  139.26 1209.42  139.72
 1364.35  139.42 1394.34  137.65 1419.33  137.51 1459.31  138.13  1474.3  137.32
 1524.28  137.27 1544.27  137.99 1579.25  136.91 1595.98   137.6 1603.31   134.1
 1607.44  133.79 1610.25  134.18 1619.23  137.72 1634.22  138.13 1664.21  137.59
#Mann= 3 ,-1 , 0
       0     .07       0 1595.98     .04       0 1634.22     .07       0
#XS Ineff= 3 ,-1
       0 1601.35  137.02 1613.04 1634.22  137.57 1634.22 1664.21  138.13
Permanent Ineff=
       F       F       F
Bank Sta=1595.98,1634.22
XS Rating Curve= 0 ,0
Exp/Cntr=0.5,0.3

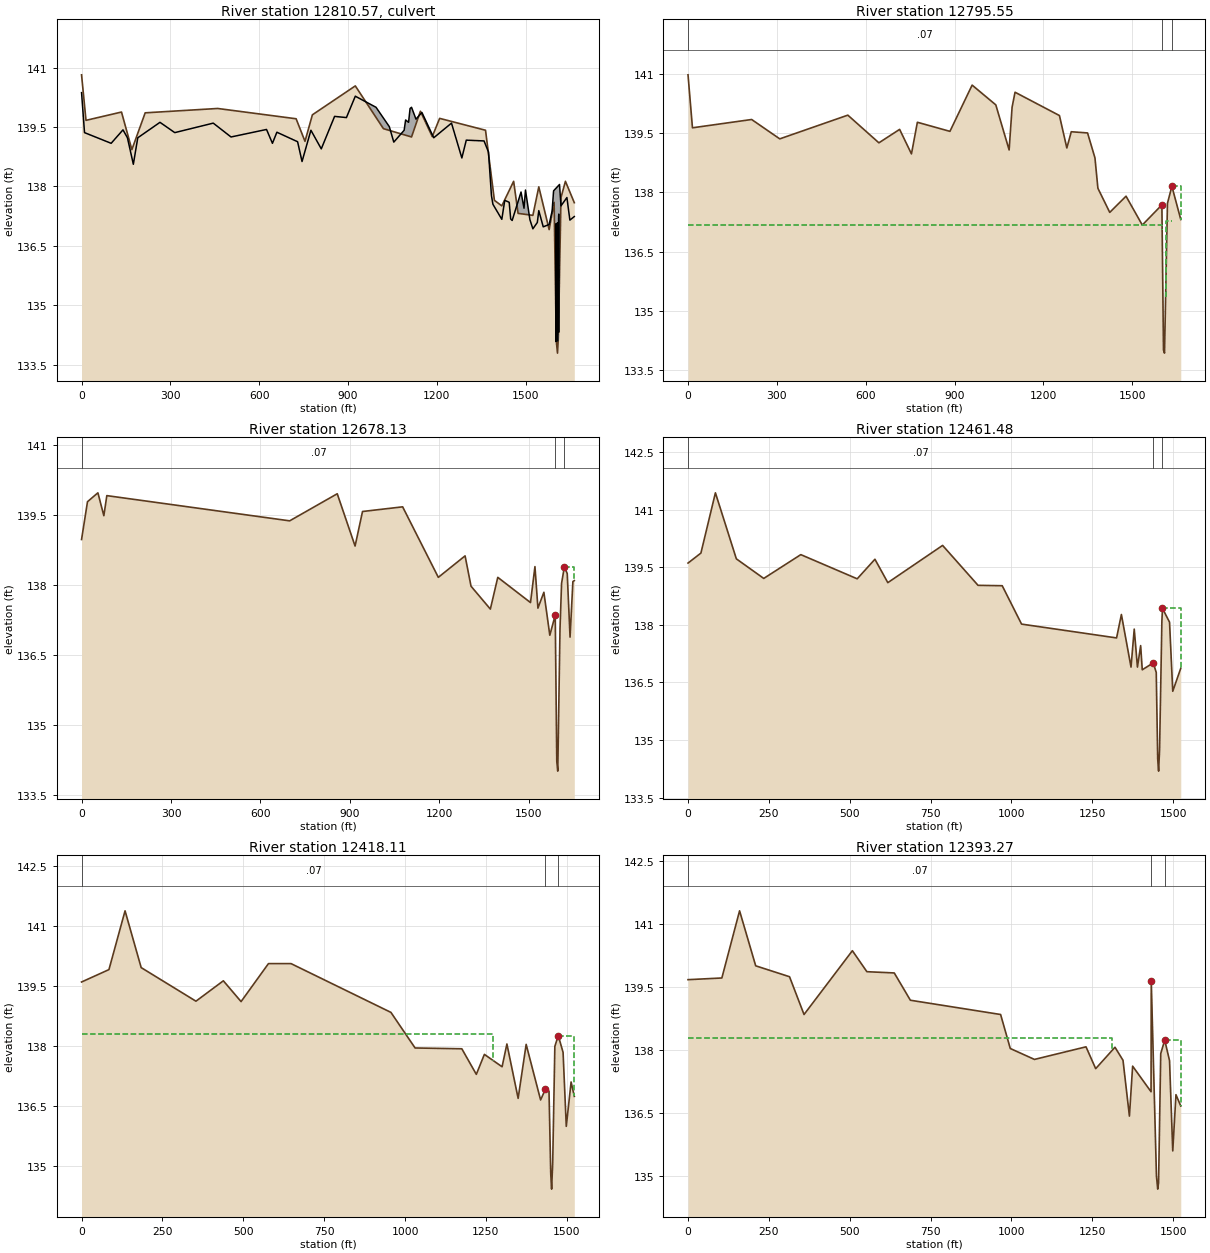
Type RM Length L Ch R = 2 ,12810.57,,,
BEGIN DESCRIPTION:
ACCESS RD #1
END DESCRIPTION:
Node Name=ACCESS RD #1
Bridge Culvert--1,0,-1,-1, 0
Deck Dist Width WeirC Skew NumUp NumDn MinLoCord MaxHiCord MaxSubmerge Is_Ogee
6,16,2.6,0, 60, 60, , , 0.98, 0, 0,0,,
       0      10   99.95  139.93  154.93  174.92  189.91  264.87  314.85  444.79
  504.76   624.7  644.69  659.69  729.65  744.65  774.63  809.61  854.59  894.57
  924.56  994.53  1039.5  1054.5 1089.48 1094.48 1104.47 1109.47 1114.47 1129.46
 1149.45 1189.43  1249.4 1284.38 1299.38 1359.35 1374.34 1384.34 1389.33 1419.32
 1429.31 1444.31  1449.3  1454.3 1484.29 1494.28 1499.28 1514.27 1524.27 1539.26
 1544.26 1559.25 1579.24 1589.24 1594.23 1614.22 1619.22 1639.21 1649.21  1664.2
  140.37  139.36  139.09  139.43  139.23  138.56  139.23  139.62  139.36   139.6
  139.25  139.44  139.09  139.37  139.13  138.63  139.42  138.95  139.77  139.74
  140.28     140  139.51  139.12  139.42  139.68  139.62  139.97     140   139.7
  139.87  139.23   139.6  138.72  139.17  139.15  138.87  137.77  137.55  137.17
  137.65   137.6  137.18  137.14  137.86  137.45  137.91  137.16  136.93  137.09
  137.39  136.98  137.04  137.38  137.89  138.05  137.51  137.72  137.15  137.24
                                                                                
                                                                                
                                                                                
                                                                                
                                                                                
                                                                                
       0      10   99.95  139.93  154.93  174.92  189.91  264.87  314.85  444.79
  504.76   624.7  644.69  659.69  729.65  744.65  774.63  809.61  854.59  894.57
  924.56  994.53  1039.5  1054.5 1089.48 1094.48 1104.47 1109.47 1114.47 1129.46
 1149.45 1189.43  1249.4 1284.38 1299.38 1359.35 1374.34 1384.34 1389.33 1419.32
 1429.31 1444.31  1449.3  1454.3 1484.29 1494.28 1499.28 1514.27 1524.27 1539.26
 1544.26 1559.25 1579.24 1589.24 1594.23 1614.22 1619.22 1639.21 1649.21  1664.2
  140.37  139.36  139.09  139.43  139.23  138.56  139.23  139.62  139.36   139.6
  139.25  139.44  139.09  139.37  139.13  138.63  139.42  138.95  139.77  139.74
  140.28     140  139.51  139.12  139.42  139.68  139.62  139.97     140   139.7
  139.87  139.23   139.6  138.72  139.17  139.15  138.87  137.77  137.55  137.17
  137.65   137.6  137.18  137.14  137.86  137.45  137.91  137.16  136.93  137.09
  137.39  136.98  137.04  137.38  137.89  138.05  137.51  137.72  137.15  137.24
                                                                                
                                                                                
                                                                                
                                                                                
                                                                                
                                                                                
BR Coef=-1 , 0 , 0 ,, 0 ,,,0.8,-1,,0,
WSPro=,,,, 1 ,,,, 0 ,,,, 0 ,,,,-1 ,-1 ,-1 , 0 , 0 , 0 , 0 , 0
Culvert=1,3,,17,0.013,0.5,1,1,3,134.07,1602.84,134.05,1602.84,Culvert #1  , 0 ,5.5
Culvert Bottom n=0.013
Culvert=1,3,,17,0.013,0.5,1,1,3,134.09,1607.34,133.91,1607.34,Culvert #2  , 0 ,5.5
Culvert Bottom n=0.013
Culvert=1,3,,17,0.013,0.5,1,1,3,134.31,1611.54,134.24,1611.54,Culvert #3  , 0 ,5.5
Culvert Bottom n=0.013
BC Design=,, 0 ,, 0 ,,,,,,
BC Use User HTab Curves=0
BC User HTab FreeFlow(D)= 0

Type RM Length L Ch R = 1 ,12795.55,122.42,117.42,117.03
BEGIN DESCRIPTION:
Downstream Section - ACCESS RD #1
END DESCRIPTION:
XS GIS Cut Line= 2
2988804.6383852813860276.46760892988875.4223644413858613.7685065
#Sta/Elev= 30
       0  140.97   14.99  139.63   214.9  139.84  309.85  139.35  539.74  139.95
  644.69  139.25  714.66  139.59  754.64  138.97  774.63  139.77  884.58  139.54
  959.54  140.71  1039.5  140.21 1084.48  139.07 1094.48  140.15 1104.47  140.53
  1254.4  139.94 1279.39  139.12 1294.38  139.53 1349.36   139.5 1374.35  138.87
 1384.34   138.1 1424.32  137.49  1479.3   137.9 1534.27  137.17 1600.41  137.68
 1605.85  134.01  1609.3  133.93 1619.23  137.72 1634.22  138.15 1664.21  137.31
#Mann= 3 ,-1 , 0
       0     .07       0 1600.41     .04       0 1634.22     .07       0
#XS Ineff= 3 ,-1
       0 1601.34  137.17 1613.04 1634.22  137.27 1634.22 1664.21  138.15
Permanent Ineff=
       F       F       F
Bank Sta=1600.41,1634.22
XS Rating Curve= 0 ,0
Exp/Cntr=0.5,0.3

Type RM Length L Ch R = 1 ,12678.13,223.77,216.66,217.47
XS GIS Cut Line= 3
2988963.3283566113860270.68907722988990.2899168613858670.6801381
2988990.6898504513858618.4600982
#Sta/Elev= 30
       0  138.98   19.94  139.79   54.84  139.98   74.78  139.49   84.75  139.92
  697.92  139.38  857.45  139.96  917.27  138.84   942.2  139.58 1076.79  139.68
 1196.44  138.17 1286.17  138.63 1306.11  137.98 1370.92  137.49 1395.84  138.17
 1505.52  137.63 1520.47   138.4 1530.44  137.51 1550.38  137.85 1570.32  136.93
 1588.48  137.36 1593.69  134.23 1596.99  134.02  1604.5  137.07 1609.73  138.04
 1619.22   138.4 1628.72  138.25 1638.21  136.89 1647.71  138.08 1652.46   138.1
#Mann= 3 ,-1 , 0
       0     .07       0 1588.48     .04       0 1619.22     .07       0
#XS Ineff= 2 ,-1
       0 1473.74  137.27 1619.22 1652.46   138.4
Permanent Ineff=
       F       F
Bank Sta=1588.48,1619.22
XS Rating Curve= 0 ,0
Exp/Cntr=0.3,0.1

Type RM Length L Ch R = 1 ,12461.48,48.57,43.36,43.33
Node Name=T
XS GIS Cut Line= 3
2989140.9677651113860135.30647392989193.2074900313858851.1774805
2989212.1976095313858613.7875354
#Sta/Elev= 30
       0  139.61   39.85  139.87   84.68  141.44  149.44  139.72  234.12  139.21
   348.7  139.83  523.04   139.2  577.84  139.71  617.69   139.1  787.05  140.07
  896.64  139.03  971.36  139.02 1031.14  138.02 1324.88  137.66 1339.76  138.27
 1369.53   136.9 1379.46  137.89 1389.38   136.9  1399.3  137.46 1404.26  136.83
 1438.23  137.01 1447.52  136.76 1452.04   134.5 1454.79  134.19 1457.82  134.75
 1464.91  138.09 1466.79  138.43 1488.61  138.07 1498.53  136.27 1523.34  136.87
#Mann= 3 ,-1 , 0
       0     .07       0 1438.23     .04       0 1466.79     .07       0
#XS Ineff= 2 ,-1
       0 1208.71  137.27 1466.79 1523.34  138.43
Permanent Ineff=
       F       F
Bank Sta=1438.23,1466.79
XS Rating Curve= 0 ,0
Exp/Cntr=0.3,0.1

Type RM Length L Ch R = 1 ,12418.11,27.22,24.84,24.84
XS GIS Cut Line= 3
 2989184.479489113860134.59322082989236.7192140213858850.4642273
2989255.7093335213858613.0742822
#Sta/Elev= 30
       0  139.59   84.68   139.9   134.5  141.37  184.31  139.95  353.68  139.11
  438.36  139.62  493.15   139.1  577.84  140.05  647.58  140.05  956.42  138.83
 1031.14  137.94  1175.6  137.92 1220.43  137.28 1245.34  137.78 1300.07  137.47
 1314.96  138.04 1349.69  136.68 1374.49  138.03 1419.15  136.64 1434.13  136.91
 1445.11  136.86 1450.51  134.79 1453.17  134.41 1456.56  135.07 1463.18  137.98
 1473.72  138.25 1488.61  137.83 1498.53  135.98 1513.41  137.09 1523.34  136.73
#Mann= 3 ,-1 , 0
       0     .07       0 1434.13     .04       0 1473.72     .07       0
#XS Ineff= 2 ,-1
       0  1272.6  138.28 1473.72 1523.34  138.25
Permanent Ineff=
       F       F
Bank Sta=1434.13,1473.72
XS Rating Curve= 0 ,0
Exp/Cntr=0.3,0.1

Type RM Length L Ch R = 1 ,12393.27,64.32,59.97,59.57
XS GIS Cut Line= 3
2989209.4453184513860133.87996762989261.6850433613858849.7509742
2989280.67516287 13858612.361029
#Sta/Elev= 30
       0  139.68  104.61  139.72   159.4  141.32  209.22  140.01  313.83  139.75
  358.66  138.85   508.1  140.37  552.93  139.87  637.61  139.84  687.43  139.19
  966.38  138.85  996.27  138.04 1070.99  137.78 1230.39  138.08 1260.28  137.56
 1319.92  138.07 1344.73  137.76 1364.57  136.43 1374.49  137.62 1431.45  137.01
 1432.08  139.65 1448.16     135  1452.1  134.69 1454.67  134.84 1461.42  137.92
 1473.72  138.24 1488.61  137.75 1498.53   135.6 1508.45  136.94 1523.34  136.67
#Mann= 3 ,-1 , 0
       0     .07       0 1432.08     .04       0 1473.72     .07       0
#XS Ineff= 2 ,-1
       0 1310.47  138.28 1473.72 1523.34  138.24
Permanent Ineff=
       F       F
Bank Sta=1432.08,1473.72
XS Rating Curve= 0 ,0
Exp/Cntr=0.5,0.3

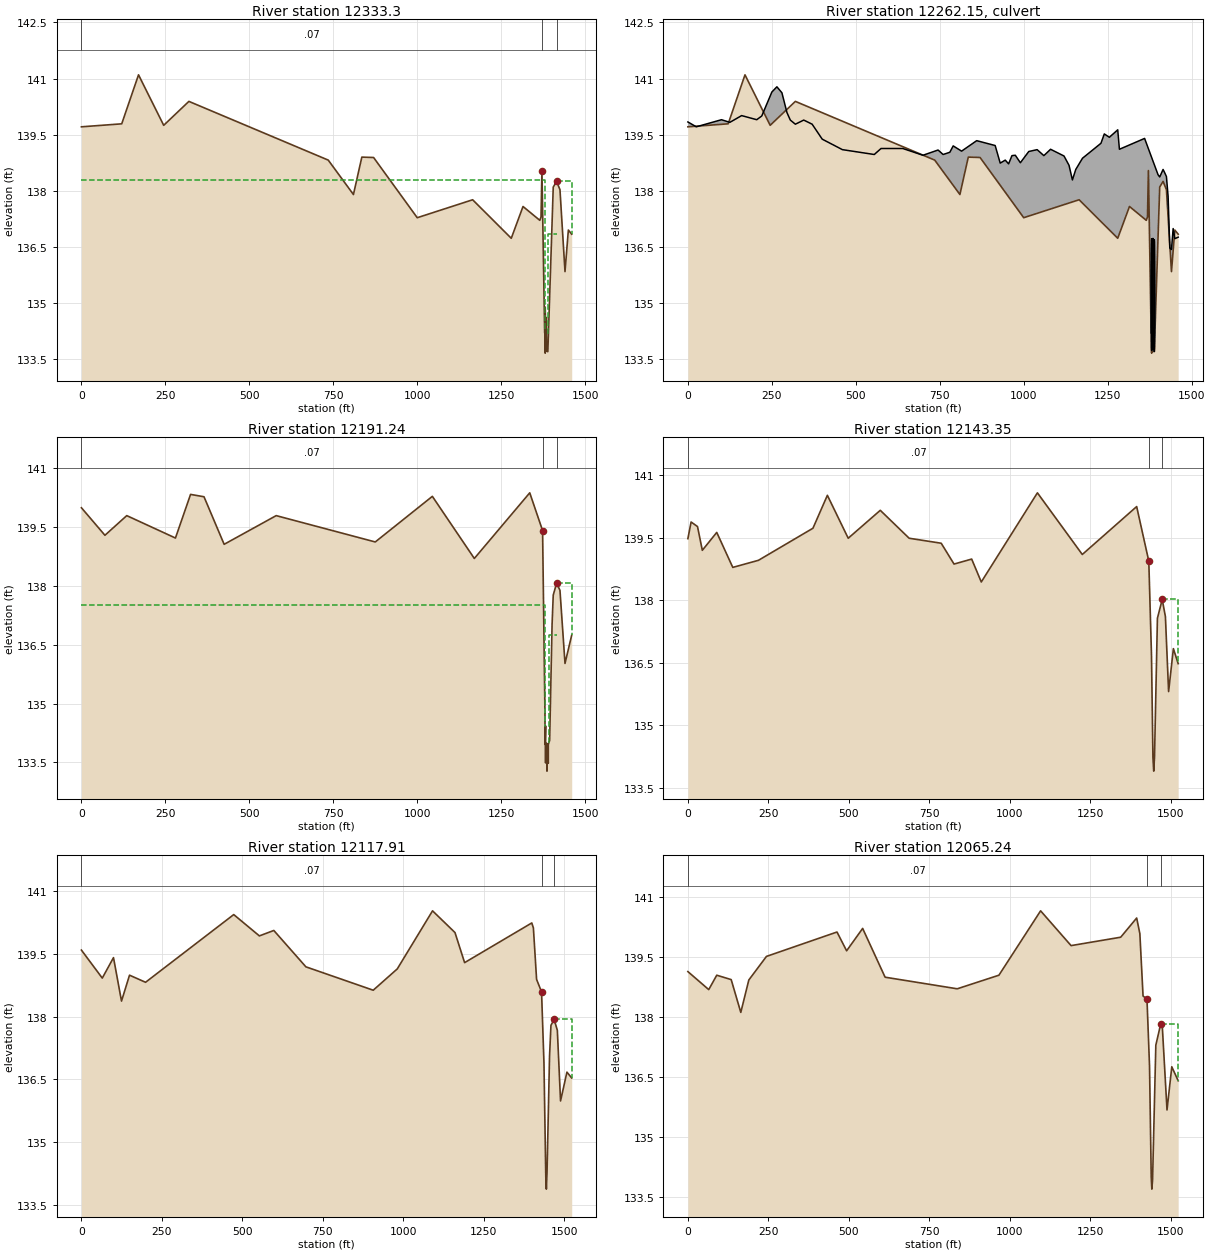
Type RM Length L Ch R = 1 ,12333.3 ,143.43,142.06,141.72
BEGIN DESCRIPTION:
Upstream Section - MORTON CREEK RANCH RD
END DESCRIPTION:
XS GIS Cut Line= 2
2989270.9333844513860075.89615972989337.9903369413858617.4371344
#Sta/Elev= 30
       0  139.71     120  139.79     170   141.1     245  139.75     320  140.39
     735  138.82     810   137.9     835   138.9     870  138.89    1000  137.28
    1165  137.76    1280  136.73    1315  137.58    1365  137.21 1368.59   137.3
 1371.32  138.54 1379.43   134.2 1380.89  134.22 1380.93  133.66 1381.02  134.89
 1382.31  134.21 1384.76  134.61  1384.9  133.71 1388.86   133.7    1405   138.1
    1415  138.25    1425  138.03    1440  135.84    1450  136.95    1460  136.84
#Mann= 3 ,-1 , 0
       0     .07       0 1371.32     .04       0    1415     .07       0
#XS Ineff= 3 ,-1
       0  1379.3  138.28  1390.6    1415  136.85    1415    1460  138.25
Permanent Ineff=
       F       F       F
Bank Sta=1371.32,1415
XS Rating Curve= 0 ,0
Exp/Cntr=0.5,0.3

Type RM Length L Ch R = 2 ,12262.15,,,
BEGIN DESCRIPTION:
MORTON CREEK RANCH RD
END DESCRIPTION:
Node Name=MORTON CRK RANCH
Bridge Culvert--1,0,-1,-1, 0
Deck Dist Width WeirC Skew NumUp NumDn MinLoCord MaxHiCord MaxSubmerge Is_Ogee
49,42,2.6,0, 60, 60, , , 0.98, 0, 4,4,,
       0      25     100     125     160     205     220     250     265     280
     295     305     320     345     370     400     460     555     575     640
     700     745     760     780     790     815     860     915     930     945
     955     965     975     990    1015    1040    1060    1080    1120    1135
    1145    1155    1175    1230    1240    1255    1280    1285    1360    1400
    1405    1415    1420    1425    1430    1435    1440    1445    1450    1460
  139.84  139.71   139.9  139.83  140.01   139.9     140  140.64  140.78  140.62
  140.09  139.89  139.78  139.89  139.78  139.38   139.1  138.97  139.13  139.13
  138.95  139.09  138.97  139.03   139.2  139.06  139.34  139.21  138.74  138.82
  138.72  138.94  138.95  138.75  139.05   139.1  138.94  139.11  138.93  138.68
  138.29  138.57  138.87  139.27  139.52  139.43  139.63  139.11   139.4  138.43
  138.37  138.57  138.48  138.38  137.85  136.47  136.43  136.99  136.72  136.76
       0       0       0       0       0       0       0       0       0       0
       0       0       0       0       0       0       0       0       0       0
       0       0       0       0       0       0       0       0       0       0
       0       0       0       0       0       0       0       0       0       0
       0       0       0       0       0       0       0       0       0       0
       0       0       0       0       0       0       0       0       0       0
       0      25     100     125     160     205     220     250     265     280
     295     305     320     345     370     400     460     555     575     640
     700     745     760     780     790     815     860     915     930     945
     955     965     975     990    1015    1040    1060    1080    1120    1135
    1145    1155    1175    1230    1240    1255    1280    1285    1360    1400
    1405    1415    1420    1425    1430    1435    1440    1445    1450    1460
  139.84  139.71   139.9  139.83  140.01   139.9     140  140.64  140.78  140.62
  140.09  139.89  139.78  139.89  139.78  139.38   139.1  138.97  139.13  139.13
  138.95  139.09  138.97  139.03   139.2  139.06  139.34  139.21  138.74  138.82
  138.72  138.94  138.95  138.75  139.05   139.1  138.94  139.11  138.93  138.68
  138.29  138.57  138.87  139.27  139.52  139.43  139.63  139.11   139.4  138.43
  138.37  138.57  138.48  138.38  137.85  136.47  136.43  136.99  136.72  136.76
       0       0       0       0       0       0       0       0       0       0
       0       0       0       0       0       0       0       0       0       0
       0       0       0       0       0       0       0       0       0       0
       0       0       0       0       0       0       0       0       0       0
       0       0       0       0       0       0       0       0       0       0
       0       0       0       0       0       0       0       0       0       0
BR Coef=-1 , 0 , 0 ,, 0 ,,,0.8,-1,,0,
WSPro=,,,, 1 ,,,, 0 ,,,, 0 ,,,,-1 ,-1 ,-1 , 0 , 0 , 0 , 0 , 0
Culvert=1,3,,101,0.013,0.7,1,1,1,133.73,1380.8,133.51,1381.98,Culvert #1  , 0 ,19.5
Culvert Bottom n=0.013
Culvert=1,3,,101,0.013,0.7,1,1,1,133.74,1384.87,133.57,1386.26,Culvert #2  , 0 ,19.5
Culvert Bottom n=0.013
Culvert=1,3,,101,0.013,0.7,1,1,1,133.7,1389.1,133.55,1390.29,Culvert #3  , 0 ,19.5
Culvert Bottom n=0.013
BC Design=,, 0 ,, 0 ,,,,,,
BC Use User HTab Curves=0
BC User HTab FreeFlow(D)= 0

Type RM Length L Ch R = 1 ,12191.24,47.03,47.89,48.23
BEGIN DESCRIPTION:
Downstream Section - MORTON CREEK RANCH RD
END DESCRIPTION:
XS GIS Cut Line= 2
2989412.4967496113860082.40500492989479.5537021213858623.9459796
#Sta/Elev= 30
       0  139.98      70  139.28     135  139.78     280  139.21     325  140.32
     365  140.26     425  139.05     580  139.78     875  139.11    1045  140.27
    1170  138.69    1335  140.36 1373.25   139.4  1380.4  134.68 1380.63  133.96
 1382.16  134.43  1382.2  133.49 1382.24     134 1386.25  133.95 1386.31  133.28
 1387.78  133.98 1390.15  133.48 1390.29  133.96 1394.26  134.06 1401.54  137.02
    1405  137.76    1415  138.06    1425  137.88    1440  136.02    1460  136.74
#Mann= 3 ,-1 , 0
       0     .07       0 1373.25     .04       0    1415     .07       0
#XS Ineff= 3 ,-1
       0 1380.49   137.5 1391.79    1415  136.75    1415    1460  138.06
Permanent Ineff=
       F       F       F
Bank Sta=1373.25,1415
XS Rating Curve= 0 ,0
Exp/Cntr=0.5,0.3

Type RM Length L Ch R = 1 ,12143.35,25.44,25.44,25.45
XS GIS Cut Line= 3
2989459.10262753 13860139.5863212989511.3423524513858855.4573276
2989530.3324719413858618.0673824
#Sta/Elev= 30
       0  139.48    9.96  139.88   29.89  139.77   44.83   139.2   89.66  139.63
  139.48  138.79  219.18  138.96  388.55  139.73  433.38  140.52  498.14  139.49
  597.76  140.16  687.43  139.49  787.05  139.37  826.91  138.87   881.7  138.99
  911.59  138.44 1085.94  140.58 1225.41   139.1 1394.34  140.25 1432.02  138.94
 1440.37  136.69 1444.93  134.22 1447.39   133.9  1449.8  134.24 1458.84  137.57
 1473.72  138.02 1483.65  137.61 1493.57  135.81 1508.45  136.84 1523.34  136.48
#Mann= 3 ,-1 , 0
       0     .07       0 1432.02     .04       0 1473.72     .07       0
#XS Ineff= 2 ,-1
       0 1351.11   137.5 1473.72 1523.34  138.02
Permanent Ineff=
       F       F
Bank Sta=1432.02,1473.72
XS Rating Curve= 0 ,0
Exp/Cntr=0.3,0.1

Type RM Length L Ch R = 1 ,12117.91,52.59,52.67,52.6
Node Name=S
XS GIS Cut Line= 3
2989484.7817100313860137.44656152989537.0214349513858853.3175681
2989556.0115544513858615.9276229
#Sta/Elev= 30
       0  139.59   64.76  138.92   99.63  139.41  124.53  138.37  149.44  138.99
  199.25  138.82  473.23  140.44  552.93  139.93  597.76  140.06  697.39  139.19
  906.61  138.63  981.33  139.14 1090.92  140.53 1160.66  140.01 1190.54  139.29
  1399.3  140.24 1404.26  140.12 1414.19  138.89  1429.6  138.59  1437.1  136.89
 1442.75  134.18 1444.55  133.87 1446.62  134.26 1454.39  137.04 1458.84  137.79
 1468.76  137.93 1478.68  137.67 1488.61  135.98 1508.45  136.67 1523.34  136.53
#Mann= 3 ,-1 , 0
       0     .07       0  1429.6     .04       0 1468.76     .07       0
#XS Ineff= 2 ,-1
       0  1316.5   137.5 1468.76 1523.34  137.93
Permanent Ineff=
       F       F
Bank Sta=1429.6,1468.76
XS Rating Curve= 0 ,0
Exp/Cntr=0.3,0.1

Type RM Length L Ch R = 1 ,12065.24,916.99,864.91,863.26
XS GIS Cut Line= 3
2989537.5663813713860136.73330832989589.8061062813858852.6043149
2989608.7962257713858615.2143698
#Sta/Elev= 30
       0  139.14   64.76  138.69   89.66  139.05   134.5  138.94  164.38  138.12
  189.29  138.93  244.09  139.52  463.27  140.13  493.15  139.66  542.97  140.22
  612.71     139  836.87  138.71  966.38  139.05  1095.9  140.66 1190.54  139.79
 1344.73     140 1394.34  140.48 1404.26  140.09 1414.19  138.53  1426.4  138.45
 1434.29  136.78 1439.58     134 1441.44   133.7 1443.74  133.93 1453.88   137.3
 1468.76  137.82 1473.72  137.81 1488.61  135.68 1503.49  136.76 1523.34  136.41
#Mann= 3 ,-1 , 0
       0     .07       0  1426.4     .04       0 1468.76     .07       0
#XS Ineff= 2 ,-1
       0 1246.84   137.5 1468.76 1523.34  137.82
Permanent Ineff=
       F       F
Bank Sta=1426.4,1468.76
XS Rating Curve= 0 ,0
Exp/Cntr=0.3,0.1

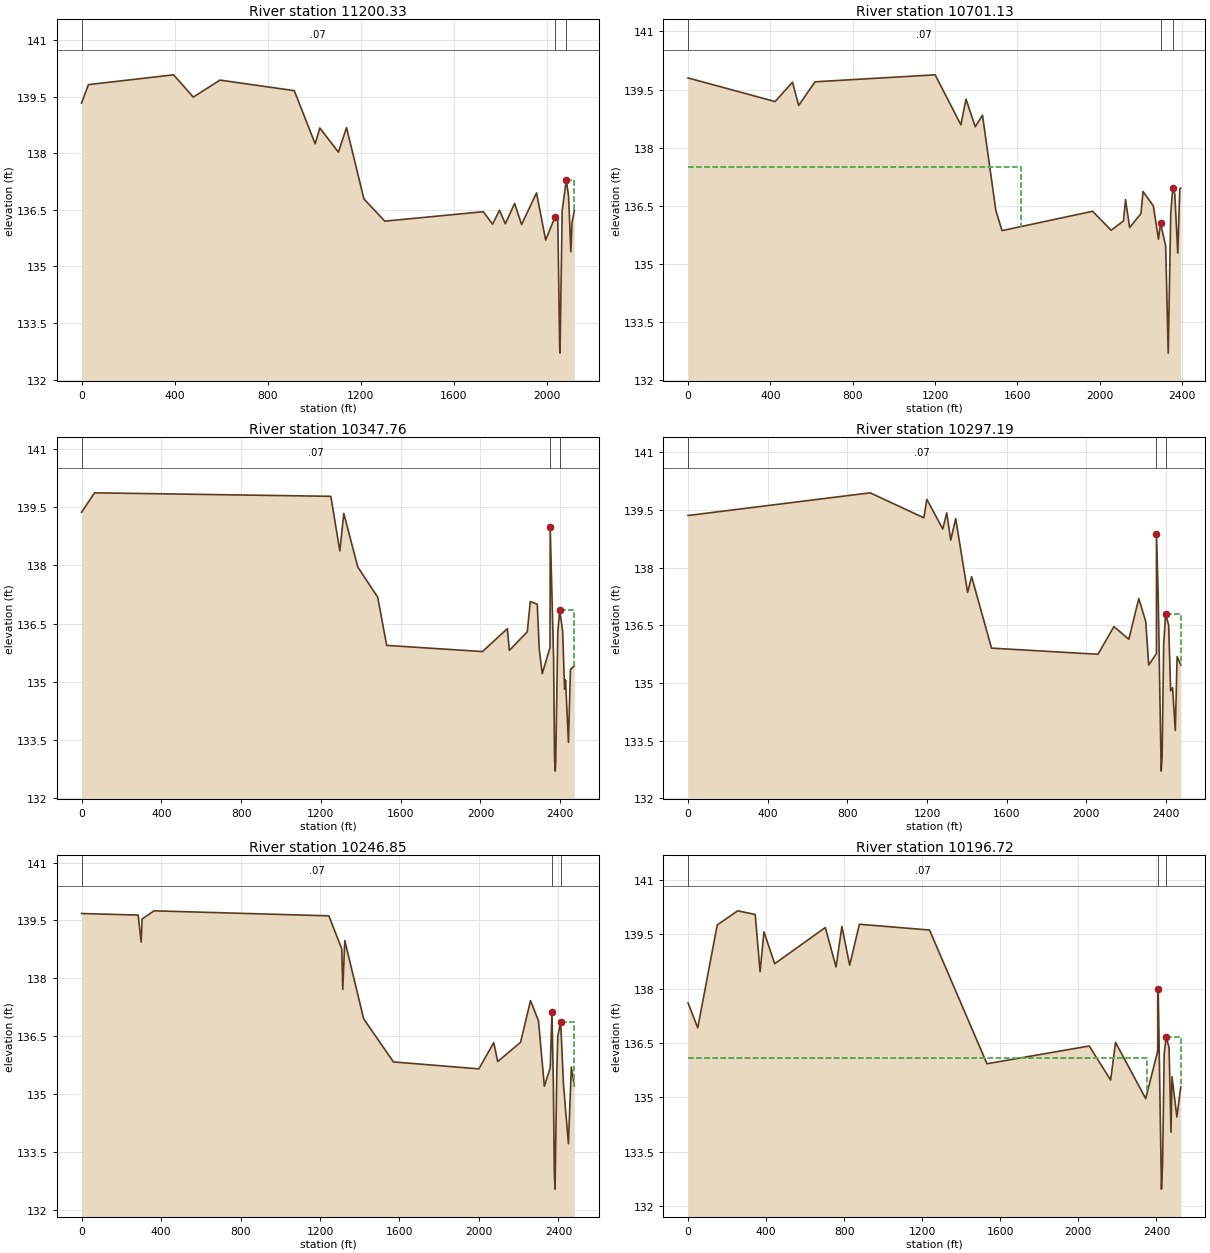
Type RM Length L Ch R = 1 ,11200.33,481.2,499.2,498.95
XS GIS Cut Line= 5
2989943.06917928 13860665.0222782990070.8901178513860490.9901458
2990440.2899696113859650.29005552990465.7600630213858873.2899691
2990465.7600630213858666.4399891
#Sta/Elev= 30
       0  139.33   29.44  139.82  395.59  140.08  480.43  139.49  595.22  139.94
  914.62  139.66 1004.45  138.25 1024.41  138.67 1104.26  138.03 1139.19  138.68
 1213.94  136.79 1303.64   136.2 1727.23  136.45  1767.1  136.12    1797  136.49
 1821.92  136.13 1861.79  136.67 1891.69  136.11 1955.95  136.95 1995.34   135.7
 2034.74   136.3  2047.5  136.24 2055.54  132.85 2056.94   132.7 2066.37  136.48
 2083.99  137.29 2093.84  136.86 2103.69  135.39 2108.62  136.16 2118.47  136.48
#Mann= 3 ,-1 , 0
       0     .07       0 2034.74     .04       0 2083.99     .07       0
#XS Ineff= 2 ,-1
       0  835.07   137.5 2083.99 2118.47  137.29
Permanent Ineff=
       F       F
Bank Sta=2034.74,2083.99
XS Rating Curve= 0 ,0
Exp/Cntr=0.3,0.1

Type RM Length L Ch R = 1 ,10701.13,358.18,353.38,352.71
XS GIS Cut Line= 5
2990546.3484845313861022.20069752990682.2100894513860728.9801553
2990865.2300646213859989.29003372990964.3601156913858738.6701596
2990964.36011569 13858685.290017
#Sta/Elev= 30
       0   139.8  422.77  139.19  507.44  139.69  537.32  139.09  617.01   139.7
 1200.12  139.88 1325.08  138.59 1350.07  139.25 1395.05  138.54 1430.04  138.84
 1495.01  136.38    1525  135.86 1964.85  136.36 2054.81  135.87 2114.79  136.11
 2124.79  136.66 2144.78  135.94 2199.76   136.3 2209.76  136.87 2259.74   136.5
 2284.73  135.64 2294.73  136.05 2319.72  135.47 2332.14   132.7 2344.57  136.33
 2354.27  136.95 2363.98  136.81 2378.53  135.28 2388.24  136.94 2393.09  136.96
#Mann= 3 ,-1 , 0
       0     .07       0 2294.73     .04       0 2354.27     .07       0
#XS Ineff= 2 ,-1
       0  1618.3   137.5 2354.27 2393.09  136.95
Permanent Ineff=
       F       F
Bank Sta=2294.73,2354.27
XS Rating Curve= 0 ,0
Exp/Cntr=0.3,0.1

Type RM Length L Ch R = 1 ,10347.76,55.62,50.57,50.21
XS GIS Cut Line= 4
2991155.9670159413861127.65258642991314.1399279413858823.1998462
2991318.3899194413858706.49010592991319.9889976113858662.5758236
#Sta/Elev= 30
       0  139.37      65  139.87 1249.93  139.78 1294.93  138.37 1314.93  139.34
 1384.92  137.96 1484.92  137.18 1529.92  135.94 2009.89  135.78 2134.89  136.37
 2144.89  135.81 2234.88  136.29 2249.88  137.07 2284.88     137 2294.88  135.84
 2309.88  135.21 2348.99  135.89 2349.67  138.99 2366.76   135.6 2371.49  133.05
 2374.95   132.7 2377.39  132.94 2387.73  136.28 2397.47  136.84 2412.06  136.31
  2421.8  134.81 2426.66  135.05 2441.31  133.44 2451.07  135.32 2470.61  135.41
#Mann= 3 ,-1 , 0
       0     .07       0 2349.67     .04       0 2397.47     .07       0
#XS Ineff= 2 ,-1
       0 2113.92  136.08 2397.47 2470.61  136.84
Permanent Ineff=
       F       F
Bank Sta=2349.67,2397.47
XS Rating Curve= 0 ,0
Exp/Cntr=0.3,0.1

Type RM Length L Ch R = 1 ,10297.19,48.8,50.34,49.18
XS GIS Cut Line= 4
2991238.4189507813861133.99509332991367.0600976913858824.7900661
2991366.9298486113858709.82999422991366.8780114513858663.9754271
#Sta/Elev= 30
       0  139.36  914.12  139.95 1183.86   139.3 1198.85  139.78 1278.77  139.01
 1298.75  139.43 1318.74  138.72 1343.71  139.28 1403.65  137.36 1423.63  137.77
 1523.54  135.91 2058.02  135.75 2137.95  136.47 2212.88  136.14 2262.83   137.2
  2297.8   136.6 2312.78  135.47 2351.56  135.77 2351.57  138.89 2360.23  137.26
 2375.27  132.71 2379.95  133.08 2387.76  136.02 2397.75  136.79 2412.75  136.51
 2422.75   134.8 2432.33  134.88 2446.09  133.77 2455.26  135.69  2473.6  135.47
#Mann= 3 ,-1 , 0
       0     .07       0 2351.57     .04       0 2397.75     .07       0
#XS Ineff= 2 ,-1
       0 2184.79  136.08 2397.75  2473.6  136.79
Permanent Ineff=
       F       F
Bank Sta=2351.57,2397.75
XS Rating Curve= 0 ,0
Exp/Cntr=0.3,0.1

Type RM Length L Ch R = 1 ,10246.85,42.72,50.13,50.19
XS GIS Cut Line= 4
2991300.7862801113861142.45176942991414.4799503513858825.8901295
2991417.1298794413858710.07015122991418.1495624513858665.5059358
#Sta/Elev= 30
       0  139.68  284.92  139.64  299.92  138.94  304.91  139.54   364.9  139.75
 1244.65  139.62 1309.63  138.76 1314.63  137.71 1324.63  138.98  1419.6  136.95
 1569.56  135.83 1999.44  135.65 2074.41  136.33 2094.41  135.84 2209.38  136.34
 2259.36  137.42 2299.35   136.9    2329   135.2 2358.68  135.68  2367.4  137.13
 2374.32  135.28 2379.15  132.98 2382.81  132.53 2391.76  135.58 2396.58  136.49
 2411.06  136.87 2425.55  135.22 2450.06  133.71 2464.92   135.7 2479.78  135.21
#Mann= 3 ,-1 , 0
       0     .07       0  2367.4     .04       0 2411.06     .07       0
#XS Ineff= 2 ,-1
       0 2249.64  136.08 2411.06 2479.78  136.87
Permanent Ineff=
       F       F
Bank Sta=2367.4,2411.06
XS Rating Curve= 0 ,0
Exp/Cntr=0.3,0.1

Type RM Length L Ch R = 1 ,10196.72,84.63,46.43,46.42
XS GIS Cut Line= 4
2991406.3359377813861190.40967872991448.8709576913858935.6343326
2991464.8210570213858807.11785742991468.7931619413858667.1742396
#Sta/Elev= 30
       0  137.61   49.89  136.92  149.68  139.76  254.46  140.15  344.26  140.05
  369.21  138.47  389.17  139.57  444.05  138.69   703.5  139.69  758.38   138.6
  788.31  139.72  828.23  138.65  878.12  139.78 1237.35  139.62 1531.72  135.93
  2055.6  136.42 2165.37  135.48 2190.31  136.52 2344.83  134.97 2407.02  136.29
 2409.04  137.99 2425.61  132.47 2431.33  133.15 2439.67   136.2 2449.67  136.66
 2464.67  136.38 2474.67  134.04 2479.67  135.57 2504.67  134.46 2524.67  135.29
#Mann= 3 ,-1 , 0
       0     .07       0 2409.04     .04       0 2449.67     .07       0
#XS Ineff= 2 ,-1
       0 2351.46  136.08 2449.67 2524.67  136.66
Permanent Ineff=
       F       F
Bank Sta=2409.04,2449.67
XS Rating Curve= 0 ,0
Exp/Cntr=0.5,0.3