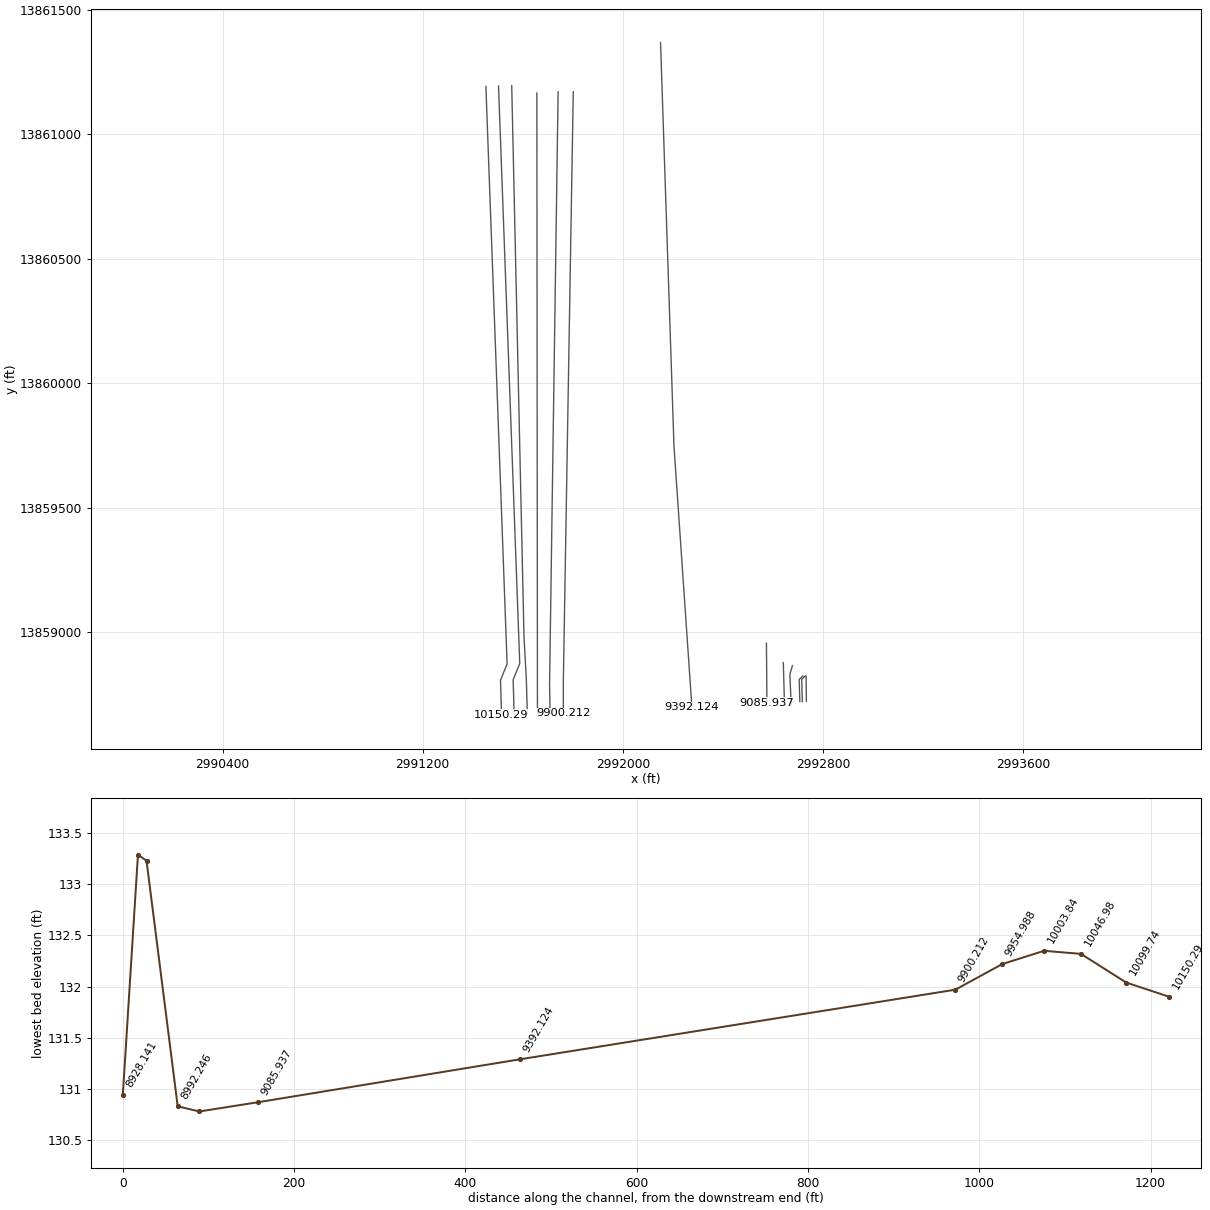
HEC-RAS study U101-07-00.prj: U101-07-00 2019 (Re-Study)

--- U101-07-00.g01 (geometry) --- (continued)

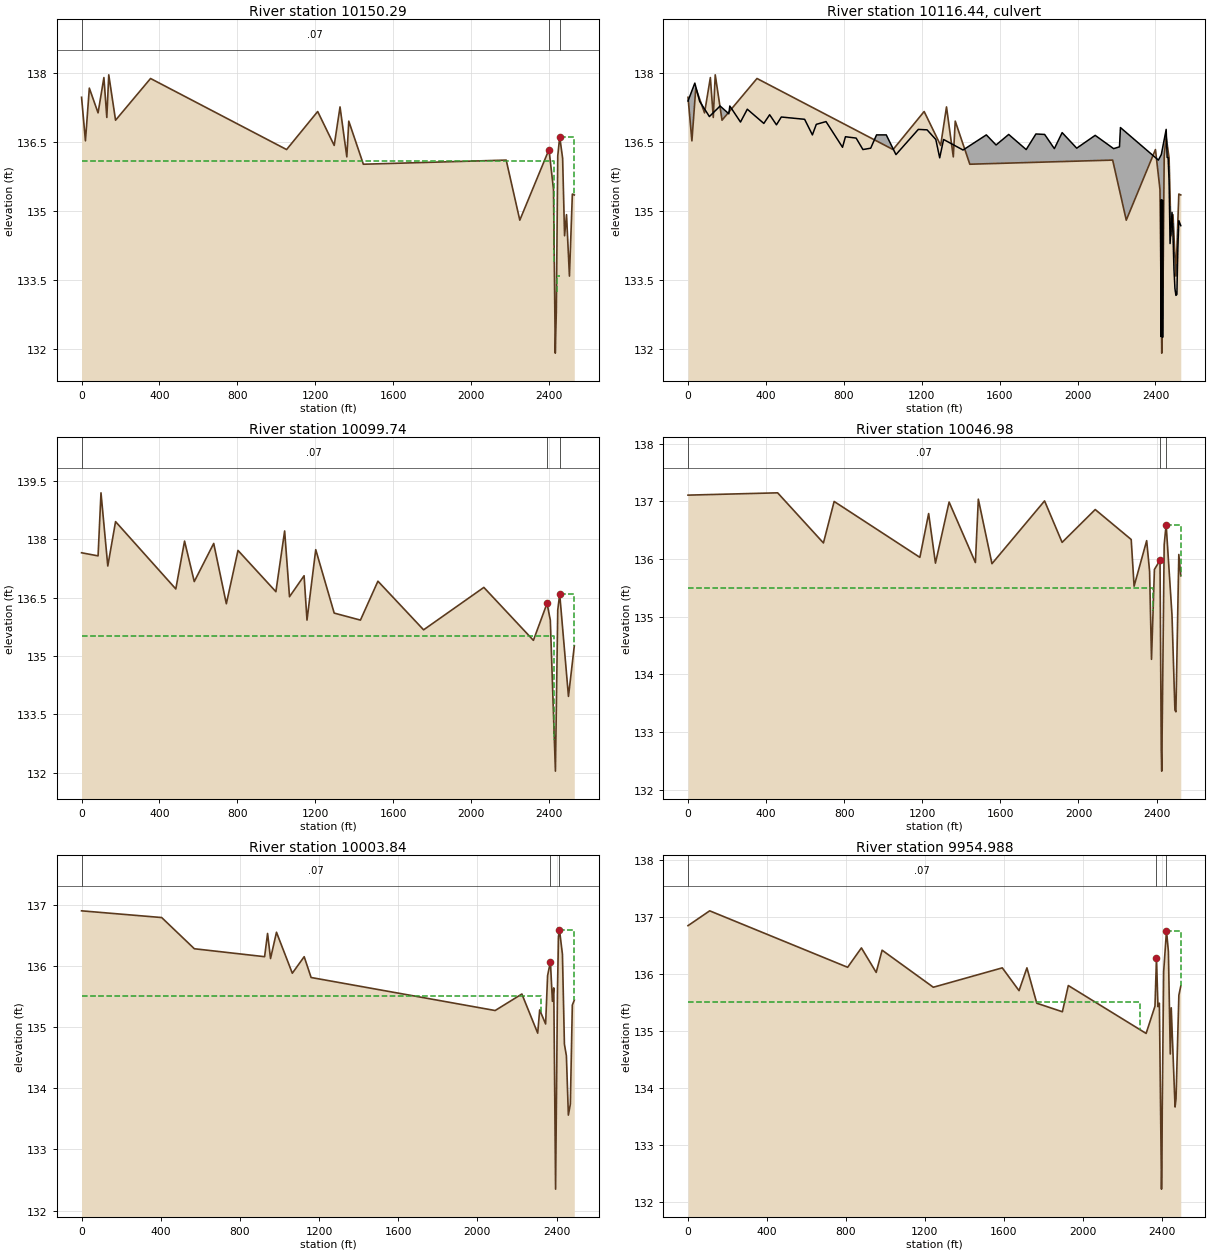
Type RM Length L Ch R = 1 ,10150.29,50.55,50.55,50.55
BEGIN DESCRIPTION:
Upstream Section - PEEK RD
END DESCRIPTION:
Node Name=R
XS GIS Cut Line= 4
2991452.7334827813861191.72660522991537.5863314413858873.2788143
2991511.2186020313858808.43478382991515.1907069413858668.4911661
#Sta/Elev= 30
       0  137.48   19.96  136.53   39.91  137.68   84.82  137.14  114.75  137.91
  129.72  137.04   139.7  137.97  174.62  136.98  354.24  137.89 1052.73  136.34
 1212.39  137.17 1297.21  136.43 1327.14  137.27 1362.07  136.18 1372.04  136.96
 1446.88  136.02 2180.31  136.11 2250.16   134.8 2400.01  136.34 2423.21  135.47
 2432.34   131.9 2437.67  132.81 2445.01   136.2 2455.01  136.62 2470.01  136.15
 2480.01  134.46 2490.01  134.92 2505.01  133.58 2520.01  135.37 2530.01  135.35
#Mann= 3 ,-1 , 0
       0     .07       0 2400.01     .04       0 2455.01     .07       0
#XS Ineff= 3 ,-1
       0 2427.38  136.08  2438.6 2455.01  133.58 2455.01 2530.01  136.62
Permanent Ineff=
       F       F       F
Bank Sta=2400.01,2455.01
XS Rating Curve= 0 ,0
Exp/Cntr=0.5,0.3

Type RM Length L Ch R = 2 ,10116.44,,,
BEGIN DESCRIPTION:
PEEK RD
END DESCRIPTION:
Node Name=PEEK RD
Bridge Culvert--1,0,-1,-1, 0
Deck Dist Width WeirC Skew NumUp NumDn MinLoCord MaxHiCord MaxSubmerge Is_Ogee
8,36.5,2.6,0, 60, 60, , , 0.98, 0, 1,1,,
       0   34.92   59.87  109.76  164.65  209.55  214.54  269.42  304.34  389.16
   419.1  454.02  478.97  598.71  638.62  658.58  708.47  793.29  808.26  863.14
  898.07  937.98  967.92 1017.81  1067.7 1182.45 1227.36 1272.26 1292.22 1312.17
 1411.96  1531.7 1581.59 1646.45 1736.26 1786.15 1831.06 1880.95 1920.86  1995.7
  2090.5 2185.29 2215.23 2220.22 2415.01 2430.01 2455.01 2460.01 2465.01 2470.01
 2475.01 2485.01 2490.01 2495.01 2500.01 2505.01 2510.01 2515.01 2520.01 2530.01
   137.4  137.79  137.39  137.06  137.29  137.12  137.29  136.94  137.22  136.91
   137.1  136.88  137.05     137  136.66  136.89  136.95  136.39  136.62  136.59
  136.34  136.37  136.66  136.66  136.23  136.78  136.77  136.56  136.16  136.56
  136.33  136.66  136.44  136.67  136.34  136.68  136.67  136.36  136.71  136.37
  136.65  136.36   136.4  136.82  136.11  136.23  136.78  136.17  136.16  135.66
  134.29  134.97   134.5  133.73  133.31  133.16  133.18  134.19  134.79  134.68
       0       0       0       0       0       0       0       0       0       0
       0       0       0       0       0       0       0       0       0       0
       0       0       0       0       0       0       0       0       0       0
       0       0       0       0       0       0       0       0       0       0
       0       0       0       0       0       0       0       0       0       0
       0       0       0       0       0       0       0       0       0       0
       0   34.92   59.87  109.76  164.65  209.55  214.54  269.42  304.34  389.16
   419.1  454.02  478.97  598.71  638.62  658.58  708.47  793.29  808.26  863.14
  898.07  937.98  967.92 1017.81  1067.7 1182.45 1227.36 1272.26 1292.22 1312.17
 1411.96  1531.7 1581.59 1646.45 1736.26 1786.15 1831.06 1880.95 1920.86  1995.7
  2090.5 2185.29 2215.23 2220.22 2415.01 2430.01 2455.01 2460.01 2465.01 2470.01
 2475.01 2485.01 2490.01 2495.01 2500.01 2505.01 2510.01 2515.01 2520.01 2530.01
   137.4  137.79  137.39  137.06  137.29  137.12  137.29  136.94  137.22  136.91
   137.1  136.88  137.05     137  136.66  136.89  136.95  136.39  136.62  136.59
  136.34  136.37  136.66  136.66  136.23  136.78  136.77  136.56  136.16  136.56
  136.33  136.66  136.44  136.67  136.34  136.68  136.67  136.36  136.71  136.37
  136.65  136.36   136.4  136.82  136.11  136.23  136.78  136.17  136.16  135.66
  134.29  134.97   134.5  133.73  133.31  133.16  133.18  134.19  134.79  134.68
       0       0       0       0       0       0       0       0       0       0
       0       0       0       0       0       0       0       0       0       0
       0       0       0       0       0       0       0       0       0       0
       0       0       0       0       0       0       0       0       0       0
       0       0       0       0       0       0       0       0       0       0
       0       0       0       0       0       0       0       0       0       0
BR Coef=-1 , 0 , 0 ,, 0 ,,,0.8,-1,,0,
WSPro=,,,, 1 ,,,, 0 ,,,, 0 ,,,,-1 ,-1 ,-1 , 0 , 0 , 0 , 0 , 0
Culvert=1,3,,42.5,0.013,0.5,1,1,3,132.25,2428.87,131.89,2429.12,Culvert #1  , 0 ,4
Culvert Bottom n=0.013
Culvert=1,3,,42.5,0.013,0.5,1,1,3,132.25,2432.95,131.75,2433.29,Culvert #2  , 0 ,4
Culvert Bottom n=0.013
Culvert=1,3,,42.5,0.013,0.5,1,1,3,132.24,2437.1,131.73,2437.44,Culvert #3  , 0 ,4
Culvert Bottom n=0.013
BC Design=,, 0 ,, 0 ,,,,,,
BC Use User HTab Curves=0
BC User HTab FreeFlow(D)= 0

Type RM Length L Ch R = 1 ,10099.74,21.69,52.76,52.76
BEGIN DESCRIPTION:
Downstream Section - PEEK RD
END DESCRIPTION:
XS GIS Cut Line= 4
2991503.2635654513861193.16065742991588.1164141113858874.7128665
2991561.7486846913858809.86883612991565.7207896113858669.9252184
#Sta/Elev= 30
       0  137.65   84.82  137.57   99.79  139.19  134.71  137.31  174.62  138.45
  483.96  136.72  528.86  137.95  578.75  136.91  678.54  137.89   743.4  136.34
  803.27  137.71  997.85  136.65 1042.75  138.21  1067.7  136.52 1142.54  137.06
 1157.51  135.92 1202.41  137.73 1297.21   136.1 1431.92  135.92 1521.72  136.92
 1756.22  135.67 2065.55  136.76 2320.01   135.4 2390.01  136.35 2406.81  135.92
 2433.01  132.04 2445.01  136.18 2455.01  136.59 2500.01  133.96 2530.01  135.26
#Mann= 3 ,-1 , 0
       0     .07       0 2390.01     .04       0 2455.01     .07       0
#XS Ineff= 3 ,-1
       0 2427.63   135.5 2438.94 2455.01  133.96 2455.01 2530.01  136.59
Permanent Ineff=
       F       F       F
Bank Sta=2390.01,2455.01
XS Rating Curve= 0 ,0
Exp/Cntr=0.5,0.3

Type RM Length L Ch R = 1 ,10046.98,54.73,43.14,42.87
Node Name=Q
XS GIS Cut Line= 4
 2991556.000664713861194.65737362991605.1301596213858979.5600978
2991614.4857839513858811.36555232991618.4578888613858671.4219345
#Sta/Elev= 30
       0  137.11   459.1  137.15  693.64  136.28  748.53     137 1187.66  136.03
 1232.58  136.79 1267.51  135.93 1337.37  136.99 1472.11  135.94 1487.08  137.04
 1556.94  135.92 1826.41  137.01 1916.23  136.29  2085.9  136.86 2270.15  136.34
 2285.01  135.53 2349.42  136.32 2364.28  135.79 2374.19  134.26  2389.1  135.82
 2417.74  135.98 2424.14  132.67 2426.55  132.32  2439.1  136.25  2449.1   136.6
  2479.1  135.03  2494.1  133.38  2499.1  133.35  2514.1  136.08  2524.1  135.71
#Mann= 3 ,-1 , 0
       0     .07       0 2417.74     .04       0  2449.1     .07       0
#XS Ineff= 2 ,-1
       0 2382.26   135.5  2449.1  2524.1   136.6
Permanent Ineff=
       F       F
Bank Sta=2417.74,2449.1
XS Rating Curve= 0 ,0
Exp/Cntr=0.3,0.1

Type RM Length L Ch R = 1 ,10003.84,52.41,48.85,49.02
XS GIS Cut Line= 2
2991656.5007917713861165.35493882991658.8715219513858675.7598523
#Sta/Elev= 30
       0   136.9  404.93  136.79  569.91  136.28  924.85  136.15  939.85  136.53
  954.84  136.12  984.84  136.55 1064.83  135.88 1124.82  136.15 1159.81  135.81
 2089.67  135.27 2224.65  135.54 2304.63   134.9 2314.63  135.28 2344.63  135.05
 2354.62  135.84 2368.82  136.07 2378.98  135.42 2385.82  135.64    2395  132.35
 2404.62  135.62 2409.61  136.47 2414.61  136.59 2429.61  136.19 2439.61  134.72
 2449.61  134.53 2459.61  133.56  2469.6  133.74  2479.6  135.36  2489.6  135.44
#Mann= 3 ,-1 , 0
       0     .07       0 2368.82     .04       0 2414.61     .07       0
#XS Ineff= 2 ,-1
       0 2320.36   135.5 2414.61  2489.6  136.59
Permanent Ineff=
       F       F
Bank Sta=2368.82,2414.61
XS Rating Curve= 0 ,0
Exp/Cntr=0.3,0.1

Type RM Length L Ch R = 1 ,9954.988,55.49,54.78,54.6
XS GIS Cut Line= 4
2991741.4382859513861170.01798722991707.2999027813858789.7901361
2991708.4301498513858727.32995922991709.3914340313858674.1998161
#Sta/Elev= 30
       0  136.84  109.79   137.1  808.46  136.11  878.33  136.45  953.19  136.02
  983.13  136.41 1242.64  135.76 1591.97   136.1 1676.81   135.7 1716.73   136.1
 1766.64  135.48 1896.39  135.33 1926.34  135.79 2320.58  134.95  2365.5  135.43
 2372.97  136.28 2380.47  135.42 2387.66  135.48  2398.4  132.22 2400.66  132.66
 2402.23  133.62  2409.3  136.03 2423.72  136.75 2433.33  136.39 2442.94  134.59
 2447.77   135.4 2467.09  133.66 2471.93   133.8 2486.42  135.62 2496.08  135.78
#Mann= 3 ,-1 , 0
       0     .07       0 2372.97     .04       0 2423.72     .07       0
#XS Ineff= 2 ,-1
       0 2289.47   135.5 2423.72 2496.08  136.75
Permanent Ineff=
       F       F
Bank Sta=2372.97,2423.72
XS Rating Curve= 0 ,0
Exp/Cntr=0.3,0.1

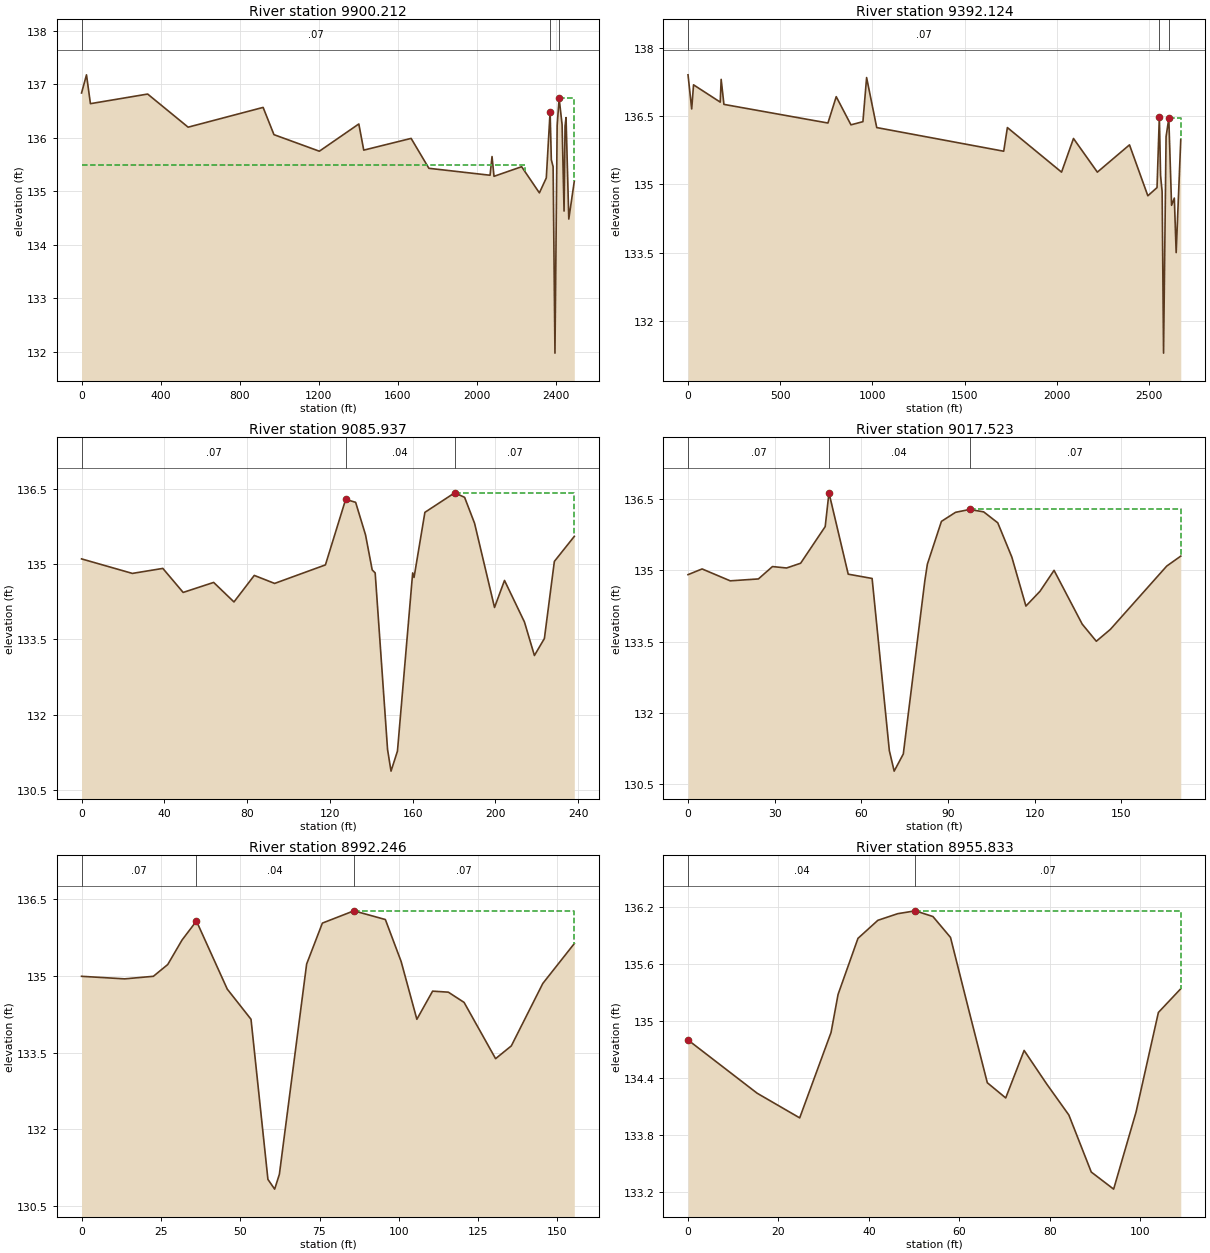
Type RM Length L Ch R = 1 ,9900.212,489.39,508.09,508.64
XS GIS Cut Line= 4
2991802.0588996113861170.01798722991762.3486771913858802.5903074
2991762.3486771913858717.68004412991762.3486771913858675.7805216
#Sta/Elev= 30
       0  136.84   24.98  137.18   44.96  136.64  334.68  136.82  539.49   136.2
  919.13  136.57  974.08  136.06 1203.86  135.75 1403.67  136.26 1428.65  135.77
 1668.42  135.99 1758.34  135.43 2068.05   135.3 2078.04  135.65 2088.03  135.28
  2227.9  135.46 2317.81  134.97 2352.78  135.25 2372.02  136.49 2378.22  135.59
 2387.25  135.46  2396.6  131.97 2407.72  136.23 2417.71  136.74 2432.69  136.25
 2442.68  134.63 2447.68  136.22 2452.67  136.38 2466.64  134.48 2494.57  135.19
#Mann= 3 ,-1 , 0
       0     .07       0 2372.02     .04       0 2417.71     .07       0
#XS Ineff= 2 ,-1
       0 2243.39   135.5 2417.71 2494.57  136.74
Permanent Ineff=
       F       F
Bank Sta=2372.02,2417.71
XS Rating Curve= 0 ,0
Exp/Cntr=0.3,0.1

Type RM Length L Ch R = 1 ,9392.124,337.77,306.19,305.24
XS GIS Cut Line= 5
2992150.9499341113861367.78005882992204.6899841113859746.6901252
2992268.2505525213858818.12734982992271.5881442713858769.3636678
 2992276.363397213858699.6036367
#Sta/Elev= 30
       0  137.41   19.96  136.66   29.94  137.19  174.67  136.81  179.67  137.31
  194.64  136.76  758.59  136.35   803.5  136.93  883.36  136.31  948.23  136.38
   968.2  137.35  1023.1  136.25 1711.57  135.73 1731.48  136.25 2025.14  135.27
 2089.84  136.01 2219.25  135.27 2393.44  135.87 2492.99  134.75 2542.76  134.93
 2555.31  136.49 2562.05  135.19 2570.43  134.84 2578.16  131.29 2591.81  136.05
 2606.58  136.45 2621.57  134.54 2636.55   134.7 2646.54   133.5 2671.51  135.99
#Mann= 3 ,-1 , 0
       0     .07       0 2555.31     .04       0 2606.58     .07       0
#XS Ineff= 2 ,-1
       0 2039.49  134.68 2606.58 2671.51  136.45
Permanent Ineff=
       F       F
Bank Sta=2555.31,2606.58
XS Rating Curve= 0 ,0
Exp/Cntr=0.3,0.1

Type RM Length L Ch R = 1 ,9085.937,96.18,68.41,68.44
XS GIS Cut Line= 4
2992574.3326175213858955.92169362992575.3585341113858828.2290356
 2992575.742719713858780.41121792992576.2459995313858717.7627211
#Sta/Elev= 30
       0  135.11   24.56  134.82   39.29  134.92   49.11  134.44   63.85  134.64
   73.67  134.25   83.49  134.78   93.32  134.62  117.87  134.99  127.67   136.3
  132.48  136.24  137.26  135.59  140.48  134.89  141.92  134.83  147.91   131.3
  149.58  130.87  152.69  131.27  160.04  134.83  160.71  134.74  165.95  136.04
  180.34  136.43  185.15  136.34  189.97  135.82  199.61  134.14  204.43  134.68
  214.07  133.85  218.89  133.18  223.71  133.52  228.53  135.06  238.17  135.56
#Mann= 3 ,-1 , 0
       0     .07       0  127.67     .04       0  180.34     .07       0
#XS Ineff= 1 ,-1
  180.34  238.17  136.43
Permanent Ineff=
       F
Bank Sta=127.67,180.34
XS Rating Curve= 0 ,0
Exp/Cntr=0.3,0.1

Type RM Length L Ch R = 1 ,9017.523,34.82,25.28,25.44
XS GIS Cut Line= 2
 2992641.858729213858878.51732092992646.4203998613858707.9884624
#Sta/Elev= 30
       0  134.91    4.87  135.03   14.62  134.78   24.37  134.82   29.24  135.08
   34.12  135.05   38.99  135.15   47.49  135.92    48.8  136.63   55.46  134.92
   63.73  134.83    69.7  131.21   71.37  130.78   74.53  131.14   81.98  134.78
   82.86  135.13   87.73  136.03   92.61  136.22   97.48  136.28  102.35  136.23
  107.23     136   112.1  135.28  116.98  134.25  121.85  134.56  126.72     135
  136.47  133.87  141.35  133.51  146.22  133.76  165.72  135.09  170.59   135.3
#Mann= 3 ,-1 , 0
       0     .07       0    48.8     .04       0   97.48     .07       0
#XS Ineff= 1 ,-1
   97.48  170.59  136.28
Permanent Ineff=
       F
Bank Sta=48.8,97.48
XS Rating Curve= 0 ,0
Exp/Cntr=0.3,0.1

Type RM Length L Ch R = 1 ,8992.246,43.96,36.41,36.25
BEGIN DESCRIPTION:
U/S of Confluence with U201-07-01
END DESCRIPTION:
XS GIS Cut Line= 3
2992678.1732891113858866.4126863 2992668.045684713858831.6502886
2992673.0010553613858712.6620095
#Sta/Elev= 24
       0  134.99   13.58  134.94   22.63  134.99   27.16  135.22   31.68   135.7
   36.21  136.07   45.92  134.74   53.41  134.15   58.74  131.02   60.86  130.83
   62.35  131.12   70.94  135.23    75.9  136.03   85.83  136.27   95.75   136.1
  100.72  135.28  105.68  134.15  110.64   134.7   115.6  134.68  120.56  134.48
  130.49  133.38  135.45  133.63  145.37  134.85   155.3  135.63
#Mann= 3 ,-1 , 0
       0     .07       0   36.21     .04       0   85.83     .07       0
#XS Ineff= 1 ,-1
   85.83   155.3  136.27
Permanent Ineff=
       F
Bank Sta=36.21,85.83
XS Rating Curve= 0 ,0
Exp/Cntr=0.3,0.1

Type RM Length L Ch R = 1 ,8955.833,14.98,10,10
BEGIN DESCRIPTION:
Upstream Section - TEMP DIRT WEIR
END DESCRIPTION:
XS GIS Cut Line= 6
2992719.8198593613858824.92917342992705.3451507813858811.1276919
2992706.0593881913858784.75208842992706.3753324413858773.0838047
2992706.8159483713858756.80791862992707.7539386213858722.1721611
#Sta/Elev= 22
       0   134.8   15.28  134.24    24.7  133.98   31.64  134.88   33.19  135.28
   37.59  135.87   41.99  136.06   46.39  136.13   50.28  136.16   54.17   136.1
   58.06  135.88   62.13  135.11    66.2  134.35   70.27  134.19   74.34  134.69
   79.29  134.34   84.24  134.01   89.19  133.41   94.14  133.23   99.09  134.04
  104.04  135.09  108.99  135.34
#Mann= 2 ,-1 , 0
       0     .04       0   50.28     .07       0
#XS Ineff= 1 ,-1
   50.28  108.99  136.16
Permanent Ineff=
       F
Bank Sta=0,50.28
XS Rating Curve= 0 ,0
Exp/Cntr=0.4,0.2

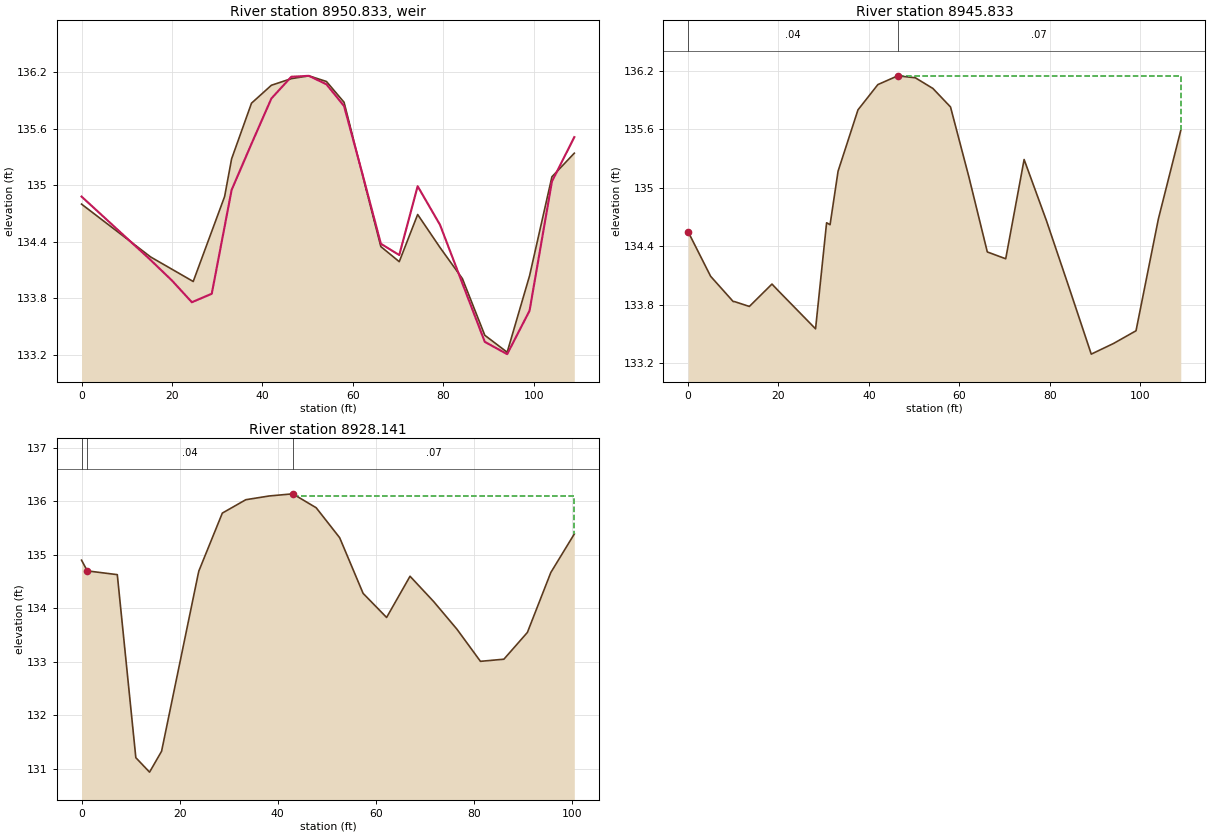
Type RM Length L Ch R = 5 ,8950.833,,,
BEGIN DESCRIPTION:
TEMP DIRT WEIR
END DESCRIPTION:
Node Name=TEMP DIRT WEIR
IW Pilot Flow=0
#Inline Weir SE= 25
       0  134.88       5  134.66      10  134.44      15  134.22      20  133.99
    24.4  133.76    28.8  133.85   33.19  134.95   37.59  135.44   41.99  135.92
   46.39  136.15   50.28  136.16   54.17  136.07   58.06  135.84   62.13  135.12
    66.2  134.38   70.27  134.26   74.34  134.99   79.29  134.58   84.24  133.96
   89.19  133.34   94.14  133.21   99.09  133.67  104.04  135.04  108.99  135.51
IW Dist,WD,Coef,Skew,MaxSub,Min_El,Is_Ogee,SpillHt,DesHd
2.5,5,2.6,0,0.98,, 0 ,,,0,0,

Type RM Length L Ch R = 1 ,8945.833,11.63,17.69,17.51
BEGIN DESCRIPTION:
Downstream Section - TEMP DIRT WEIR
END DESCRIPTION:
Node Name=P
XS GIS Cut Line= 6
2992729.8159023713858825.20017032992715.3411937813858811.3986887
2992716.0554311913858785.02308532992716.3713754413858773.3548015
2992716.8119913613858757.07891542992717.7499816113858722.4431579
#Sta/Elev= 28
       0  134.55       5  134.09      10  133.83   10.27  133.83   13.57  133.78
   18.57  134.01      20  133.94   28.21  133.55   30.65  134.64   31.42  134.62
   33.19  135.17   37.59   135.8   41.99  136.06   46.39  136.15   50.28  136.13
   54.17  136.02   58.06  135.83   62.13  135.11    66.2  134.34   70.27  134.27
   74.34  135.29   79.29  134.66   84.24  133.98   89.19  133.29   94.14   133.4
   99.09  133.53  104.04  134.68  108.99  135.59
#Mann= 2 ,-1 , 0
       0     .04       0   46.39     .07       0
#XS Ineff= 1 ,-1
   46.39  108.99  136.15
Permanent Ineff=
       F
Bank Sta=0,46.39
XS Rating Curve= 0 ,0
Exp/Cntr=0.4,0.2

Type RM Length L Ch R = 1 ,8928.141,24.75,22.49,22.6
XS GIS Cut Line= 2
2992732.88052878 13858824.2424952992734.0491616113858723.7617249
#Sta/Elev= 24
       0   134.9    1.18   134.7    7.29  134.63   11.07  131.21   13.87  130.94
   16.32  131.33   23.78  134.64   23.93   134.7   28.71  135.78    33.5  136.03
   38.28   136.1   43.07  136.14   47.85  135.88   52.64  135.32   57.42  134.28
   62.21  133.83   66.99   134.6   71.78  134.13   76.56  133.61   81.35  133.01
   86.13  133.05   90.92  133.55    95.7  134.67  100.49  135.39
#Mann= 3 ,-1 , 0
       0     .07       0    1.18     .04       0   43.07     .07       0
#XS Ineff= 1 ,-1
   43.07  100.49   136.1
Permanent Ineff=
       F
Bank Sta=1.18,43.07
XS Rating Curve= 0 ,0
Exp/Cntr=0.3,0.1