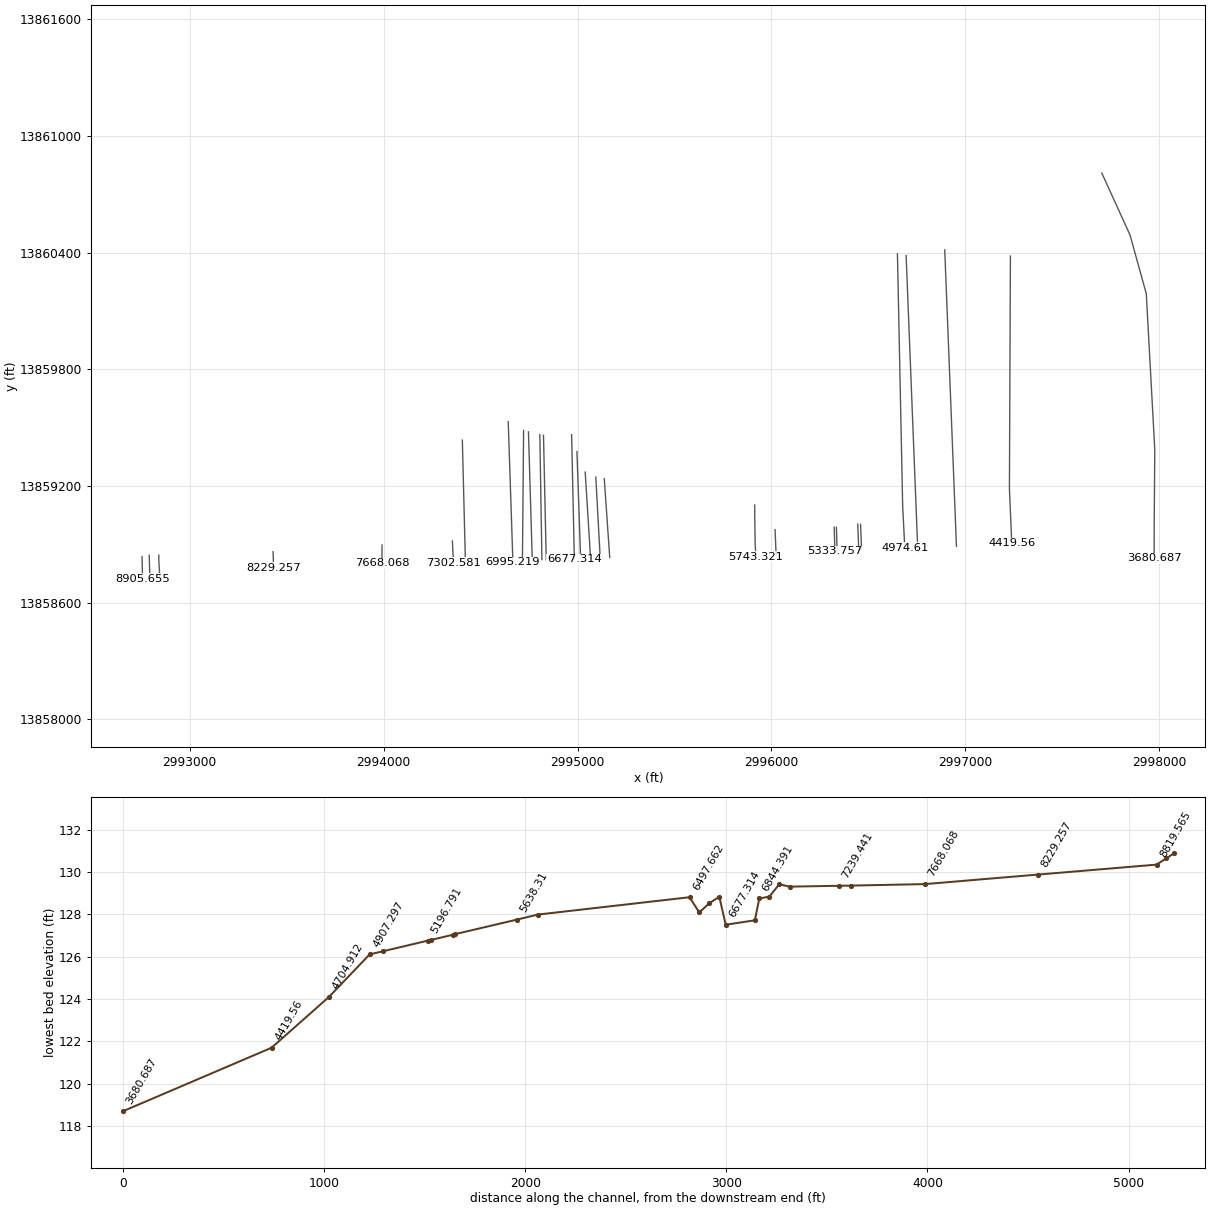
HEC-RAS study U101-07-00.prj: U101-07-00 2019 (Re-Study)

--- U101-07-00.g01 (geometry) --- (continued)

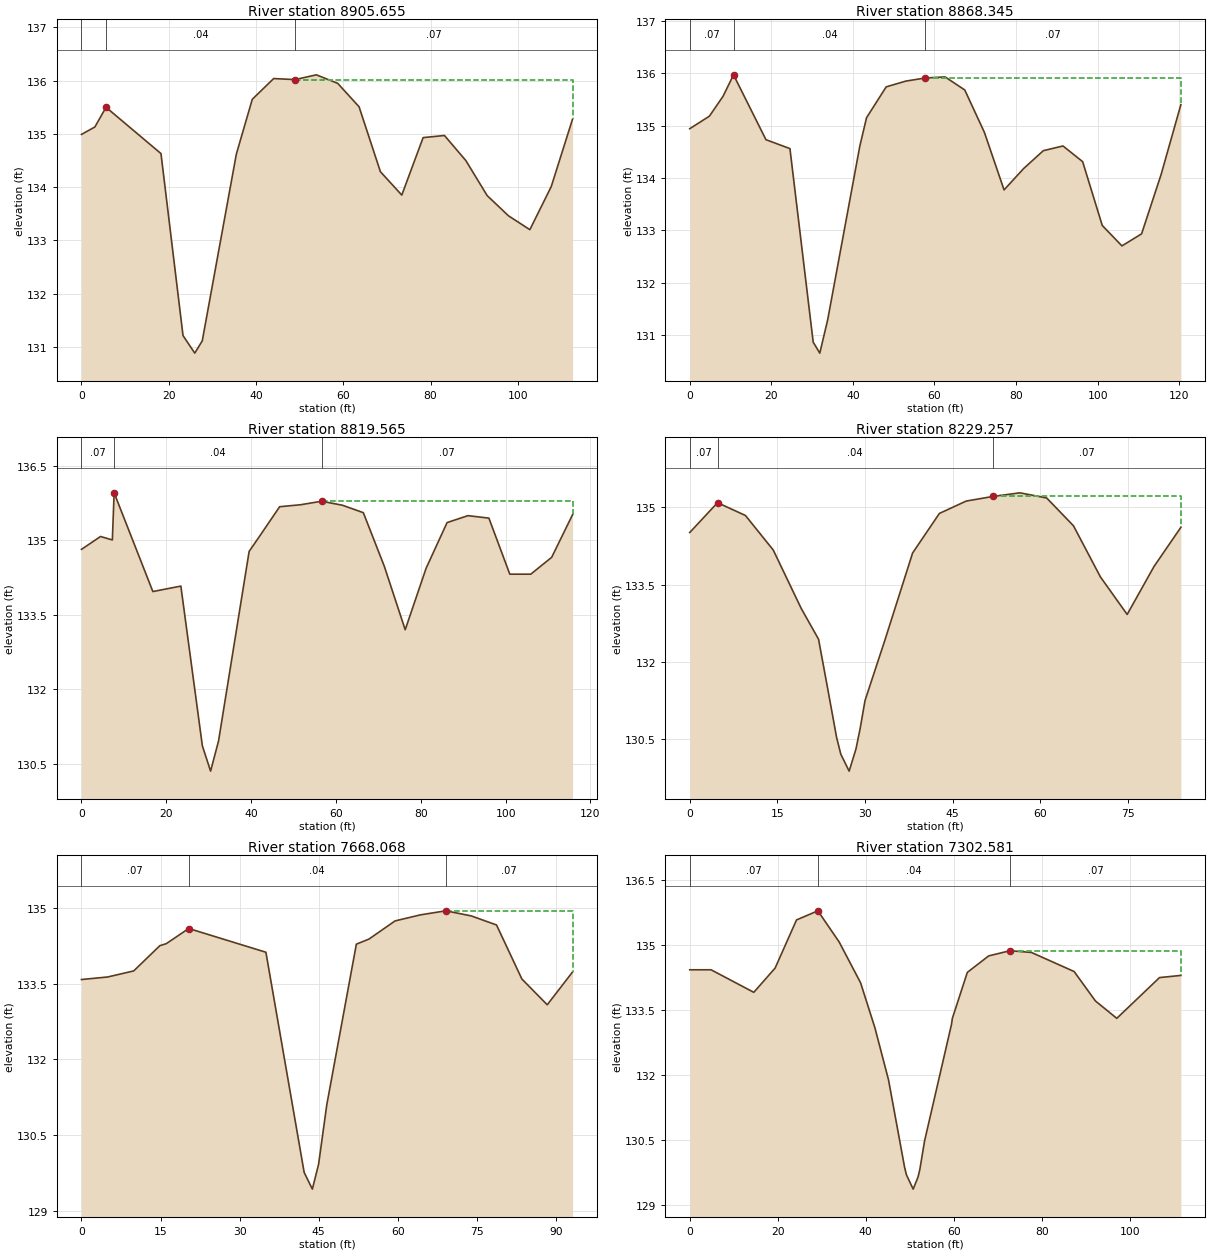
Type RM Length L Ch R = 1 ,8905.655,37.48,37.31,37.39
XS GIS Cut Line= 2
2992754.9789097813858836.56694542992757.41656895 13858724.053719
#Sta/Elev= 24
       0  134.99    3.07  135.13    5.63   135.5   18.22  134.63   23.27  131.21
   25.96  130.88   27.68  131.11   35.49  134.62   39.14  135.65   44.04  136.04
   48.93  136.02   53.82  136.11   58.72  135.95   63.61  135.51    68.5  134.29
    73.4  133.85   78.29  134.93   83.18  134.97   88.07   134.5   92.97  133.84
   97.86  133.46  102.75   133.2  107.65  134.01  112.54  135.28
#Mann= 3 ,-1 , 0
       0     .07       0    5.63     .04       0   48.93     .07       0
#XS Ineff= 1 ,-1
   48.93  112.54  136.02
Permanent Ineff=
       F
Bank Sta=5.63,48.93
XS Rating Curve= 0 ,0
Exp/Cntr=0.3,0.1

Type RM Length L Ch R = 1 ,8868.345,49.38,48.78,49.1
XS GIS Cut Line= 2
2992791.9227335313858843.84022482992795.3889339413858723.4694026
#Sta/Elev= 27
       0  134.94    4.82  135.18    8.17  135.56   10.74  135.97   18.69  134.73
   24.57  134.56   30.27  130.86   31.89  130.65   33.83  131.29   41.71  134.61
   43.35  135.15   48.17  135.74   52.99  135.85    57.8  135.91   62.62  135.93
   67.44  135.68   72.25  134.87   77.07  133.77   81.89  134.18    86.7  134.52
   91.52  134.61   96.34  134.31  101.15  133.09  105.97   132.7  110.79  132.93
   115.6  134.07  120.42   135.4
#Mann= 3 ,-1 , 0
       0     .07       0   10.74     .04       0    57.8     .07       0
#XS Ineff= 1 ,-1
    57.8  120.42  135.91
Permanent Ineff=
       F
Bank Sta=10.74,57.8
XS Rating Curve= 0 ,0
Exp/Cntr=0.3,0.1

Type RM Length L Ch R = 1 ,8819.565,589.45,590.31,589.88
XS GIS Cut Line= 3
2992841.4446161113858844.07480442992841.4482250213858817.0837167
2992846.5056296113858728.4352719
#Sta/Elev= 27
       0  134.82     4.5  135.08    7.28  135.01     7.7  135.96   16.83  133.97
   23.43  134.08   26.99  131.82    28.5  130.86   30.44  130.35   32.32  130.96
   39.53  134.78   41.79  135.06   46.72  135.68   51.66  135.72   56.59  135.79
   61.52  135.71   66.45  135.56   71.39  134.48   76.32   133.2   81.25  134.44
   86.19  135.36   91.12   135.5   96.05  135.45  100.98  134.32  105.92  134.32
  110.85  134.66  115.78  135.52
#Mann= 3 ,-1 , 0
       0     .07       0     7.7     .04       0   56.59     .07       0
#XS Ineff= 1 ,-1
   56.59  115.78  135.79
Permanent Ineff=
       F
Bank Sta=7.7,56.59
XS Rating Curve= 0 ,0
Exp/Cntr=0.3,0.1

Type RM Length L Ch R = 1 ,8229.257,562.05,561.19,560.87
XS GIS Cut Line= 3
2993430.45590527 13858862.3132852993431.6999972813858824.1900017
2993433.0123306113858778.2763796
#Sta/Elev= 27
       0  134.51    4.77  135.09    6.08  135.02    9.54  134.84    14.3  134.17
   19.07  133.04   22.05  132.44   23.49  131.56   25.15  130.53   25.86  130.21
   27.29  129.88   28.46  130.31   29.18  130.71   30.01  131.25   33.38  132.41
   38.01  134.06   38.14  134.11   42.74  134.88   47.33  135.12   51.92  135.21
   56.52  135.28   61.11  135.18    65.7  134.64    70.3  133.65   74.89  132.92
   79.48  133.85   84.08  134.61
#Mann= 3 ,-1 , 0
       0     .07       0    4.77     .04       0   51.92     .07       0
#XS Ineff= 1 ,-1
   51.92   84.08  135.21
Permanent Ineff=
       F
Bank Sta=4.77,51.92
XS Rating Curve= 0 ,0
Exp/Cntr=0.3,0.1

Type RM Length L Ch R = 1 ,7668.068,364.14,365.49,365.98
XS GIS Cut Line= 3
 2993992.226107213858896.5520617 2993992.226107213858837.0630074
2993992.6778779513858803.3819724
#Sta/Elev= 21
       0  133.58    4.96  133.63    9.91  133.75   14.87  134.25   16.09  134.29
   20.35  134.59   34.99  134.12   42.25  129.76    43.8  129.43   44.98  129.92
   46.54   131.1   52.15  134.28   54.53  134.38   59.49  134.74    64.3  134.86
   69.11  134.94   73.93  134.84   78.74  134.66   83.55  133.59   88.36  133.08
   93.17  133.73
#Mann= 3 ,-1 , 0
       0     .07       0   20.35     .04       0   69.11     .07       0
#XS Ineff= 1 ,-1
   69.11   93.17  134.94
Permanent Ineff=
       F
Bank Sta=20.35,69.11
XS Rating Curve= 0 ,0
Exp/Cntr=0.3,0.1

Type RM Length L Ch R = 1 ,7302.581,63.8,63.14,62.9
Node Name=O
XS GIS Cut Line= 2
2994354.9363397813858916.94834632994360.56690595 13858805.466942
#Sta/Elev= 27
       0  134.42    4.85  134.42   14.56   133.9   19.41  134.46   24.27  135.57
   29.12  135.78   33.97  135.06   38.83  134.12   42.09  133.0845.17999  131.88
48.82001  129.87   49.25  129.69   50.78  129.3651.89001  129.6452.29001  129.81
   53.37  130.4759.48999  133.16   59.69   133.3   63.09  134.36   67.94  134.74
    72.8  134.86   77.65  134.82   87.36  134.38   92.21   133.7   97.06   133.3
  106.77  134.24  111.62  134.29
#Mann= 3 ,-1 , 0
       0     .07       0   29.12     .04       0    72.8     .07       0
#XS Ineff= 1 ,-1
    72.8  111.62  134.86
Permanent Ineff=
       F
Bank Sta=29.12,72.8
XS Rating Curve= 0 ,0
Exp/Cntr=0.3,0.1

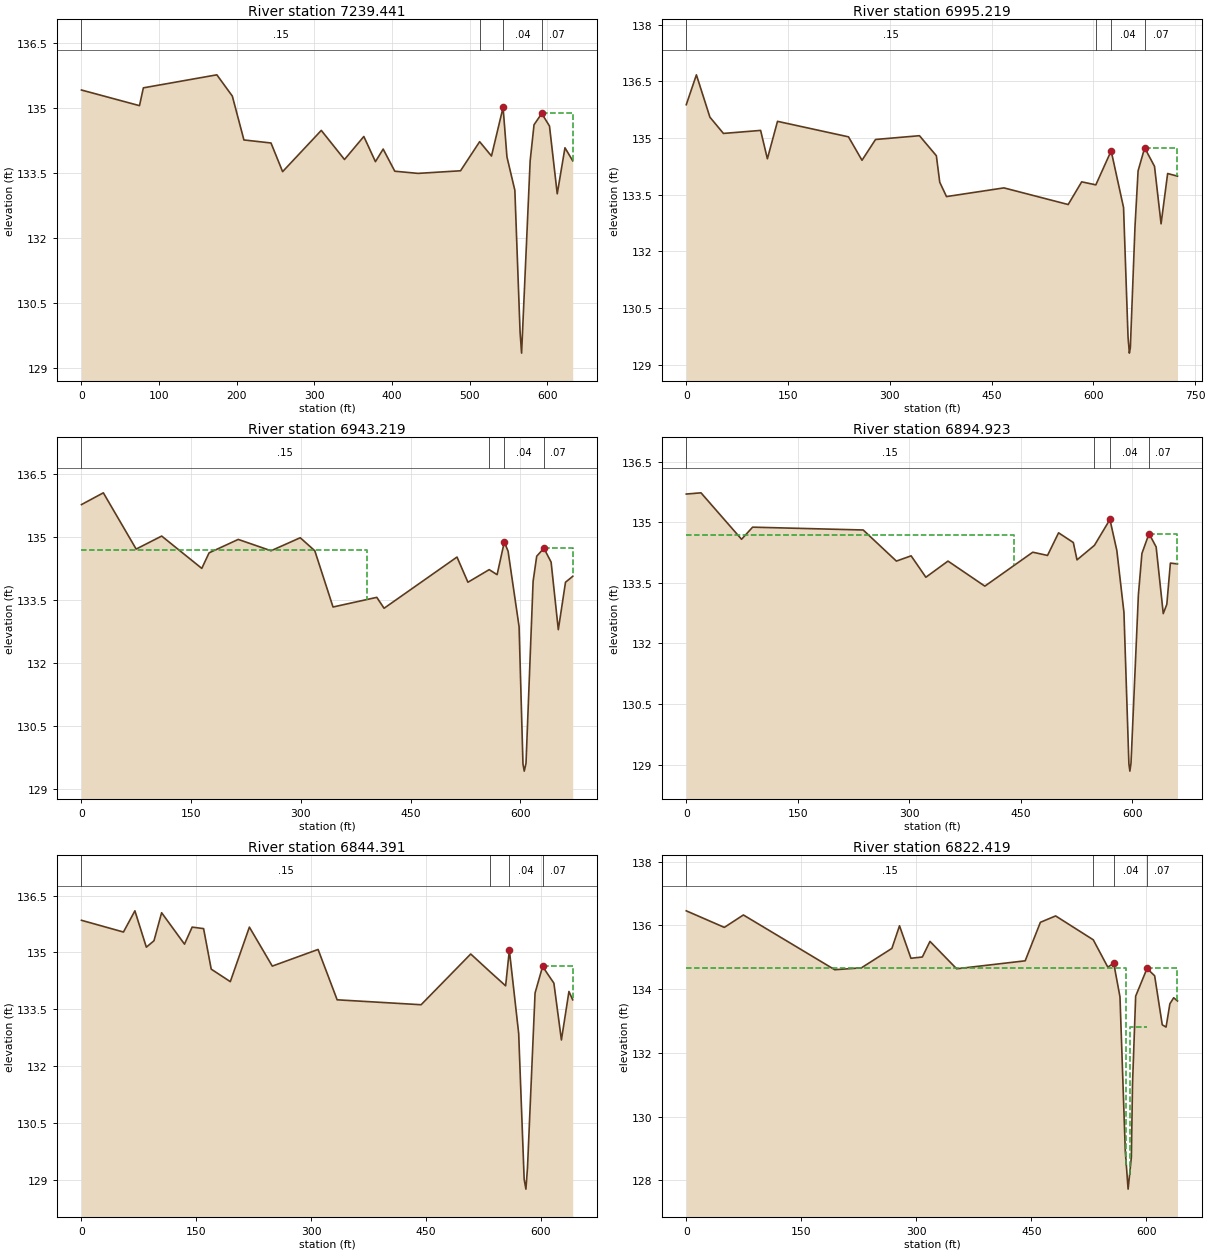
Type RM Length L Ch R = 1 ,7239.441,244.01,244.22,244.3
XS GIS Cut Line= 2
2994406.2147805213859435.79835852994422.2298403513858803.1939807
#Sta/Elev= 30
       0  135.41   74.74  135.05   79.72  135.46   174.4  135.76  194.33  135.27
  209.27  134.26  244.15  134.19   259.1  133.53  308.93  134.48  338.83  133.81
  363.74  134.34  378.69  133.76  388.65  134.05   403.6  133.54   433.5  133.49
  488.31  133.55  512.92  134.22  528.17  133.89  543.12  135.01   548.1  133.87
  558.29   133.1     565  129.84  566.96  129.35     578  133.78  582.98  134.61
  592.95  134.87  602.91  134.58  612.88  133.02  622.84  134.08  632.81  133.78
#Mann= 4 ,-1 , 0
       0     .15       0  512.92     .07       0  543.12     .04       0
  592.95     .07       0
#XS Ineff= 1 ,-1
  592.95  632.81  134.87
Permanent Ineff=
       F
Bank Sta=543.12,592.95
XS Rating Curve= 0 ,0
Exp/Cntr=0.3,0.1

Type RM Length L Ch R = 1 ,6995.219,53.15,52,51.65
XS GIS Cut Line= 3
2994642.8035461913859530.50453392994663.2798831913858918.1100894
2994667.0000201213858806.8501413
#Sta/Elev= 30
       0  135.88   14.94  136.67   34.87  135.55    54.8  135.12   109.6   135.2
  119.56  134.45   134.5  135.44  239.12  135.03  259.04  134.41  278.97  134.96
  343.73  135.06  368.64  134.53  373.62  133.83  383.58  133.45  468.27  133.68
  562.92  133.24  582.85  133.84  603.69  133.76  626.29  134.66  644.55  133.16
  651.18  129.73  653.11  129.31  654.56  129.45  661.43  132.66  665.98  134.13
  675.66  134.74  690.18  134.25  699.86  132.73  709.54  134.06  724.06  133.99
#Mann= 4 ,-1 , 0
       0     .15       0  603.69     .07       0  626.29     .04       0
  675.66     .07       0
#XS Ineff= 2 ,-1
       0  345.37  134.68  675.66  724.06  134.74
Permanent Ineff=
       F       F
Bank Sta=626.29,675.66
XS Rating Curve= 0 ,0
Exp/Cntr=0.3,0.1

Type RM Length L Ch R = 1 ,6943.219,47.24,48.3,48.61
XS GIS Cut Line= 3
2994721.9969573613859485.32581852994716.9398808613858917.2498549
2994716.0199351913858813.9098385
#Sta/Elev= 30
       0  135.77    29.9  136.05   74.75  134.71  109.63  135.02  164.45  134.25
  174.42  134.62  214.28  134.94  259.13  134.67     299  134.98  318.93  134.67
  343.85  133.33  403.65  133.56  413.62   133.3  513.28  134.52  528.23  133.92
  557.28  134.22   568.1   134.1  577.94  134.88   583.1  134.66  598.16  132.86
  603.46  129.59  605.21  129.42  607.62  129.61  617.31  133.94  622.23  134.54
  632.07  134.73  641.92   134.4  651.76  132.79   661.6  133.92  671.44  134.06
#Mann= 4 ,-1 , 0
       0     .15       0  557.28     .07       0  577.94     .04       0
  632.07     .07       0
#XS Ineff= 2 ,-1
       0     390  134.68  632.07  671.44  134.73
Permanent Ineff=
       F       F
Bank Sta=577.94,632.07
XS Rating Curve= 0 ,0
Exp/Cntr=0.3,0.1

Type RM Length L Ch R = 1 ,6894.923,50.91,50.53,50.43
XS GIS Cut Line= 3
2994747.1002536113859477.92360242994763.7800102813858917.5900774
2994766.77016178 13858817.140147
#Sta/Elev= 30
       0   135.7   19.84  135.73   74.41  134.58    89.3  134.88  238.12  134.81
  282.77  134.04  302.61  134.17  322.46  133.64  352.22  134.04  401.83  133.42
  466.32  134.26  486.17  134.18  501.05  134.74  520.89   134.5  525.86  134.07
  549.32  134.43  570.15  135.07  579.47   134.3  589.02  132.77  595.68  129.02
     597  128.84  598.53  129.04  608.44   133.2  613.22  134.23  622.79  134.72
  632.36  134.39  641.93  132.74  646.72  132.97  651.51  133.99  661.08  133.97
#Mann= 4 ,-1 , 0
       0     .15       0  549.32     .07       0  570.15     .04       0
  622.79     .07       0
#XS Ineff= 2 ,-1
       0  441.25  134.68  622.79  661.08  134.72
Permanent Ineff=
       F       F
Bank Sta=570.15,622.79
XS Rating Curve= 0 ,0
Exp/Cntr=0.3,0.1

Type RM Length L Ch R = 1 ,6844.391,21.82,21.97,22.02
XS GIS Cut Line= 3
2994805.8176558613859463.33636122994814.7700657713858920.0900723
2994816.3901412813858821.7799015
#Sta/Elev= 30
       0  135.85   54.83  135.54   69.78   136.1   84.74  135.14   94.71  135.31
  104.68  136.05  134.58  135.22  144.55  135.67  159.51  135.63  169.48  134.56
   194.4  134.23  219.32  135.67  249.23  134.64  309.04  135.08  333.97  133.75
  443.63  133.62  508.43  134.96   533.7  134.49  554.02  134.12  558.89  135.06
  571.08  132.86  578.23  129.01  580.52  128.75  582.59  129.32  592.48  133.93
  602.31  134.63  617.06  134.19  626.89  132.69  636.73  133.97  641.64  133.75
#Mann= 4 ,-1 , 0
       0     .15       0   533.7     .07       0  558.89     .04       0
  602.31     .07       0
#XS Ineff= 2 ,-1
       0  502.04  134.68  602.31  641.64  134.63
Permanent Ineff=
       F       F
Bank Sta=558.89,602.31
XS Rating Curve= 0 ,0
Exp/Cntr=0.5,0.3

Type RM Length L Ch R = 1 ,6822.419,145.02,145.11,145.05
BEGIN DESCRIPTION:
Upstream Section - WATERSTONE FALLS DR
END DESCRIPTION:
XS GIS Cut Line= 2
2994824.6214240313859460.58472632994838.7326162813858820.2802326
#Sta/Elev= 30
       0  136.46   49.65  135.94   74.47  136.33  193.63  134.61  228.38  134.67
   268.1  135.28  278.03  135.99  292.92  134.97  307.82  135.01  317.75   135.5
   352.5  134.64  441.87  134.89  461.73   136.1  481.59   136.3  530.64  135.55
  549.65  134.69  557.28  134.82  565.47  133.76  572.43  128.91  576.07  127.72
  580.31  128.72  581.81  131.01  585.92  133.78  600.74  134.65  610.67  134.42
   620.6  132.88  625.57  132.81  630.53  133.54   635.5  133.73  640.46  133.63
#Mann= 4 ,-1 , 0
       0     .15       0  530.64     .07       0  557.28     .04       0
  600.74     .07       0
#XS Ineff= 3 ,-1
       0  573.92  134.68  577.92  600.74  132.82  600.74  640.46  134.65
Permanent Ineff=
       F       F       F
Bank Sta=557.28,600.74
XS Rating Curve= 0 ,0
Exp/Cntr=0.5,0.3

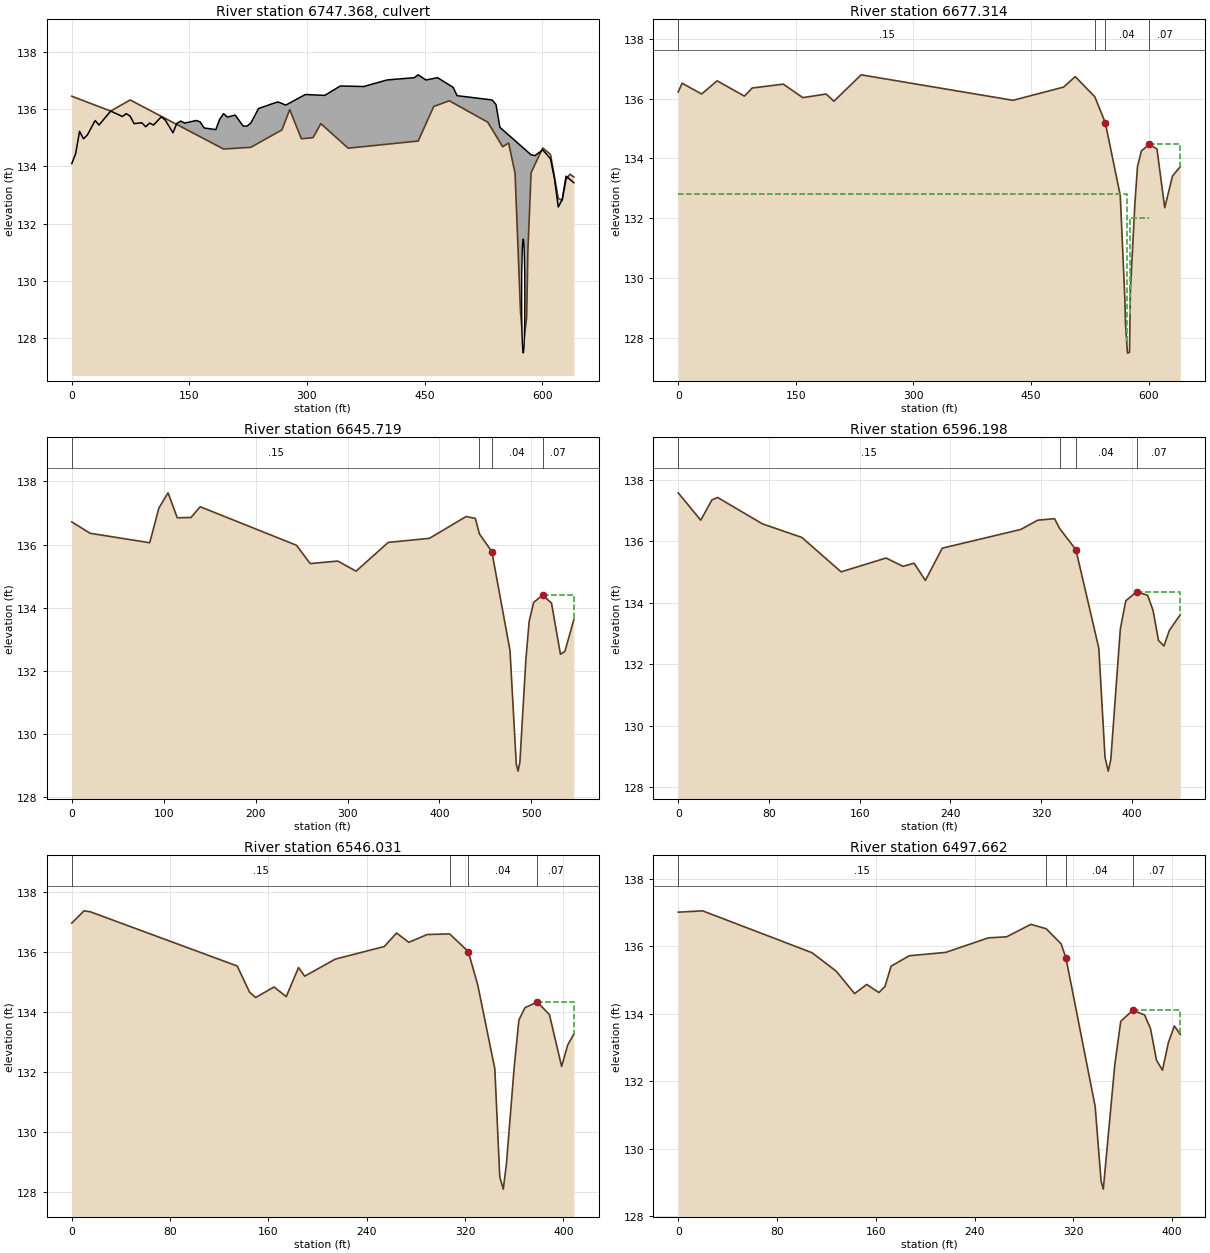
Type RM Length L Ch R = 2 ,6747.368,,,
BEGIN DESCRIPTION:
WATERSTONE FALLS DR
END DESCRIPTION:
Node Name=WATERSTONE FALLS
Bridge Culvert--1,0,-1,-1, 0
Deck Dist Width WeirC Skew NumUp NumDn MinLoCord MaxHiCord MaxSubmerge Is_Ogee
37,80,2.6,0, 60, 60, , , 0.98, 0, 0,0,,
       0    4.96    9.93   14.89   19.86   29.79   34.75   49.65   64.54   69.51
   74.47   79.44   89.37   94.33    99.3  104.26  114.19  119.16  129.08  134.05
  139.01  143.98  158.87  163.84   168.8   183.7  188.66  193.63  198.59  208.52
  218.45  223.42  228.38  238.31  258.17  263.13  273.06  297.89  322.71  342.57
  372.36  402.15   436.9  441.87   451.8  466.69  486.55  491.52   536.2  541.16
  546.13  585.85  590.81  600.74  610.67  615.64   620.6  625.57  630.53  640.46
   134.1  134.45  135.23  134.97   135.1  135.61  135.45  135.94  135.75  135.85
  135.76   135.5  135.53  135.39  135.52  135.45  135.74  135.63  135.18  135.51
  135.59  135.52  135.61  135.56  135.35  135.29  135.65  135.85  135.73   135.8
  135.42  135.41  135.52  136.03  136.22  136.26  136.15  136.52  136.49  136.82
   136.8  137.03  137.11  137.21  137.03  137.11  136.77  136.48  136.33  136.17
  135.37  134.41  134.38  134.58  134.27  133.59  132.58  132.84  133.66  133.43
       0       0       0       0       0       0       0       0       0       0
       0       0       0       0       0       0       0       0       0       0
       0       0       0       0       0       0       0       0       0       0
       0       0       0       0       0       0       0       0       0       0
       0       0       0       0       0       0       0       0       0       0
       0       0       0       0       0       0       0       0       0       0
       0    4.96    9.93   14.89   19.86   29.79   34.75   49.65   64.54   69.51
   74.47   79.44   89.37   94.33    99.3  104.26  114.19  119.16  129.08  134.05
  139.01  143.98  158.87  163.84   168.8   183.7  188.66  193.63  198.59  208.52
  218.45  223.42  228.38  238.31  258.17  263.13  273.06  297.89  322.71  342.57
  372.36  402.15   436.9  441.87   451.8  466.69  486.55  491.52   536.2  541.16
  546.13  585.85  590.81  600.74  610.67  615.64   620.6  625.57  630.53  640.46
   134.1  134.45  135.23  134.97   135.1  135.61  135.45  135.94  135.75  135.85
  135.76   135.5  135.53  135.39  135.52  135.45  135.74  135.63  135.18  135.51
  135.59  135.52  135.61  135.56  135.35  135.29  135.65  135.85  135.73   135.8
  135.42  135.41  135.52  136.03  136.22  136.26  136.15  136.52  136.49  136.82
   136.8  137.03  137.11  137.21  137.03  137.11  136.77  136.48  136.33  136.17
  135.37  134.41  134.38  134.58  134.27  133.59  132.58  132.84  133.66  133.43
       0       0       0       0       0       0       0       0       0       0
       0       0       0       0       0       0       0       0       0       0
       0       0       0       0       0       0       0       0       0       0
       0       0       0       0       0       0       0       0       0       0
       0       0       0       0       0       0       0       0       0       0
       0       0       0       0       0       0       0       0       0       0
BR Coef=-1 , 0 , 0 ,, 0 ,,,0.8,-1,,0,
WSPro=,,,, 1 ,,,, 0 ,,,, 0 ,,,,-1 ,-1 ,-1 , 0 , 0 , 0 , 0 , 0
Culvert=1,4,,106.4,0.013,0.7,1,1,1,127.46,575.92,127.49,574.34,Culvert #1  , 0 ,22.3
Culvert Bottom n=0.013
BC Design=,, 0 ,, 0 ,,,,,,
BC Use User HTab Curves=0
BC User HTab FreeFlow(D)= 0

Type RM Length L Ch R = 1 ,6677.314,31.27,31.6,31.71
BEGIN DESCRIPTION:
Downstream Section - WATERSTONE FALLS DR
END DESCRIPTION:
XS GIS Cut Line= 2
2994969.5863571913859463.77960182994983.6975494513858823.4751081
#Sta/Elev= 30
       0  136.22    4.96  136.51   29.79  136.15   49.65  136.59    84.4  136.08
   94.33  136.35  134.05  136.48  158.87  136.03  188.66  136.15  198.59  135.91
  233.35  136.79  426.97  135.94  491.52  136.38  506.41  136.73  531.38  136.06
  544.81  135.19  563.86  132.77  569.65  129.37  570.52  128.51  573.05  127.51
  575.66  127.54  576.75  129.58  582.59  132.52  585.85  133.73  590.81  134.25
  600.74  134.47  610.67  134.32   620.6  132.36  630.53  133.42  640.46  133.73
#Mann= 4 ,-1 , 0
       0     .15       0  531.38     .07       0  544.81     .04       0
  600.74     .07       0
#XS Ineff= 3 ,-1
       0  572.34  132.82  576.34  600.74     132  600.74  640.46  134.47
Permanent Ineff=
       F       F       F
Bank Sta=544.81,600.74
XS Rating Curve= 0 ,0
Exp/Cntr=0.5,0.3

Type RM Length L Ch R = 1 ,6645.719,48.8,49.52,49.77
XS GIS Cut Line= 3
2994997.0206855213859376.62524852995012.5400114513858927.8400569
2995015.8999128613858830.6801462
#Sta/Elev= 30
       0  136.72   19.96  136.36   84.82  136.06    94.8  137.16  104.78  137.64
  114.76  136.85  129.73  136.86  139.71   137.2  244.48  135.98  259.45   135.4
  289.39  135.48  309.35  135.16  344.27  136.07  389.18   136.2   429.1  136.89
  439.07  136.83  443.54  136.34  457.04  135.78   476.8  132.65  483.62  129.06
  485.57  128.83  487.55  129.11  494.05  132.35  497.66  133.57  502.52  134.17
  512.25   134.4  521.97  134.15  531.69  132.53  536.55  132.62  546.27  133.63
#Mann= 4 ,-1 , 0
       0     .15       0  443.54     .07       0  457.04     .04       0
  512.25     .07       0
#XS Ineff= 2 ,-1
       0  447.52  132.82  512.25  546.27   134.4
Permanent Ineff=
       F       F
Bank Sta=457.04,512.25
XS Rating Curve= 0 ,0
Exp/Cntr=0.3,0.1

Type RM Length L Ch R = 1 ,6596.198,50.34,50.17,50.08
XS GIS Cut Line= 3
2995039.5796555313859271.49914642995060.9700326913858930.3600649
2995067.2899019413858829.5699122
#Sta/Elev= 30
       0  137.58   19.82  136.69   29.72  137.35   34.68  137.43   74.31  136.57
  108.98  136.13  143.66  135.01  183.29  135.46  198.15  135.19  208.06  135.29
  217.97  134.73  232.83  135.78  302.18  136.39  317.04  136.69   331.9  136.74
  336.39  136.42  350.72  135.73  370.91  132.53  376.42  128.97  379.24  128.53
  381.48   128.9   389.9  133.15  394.71  134.07  404.33  134.36  413.94  134.25
  418.75  133.76  423.56  132.78  428.37   132.6  433.18  133.11   442.8  133.62
#Mann= 4 ,-1 , 0
       0     .15       0  336.39     .07       0  350.72     .04       0
  404.33     .07       0
#XS Ineff= 2 ,-1
       0  309.89  132.82  404.33   442.8  134.36
Permanent Ineff=
       F       F
Bank Sta=350.72,404.33
XS Rating Curve= 0 ,0
Exp/Cntr=0.3,0.1

Type RM Length L Ch R = 1 ,6546.031,47.86,48.37,48.42
Node Name=N
XS GIS Cut Line= 3
2995094.3236405313859245.30267652995111.4000499413858931.6300755
2995116.52996095 13858837.399949
#Sta/Elev= 30
       0  136.96    9.97  137.37   14.96  137.34  134.63  135.53   144.6  134.66
  149.59  134.48  164.55  134.83  174.52  134.51  184.49  135.48  189.48  135.19
  214.41  135.76   254.3  136.18  264.27  136.63  274.25  136.32  289.21  136.58
  307.47   136.6  322.66  136.01  330.42  134.88  344.22   132.1  348.24   128.5
  351.08  128.09  353.63  128.92  360.01  132.17  363.81  133.73  368.77  134.14
  378.71  134.33  388.64  133.91  398.57  132.18  403.54   132.9  408.51  133.26
#Mann= 4 ,-1 , 0
       0     .15       0  307.47     .07       0  322.66     .04       0
  378.71     .07       0
#XS Ineff= 2 ,-1
       0  248.91  132.82  378.71  408.51  134.33
Permanent Ineff=
       F       F
Bank Sta=322.66,378.71
XS Rating Curve= 0 ,0
Exp/Cntr=0.3,0.1

Type RM Length L Ch R = 1 ,6497.662,755.84,754.34,753.89
XS GIS Cut Line= 3
2995137.9078709513859237.94737632995159.0699021113858933.3600589
2995166.0899011913858832.3199067
#Sta/Elev= 30
       0  137.01    19.7  137.05  108.34  135.81  128.04  135.26  142.81   134.6
  152.66  134.87  162.51  134.63  167.43  134.81  172.36  135.41  187.13  135.72
  216.68  135.82  251.15  136.25  265.93  136.28  285.62  136.65     298  136.52
  310.14  136.07  314.01  135.65  337.65  131.26  342.45  129.05  344.24  128.81
  353.55  132.49  358.38  133.78  368.02   134.1  377.67  133.97  382.49  133.56
  387.31  132.63  392.14  132.33  396.96  133.15  401.78  133.64  406.61  133.39
#Mann= 4 ,-1 , 0
       0     .15       0     298     .07       0  314.01     .04       0
  368.02     .07       0
#XS Ineff= 2 ,-1
       0  210.16  133.22  368.02  406.61   134.1
Permanent Ineff=
       F       F
Bank Sta=314.01,368.02
XS Rating Curve= 0 ,0
Exp/Cntr=0.3,0.1

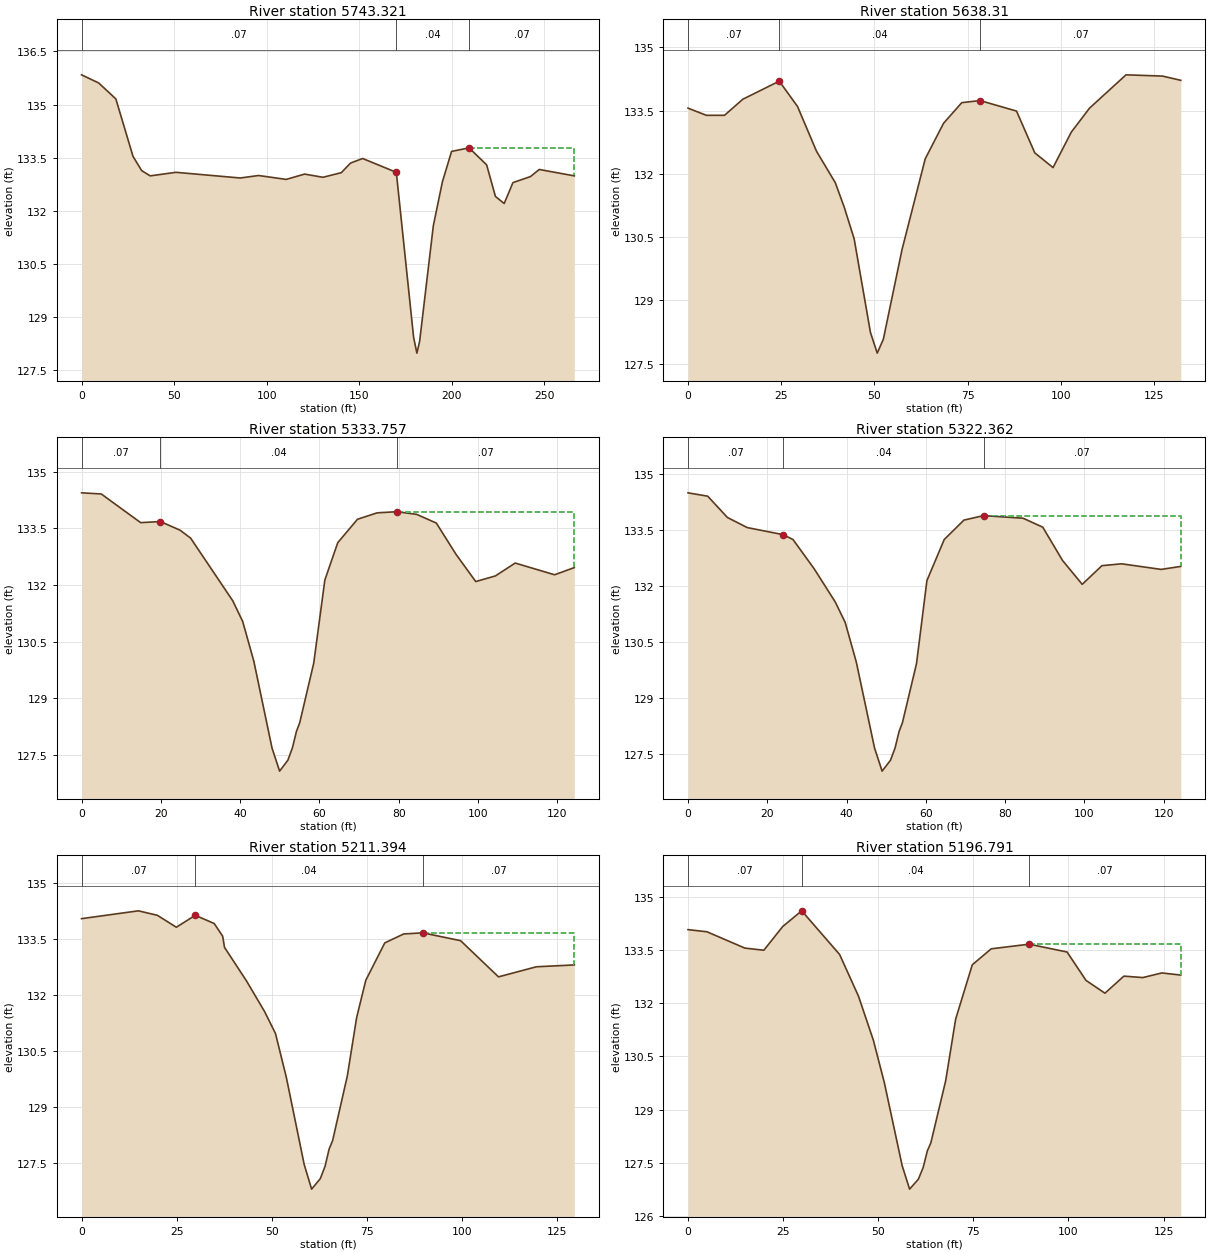
Type RM Length L Ch R = 1 ,5743.321,104.29,105.01,105.32
XS GIS Cut Line= 4
2995913.5900466113859101.36956542995913.5900466113859050.3998511
 2995915.911236213858901.51989952995919.7209398613858835.3323679
#Sta/Elev= 30
       0  135.84    9.27  135.61   18.53  135.16    27.8  133.54   32.44  133.14
   37.07  132.99   50.97  133.09   85.71  132.93   95.64     133  110.53  132.89
  120.46  133.04  130.38  132.95  140.31  133.08  145.27  133.35  151.82  133.48
  170.02  133.09  179.35  128.44  181.13  127.99  182.61  128.32     190  131.58
   194.9  132.82  199.87  133.68  209.34  133.78  218.81   133.3  223.55  132.41
  228.28  132.21  233.02   132.8  242.49  132.97  247.22  133.17  266.16  132.99
#Mann= 3 ,-1 , 0
       0     .07       0  170.02     .04       0  209.34     .07       0
#XS Ineff= 1 ,-1
  209.34  266.16  133.78
Permanent Ineff=
       F
Bank Sta=170.02,209.34
XS Rating Curve= 0 ,0
Exp/Cntr=0.3,0.1

Type RM Length L Ch R = 1 ,5638.31 ,304.84,304.55,304.45
XS GIS Cut Line= 2
2996018.4796006113858975.41640532996024.0169911113858843.3700814
#Sta/Elev= 26
       0  133.56     4.9  133.39    9.79  133.39   14.68  133.77   24.47   134.2
   29.37   133.634.45001  132.5439.51001  131.7941.89999  131.21   44.56  130.46
48.92999  128.24   50.75  127.7552.39001  128.08   57.41  130.21   63.63  132.36
   68.53   133.2   73.42  133.69   78.32  133.74   88.11  133.49      93   132.5
    97.9  132.15  102.79  132.99  107.69  133.56  117.48  134.35  127.27  134.32
  132.16  134.22
#Mann= 3 ,-1 , 0
       0     .07       0   24.47     .04       0   78.32     .07       0
#XS Ineff= 1 ,-1
   78.32  132.16  133.74
Permanent Ineff=
       F
Bank Sta=24.47,78.32
XS Rating Curve= 0 ,0
Exp/Cntr=0.3,0.1

Type RM Length L Ch R = 1 ,5333.757,11.4,11.4,11.4
XS GIS Cut Line= 2
2996323.3028098613858987.94820442996327.1853480313858863.7112481
#Sta/Elev= 29
       0  134.44    4.97  134.41   14.92  133.65   19.89  133.68   24.86  133.45
27.52002  133.2438.15002  131.5840.65997  131.0343.46002  129.9848.04999  127.68
49.96002  127.0752.04999  127.3653.20001  127.6954.20001  128.1255.03003  128.35
58.57001  129.93   61.37  132.13   64.63  133.12   69.61  133.74   74.58  133.91
   79.55  133.94   84.52  133.87   89.49  133.64   94.47  132.81   99.44  132.09
  104.41  132.24  109.38  132.58  119.33  132.27   124.3  132.46
#Mann= 3 ,-1 , 0
       0     .07       0   19.89     .04       0   79.55     .07       0
#XS Ineff= 1 ,-1
   79.55   124.3  133.94
Permanent Ineff=
       F
Bank Sta=19.89,79.55
XS Rating Curve= 0 ,0
Exp/Cntr=0.3,0.1

Type RM Length L Ch R = 1 ,5322.362,110.73,110.97,111.07
BEGIN DESCRIPTION:
U/S of Confluence with U201-08-01
END DESCRIPTION:
XS GIS Cut Line= 2
2996334.7204379413858987.40457032996338.60297611 13858863.167614
#Sta/Elev= 29
       0  134.49    4.97   134.4    9.94  133.83   14.92  133.56   24.02  133.37
26.47998  133.2431.79999  132.46   37.13  131.5739.65002  131.0242.45001  129.96
47.04999  127.6648.96002  127.0451.07001  127.3352.22998  127.6653.23999   128.1
54.07001  128.3357.64001  129.92   60.26  132.14   64.63  133.24   69.61  133.76
   74.58  133.88   84.52  133.81   89.49  133.57   94.47  132.68   99.44  132.04
  104.41  132.54  109.38  132.59  119.33  132.44   124.3  132.52
#Mann= 3 ,-1 , 0
       0     .07       0   24.02     .04       0   74.58     .07       0
#XS Ineff= 1 ,-1
   74.58   124.3  133.88
Permanent Ineff=
       F
Bank Sta=24.02,74.58
XS Rating Curve= 0 ,0
Exp/Cntr=0.3,0.1

Type RM Length L Ch R = 1 ,5211.394,14.6,14.6,14.6
BEGIN DESCRIPTION:
D/S of Confluence U201-08-01
END DESCRIPTION:
XS GIS Cut Line= 2
2996444.6765828613859004.09810642996449.8534097813858874.6846513
#Sta/Elev= 28
       0  134.04   14.94  134.25   19.93  134.13   24.91  133.81   29.89  134.13
   34.87  133.91   37.09  133.5737.58002  133.2743.35999  132.3748.10999  131.55
50.97998  130.9653.84003  129.7858.52002  127.4560.46997  126.79   62.75  127.07
      64   127.465.09003  127.8765.98999  128.0969.84998  129.82   72.31  131.39
   74.72  132.39    79.7  133.39   84.68  133.63   89.67  133.66   99.63  133.45
  109.59  132.48  119.55  132.75  129.52   132.8
#Mann= 3 ,-1 , 0
       0     .07       0   29.89     .04       0   89.67     .07       0
#XS Ineff= 1 ,-1
   89.67  129.52  133.66
Permanent Ineff=
       F
Bank Sta=29.89,89.67
XS Rating Curve= 0 ,0
Exp/Cntr=0.3,0.1

Type RM Length L Ch R = 1 ,5196.791,221.84,222.18,222.33
XS GIS Cut Line= 2
2996459.3563435213859002.46687612996464.53317045 13858873.053421
#Sta/Elev= 28
       0  134.07    4.98  134.01   14.94  133.55   19.93  133.49   24.91  134.16
   29.89   134.6   39.85  133.37   44.83  132.1948.72998  130.9551.59998  129.76
56.28998  127.4258.23999  126.7660.54999  127.04   61.81  127.3762.90997  127.84
63.82001  128.0667.71997  129.81   70.35  131.55   74.72  133.08    79.7  133.53
   89.67  133.66   99.63  133.44  104.61  132.64  109.59  132.28  114.57  132.76
  119.55  132.72  124.54  132.85  129.52  132.79
#Mann= 3 ,-1 , 0
       0     .07       0   29.89     .04       0   89.67     .07       0
#XS Ineff= 1 ,-1
   89.67  129.52  133.66
Permanent Ineff=
       F
Bank Sta=29.89,89.67
XS Rating Curve= 0 ,0
Exp/Cntr=0.3,0.1

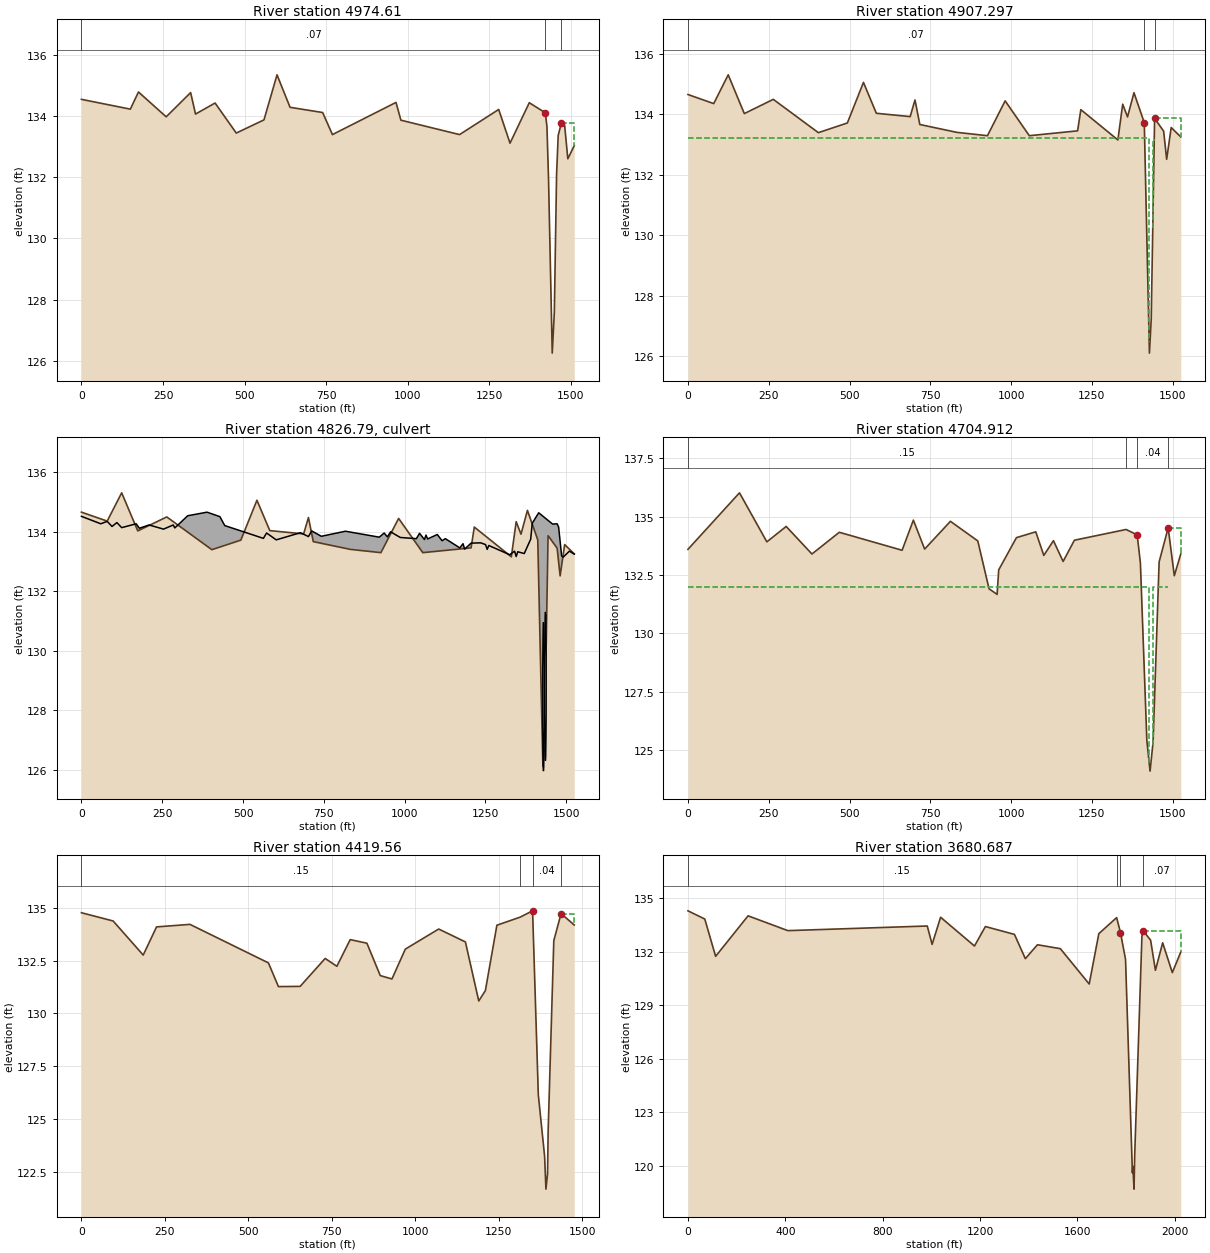
Type RM Length L Ch R = 1 ,4974.61 ,68.66,67.31,67.16
Node Name=M
XS GIS Cut Line= 3
2996649.3635094513860392.97623422996676.4500694413859094.7406417
2996687.1580532813858883.5012348
#Sta/Elev= 30
       0  134.54  149.83  134.22   174.8  134.78   259.7  133.97  334.62  134.76
   349.6  134.06  409.53  134.42  474.46  133.44  559.36  133.87  599.32  135.34
  639.27  134.28  739.16  134.11  769.12  133.39   963.9  134.44  978.88  133.86
 1158.68  133.39 1278.54  134.21 1313.27  133.11  1372.3  134.43 1421.49   134.1
 1426.41  133.65 1431.33  131.91 1442.61  126.26 1449.03  127.59 1455.92  132.09
 1460.84  133.36 1470.68  133.77 1480.52   133.7 1490.35   132.6 1510.03  133.03
#Mann= 3 ,-1 , 0
       0     .07       0 1421.49     .04       0 1470.68     .07       0
#XS Ineff= 2 ,-1
       0 1205.81  133.22 1470.68 1510.03  133.77
Permanent Ineff=
       F       F
Bank Sta=1421.49,1470.68
XS Rating Curve= 0 ,0
Exp/Cntr=0.5,0.3

Type RM Length L Ch R = 1 ,4907.297,202.05,202.39,200.1
BEGIN DESCRIPTION:
Upstream Section - ELROD RD
END DESCRIPTION:
XS GIS Cut Line= 4
2996694.1780523713860384.30171092996750.8724927813858955.4259597
2996753.6477496913858885.48088962996754.6388894513858860.5006246
#Sta/Elev= 30
       0  134.65   79.72  134.35  124.56   135.3  174.39  134.02  264.08  134.49
  403.59  133.39  493.27  133.71   543.1  135.05  582.96  134.03   687.6  133.92
  702.54  134.47  717.49  133.66  832.09   133.4  926.76  133.29  981.57  134.44
 1056.31  133.29 1205.78  133.45 1215.75  134.15 1330.35  133.15  1345.3  134.33
 1360.24  133.91 1380.17  134.71 1412.09  133.72    1428  126.11 1433.58  127.24
 1444.02  133.86    1472  133.44 1481.33  132.51 1495.33  133.56    1525  133.25
#Mann= 3 ,-1 , 0
       0     .07       0 1412.09     .04       0 1444.02     .07       0
#XS Ineff= 3 ,-1
       0 1427.24  133.22 1438.34 1444.02  133.16 1444.02    1525  133.86
Permanent Ineff=
       F       F       F
Bank Sta=1412.09,1444.02
XS Rating Curve= 0 ,0
Exp/Cntr=0.5,0.3

Type RM Length L Ch R = 2 ,4826.79 ,,,
BEGIN DESCRIPTION:
ELROD RD
END DESCRIPTION:
Node Name=ELROD RD
Bridge Culvert--1,0,-1,-1, 0
Deck Dist Width WeirC Skew NumUp NumDn MinLoCord MaxHiCord MaxSubmerge Is_Ogee
63,90,2.6,0, 60, 60, , , 0.98, 0, 0,0,,
       0   59.79   79.72   94.67  109.62  124.56  169.41  179.37  209.27  254.11
  284.01  288.99  328.85  388.64   428.5  443.45  563.03     573  602.89  677.63
  702.54  712.51   742.4  817.14  921.78  936.73  946.69  956.66  986.55 1036.38
 1046.34 1061.29 1066.27 1071.26 1101.15  1116.1 1126.06 1170.91 1180.87 1185.85
 1205.78 1235.68 1250.63 1255.61 1260.59 1325.37 1340.31  1345.3 1350.28 1370.21
 1390.14 1395.12 1415.05    1458    1472 1476.67    1486 1490.67    1510    1525
  134.51  134.26  134.34  134.17   134.3  134.13  134.26  134.11  134.22  134.08
  134.22  134.12  134.53  134.65   134.5   134.2  133.77  133.95  133.72  133.96
  133.83  134.02  133.84  134.01  133.81  133.95  133.82  133.99   133.8  133.76
  133.94  133.73  133.88  133.75   133.9  133.69  133.76  133.45  133.59  133.41
  133.61  133.62  133.56   133.4  133.53  133.22  133.34  133.16  133.32  133.26
  133.74  134.28  134.63  134.25  134.26  134.15  133.18  133.14  133.34  133.24
                                                                                
                                                                                
                                                                                
                                                                                
                                                                                
                                                                                
       0   59.79   79.72   94.67  109.62  124.56  169.41  179.37  209.27  254.11
  284.01  288.99  328.85  388.64   428.5  443.45  563.03     573  602.89  677.63
  702.54  712.51   742.4  817.14  921.78  936.73  946.69  956.66 1036.38 1046.34
 1061.29 1066.27 1071.26 1101.15  1116.1 1126.06 1170.91 1180.87 1185.85 1205.78
 1235.68 1250.63 1255.61 1260.59 1325.37 1340.31  1345.3 1350.28 1360.24 1365.23
 1390.14 1434.67 1439.33    1444    1472 1476.67    1486 1490.67    1510    1525
  134.51  134.26  134.34  134.17   134.3  134.13  134.26  134.11  134.22  134.08
  134.22  134.12  134.53  134.65   134.5   134.2  133.77  133.95  133.72  133.96
  133.83  134.02  133.84  134.01  133.81  133.95  133.82  133.99  133.76  133.94
  133.73  133.88  133.75   133.9  133.69  133.76  133.45  133.59  133.41  133.61
  133.62  133.56   133.4  133.53  133.22  133.34  133.16  133.32  133.26  134.19
  134.62  134.46  134.07  134.38  134.26  134.15  133.18  133.14  133.34  133.24
                                                                                
                                                                                
                                                                                
                                                                                
                                                                                
                                                                                
BR Coef=-1 , 0 , 0 ,, 0 ,,,0.8,-1,,0,
WSPro=,,,, 1 ,,,, 0 ,,,, 0 ,,,,-1 ,-1 ,-1 , 0 , 0 , 0 , 0 , 0
Culvert=1,5,,120,0.013,0.5,1,1,3,125.95,1429.74,124.12,1429.74,Culvert #1  , 0 ,55.5
Culvert Bottom n=0.013
Culvert=1,5,,120,0.013,0.5,1,1,3,126.3,1435.84,124.07,1435.84,Culvert #2  , 0 ,55.5
Culvert Bottom n=0.013
BC Design=,, 0 ,, 0 ,,,,,,
BC Use User HTab Curves=0
BC User HTab FreeFlow(D)= 0

Type RM Length L Ch R = 1 ,4704.912,285.4,285.35,285.41
BEGIN DESCRIPTION:
Downstream Section - ELROD RD
END DESCRIPTION:
Node Name=L
XS GIS Cut Line= 4
2996893.1720769413860413.62219032996949.8665173713858984.7464391
2996952.64177428 13858914.8013692996953.63291402 13858889.821104
#Sta/Elev= 30
       0   133.6  159.44  136.02  244.15  133.92  303.94  134.58  383.66   133.4
  468.36  134.33  662.68  133.56  697.56  134.85  732.44  133.61  812.16   134.8
  896.87  133.96  931.74  131.91  956.66  131.67  961.64  132.72 1016.45   134.1
 1076.24  134.35 1101.15  133.34 1131.05  133.97 1160.94  133.08 1195.82  133.99
 1355.69  134.45 1390.14  134.22  1400.1  133.01 1420.03  125.41    1430   124.1
 1439.33  125.35    1458  133.06    1486  134.52    1505  132.47    1525   133.4
#Mann= 4 ,-1 , 0
       0     .15       0 1355.69     .07       0 1390.14     .04       0
    1486     .07       0
#XS Ineff= 3 ,-1
       0 1427.24     132 1438.34    1486     132    1486    1525  134.52
Permanent Ineff=
       F       F       F
Bank Sta=1390.14,1486
XS Rating Curve= 0 ,0
Exp/Cntr=0.5,0.3

Type RM Length L Ch R = 1 ,4419.56 ,740.69,738.87,738.26
XS GIS Cut Line= 3
2997231.8029613613860381.58780552997226.73997936 13859186.600038
2997238.7343779513858905.9083422
#Sta/Elev= 30
       0  134.76      95  134.37     185  132.76     225  134.09     325  134.21
     560  132.39     590  131.27     655  131.28     730   132.6     765  132.23
     805  133.49     855  133.32     895  131.79     930  131.63     970  133.04
    1070  133.99    1150  133.38    1190  130.59 1209.79  131.08 1244.29  134.17
 1313.68  134.55  1351.2  134.85 1368.34  126.16 1387.17  123.26 1391.13   121.7
 1396.04  122.43 1397.75  124.43 1414.73  133.44 1436.52  134.72 1475.95  134.18
#Mann= 4 ,-1 , 0
       0     .15       0 1313.68     .07       0  1351.2     .04       0
 1436.52     .07       0
#XS Ineff= 2 ,-1
       0 1124.22     132 1436.52 1475.95  134.72
Permanent Ineff=
       F       F
Bank Sta=1351.2,1436.52
XS Rating Curve= 0 ,0
Exp/Cntr=0.3,0.1

Type RM Length L Ch R = 1 ,3680.687,163.78,165.13,166.28
XS GIS Cut Line= 6
2997702.9365335313860808.5525028 2997848.732173713860489.4412643
2997932.3301036113860188.1400297 2997976.109871713859387.0500964
2997973.1400613613859011.58988932997972.7755607813858828.0531829
#Sta/Elev= 30
       0  134.29   69.18  133.83  113.65  131.74  247.07  134.01   410.4  133.18
  983.28  133.44 1003.17  132.41    1038  133.93 1177.28  132.32 1222.06  133.41
 1341.45  132.97 1386.22  131.61 1435.96  132.39 1530.04  132.17 1648.61  130.19
 1688.13  133.01 1761.33  133.91 1777.06  133.07 1797.88  131.57 1826.11  119.61
 1827.79  119.98  1832.8   118.7 1835.46  120.57  1865.2  132.87 1871.04  133.16
 1900.81  132.65 1920.65  130.96 1950.41   132.5 1990.09  130.83 2024.82  131.98
#Mann= 4 ,-1 , 0
       0     .15       0 1761.33     .07       0 1777.06     .04       0
 1871.04     .07       0
#XS Ineff= 2 ,-1
       0 1454.23  130.73 1871.04 2024.82  133.16
Permanent Ineff=
       F       F
Bank Sta=1777.06,1871.04
XS Rating Curve= 0 ,0
Exp/Cntr=0.5,0.3