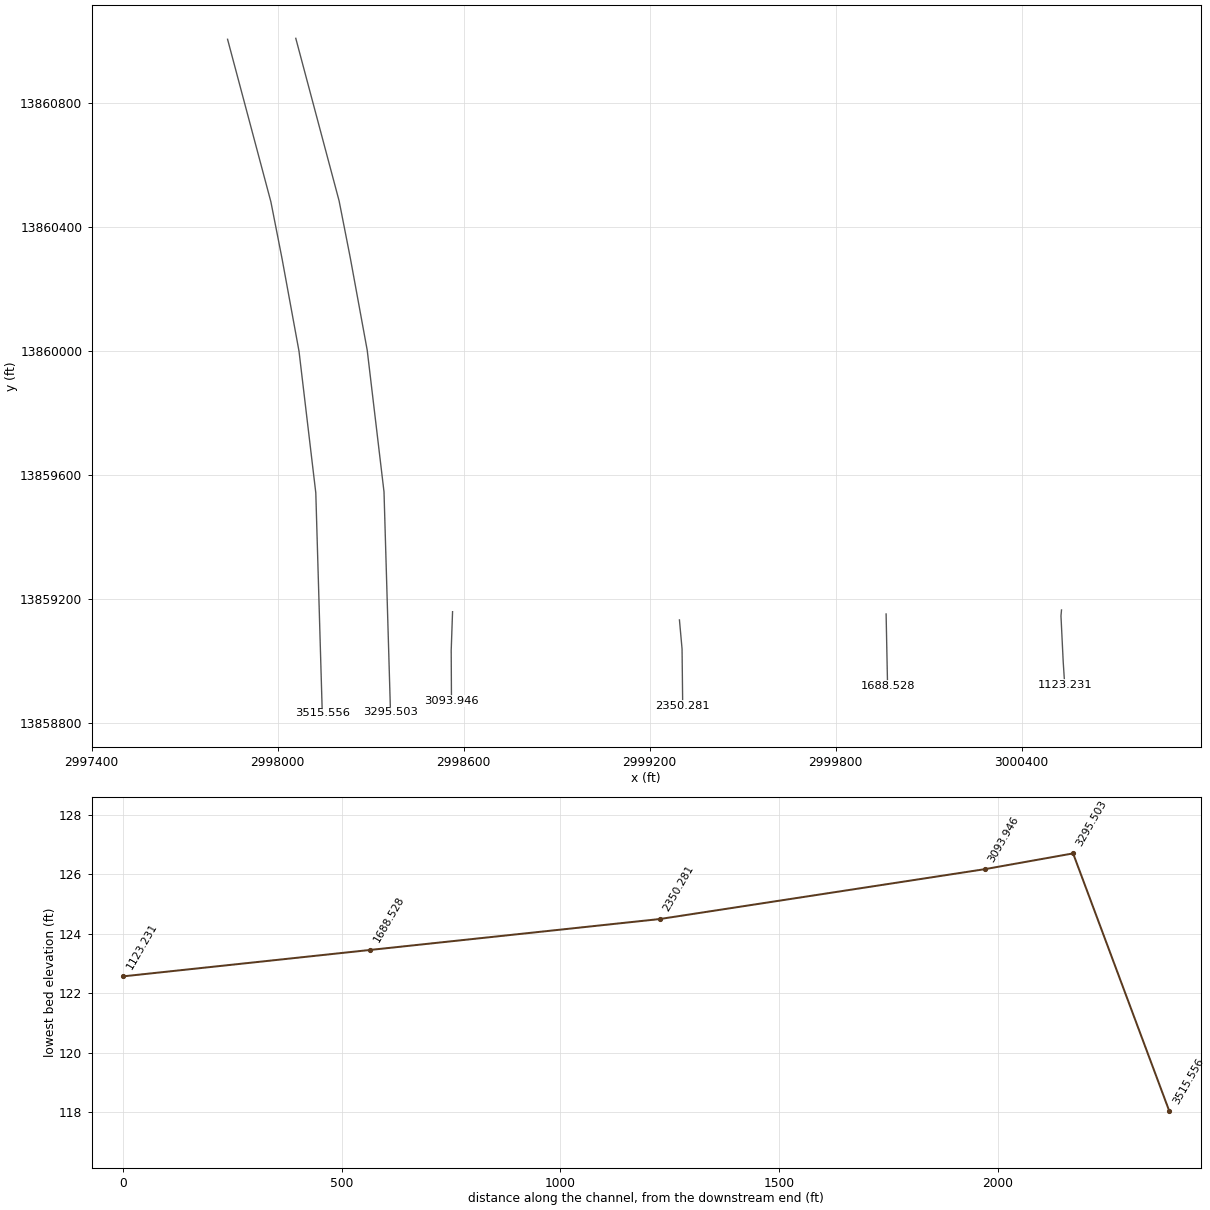
HEC-RAS study U101-07-00.prj: U101-07-00 2019 (Re-Study)

--- U101-07-00.g01 (geometry) --- (continued)

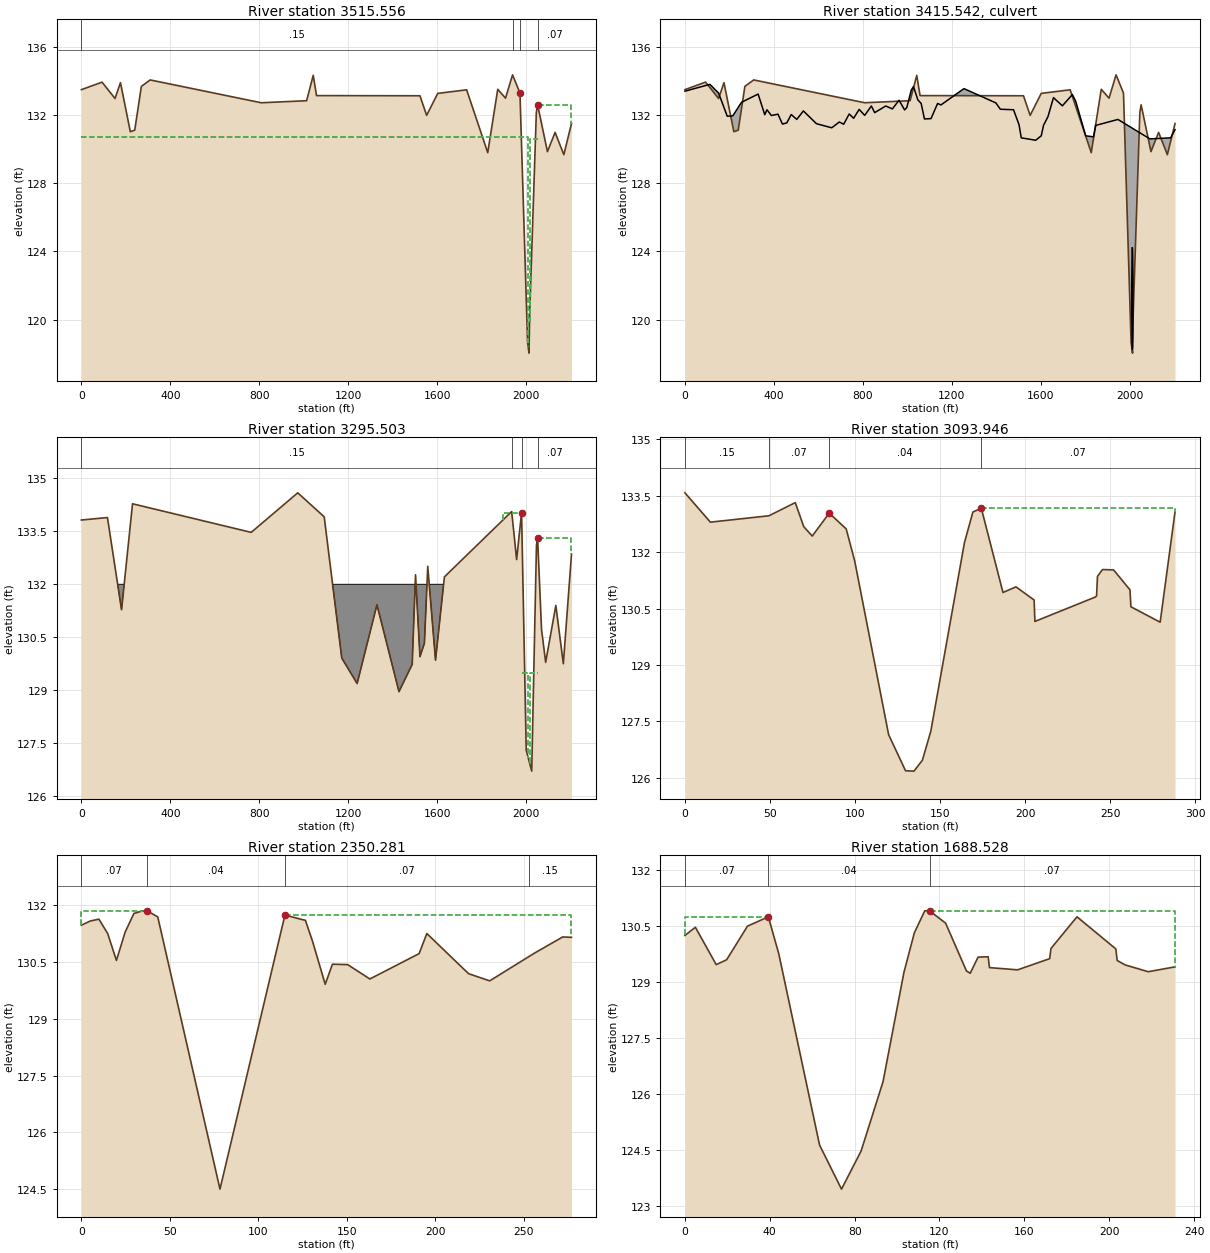
Type RM Length L Ch R = 1 ,3515.556,220.02,220.05,220.09
BEGIN DESCRIPTION:
Upstream Section - MASON RD
END DESCRIPTION:
Node Name=K
XS GIS Cut Line= 6
2997838.5022072813861005.87527092997978.26800387 13860481.499023
2998014.1330896213860298.78974282998068.9459721113859999.6883069
2998123.0820186913859542.91592642998144.0029086213858831.5813911
#Sta/Elev= 30
       0   133.5   92.71  133.94  151.27  132.98  175.67  133.91  220.01  131.03
  239.86  131.12  269.65  133.69  309.36  134.07  808.64  132.73 1013.02  132.85
 1042.83  134.34 1057.64  133.15 1522.93  133.14 1552.92  131.99  1602.9  133.28
 1732.86  133.49 1827.82   129.8 1872.81  133.52  1907.8     133 1939.36  134.37
 1972.77   133.3 2007.01  118.67 2013.48  118.03 2016.15  120.21 2046.41  132.16
 2052.11  132.61 2096.37  129.86  2130.8  130.99 2170.15  129.68 2204.58  131.51
#Mann= 4 ,-1 , 0
       0     .15       0 1939.36     .07       0 1972.77     .04       0
 2052.11     .07       0
#XS Ineff= 3 ,-1
       0  2009.7  130.73  2015.7 2052.11  130.61 2052.11 2204.58  132.61
Permanent Ineff=
       F       F       F
Bank Sta=1972.77,2052.11
XS Rating Curve= 0 ,0
Exp/Cntr=0.5,0.3

Type RM Length L Ch R = 2 ,3415.542,,,
BEGIN DESCRIPTION:
MASON RD
END DESCRIPTION:
Node Name=MASON RD
Bridge Culvert--1,0,-1,-1, 0
Deck Dist Width WeirC Skew NumUp NumDn MinLoCord MaxHiCord MaxSubmerge Is_Ogee
61,82.5,2.6,0, 60, 60, , , 0.98, 0, 0,0,,
       0  112.23  151.27   190.3  215.04  254.76  329.22  359.01  368.93  388.79
  418.58  438.43  458.29  478.15  502.97  532.76  591.68  660.28  694.58  714.18
  738.85  758.79  783.71  808.64  838.55   853.5  903.35  933.26  963.17   988.1
  998.07 1018.01 1027.98 1047.77 1062.58 1077.39    1107 1136.62 1151.43 1255.14
 1398.81 1418.63 1478.07 1502.93 1512.93 1577.91  1602.9  1612.9 1632.89 1657.88
 1697.87 1742.85 1757.85 1802.83 1837.82 1847.82 1947.78 2091.45  2184.9 2204.58
  133.41  133.81   133.3  131.94  131.96  132.76  133.24  132.03  132.32  131.98
  132.06  131.48  131.55  132.04  131.75  132.25   131.5  131.26   131.6  131.47
  132.07  131.82  132.34  131.99  132.54  132.15  132.54  132.37  132.88  132.31
  132.45  133.47  133.68   132.9  132.69  131.78   131.8  132.69   132.6  133.56
  132.72  132.35  132.32  131.44  130.67  130.53  130.79   131.4  131.91  133.03
  132.55  133.21  132.82  130.79  130.73   131.4  131.75  130.61  130.67  131.15
                                                                                
                                                                                
                                                                                
                                                                                
                                                                                
                                                                                
       0  112.23  151.27   190.3  215.04  254.76  329.22  359.01  368.93  388.79
  418.58  438.43  458.29  478.15  502.97  532.76  591.68  660.28  694.58  714.18
  738.85  758.79  783.71  808.64  838.55   853.5  903.35  933.26  963.17   988.1
  998.07 1018.01 1027.98 1047.77 1062.58 1077.39    1107 1136.62 1151.43 1255.14
 1398.81 1418.63 1478.07 1502.93 1512.93 1577.91  1602.9  1612.9 1632.89 1657.88
 1697.87 1742.85 1757.85 1802.83 1837.82 1847.82 1947.78 2091.45  2184.9 2204.58
  133.41  133.81   133.3  131.94  131.96  132.76  133.24  132.03  132.32  131.98
  132.06  131.48  131.55  132.04  131.75  132.25   131.5  131.26   131.6  131.47
  132.07  131.82  132.34  131.99  132.54  132.15  132.54  132.37  132.88  132.31
  132.45  133.47  133.68   132.9  132.69  131.78   131.8  132.69   132.6  133.56
  132.72  132.35  132.32  131.44  130.67  130.53  130.79   131.4  131.91  133.03
  132.55  133.21  132.82  130.79  130.73   131.4  131.75  130.61  130.67  131.15
                                                                                
                                                                                
                                                                                
                                                                                
                                                                                
                                                                                
BR Coef=-1 , 0 , 0 ,, 0 ,,,0.8,-1,,0,
WSPro=,,,, 1 ,,,, 0 ,,,, 0 ,,,,-1 ,-1 ,-1 , 0 , 0 , 0 , 0 , 0
Culvert=1,6,,180,0.013,0.5,1,1,3,118.25,2012.7,118.01,2012.96,Culvert #1  , 0 ,10
Culvert Bottom n=0.013
BC Design=,, 0 ,, 0 ,,,,,,
BC Use User HTab Curves=0
BC User HTab FreeFlow(D)= 0

Type RM Length L Ch R = 1 ,3295.503,204.28,201.56,200.88
BEGIN DESCRIPTION:
Downstream Section - MASON RD
END DESCRIPTION:
Node Name=J
XS GIS Cut Line= 6
2998058.5240769413861008.96384742998198.2898735313860484.5875995
2998234.1549592813860301.87831932998288.9678417713860002.7768833
2998343.1038883613859546.00450292998364.0247782813858834.6699676
#Sta/Elev= 30
       0  133.82  117.11  133.89  180.55  131.28  229.93  134.28  763.77  133.47
  973.14  134.59  1092.2  133.91 1171.17  129.91 1240.28  129.19 1329.45  131.42
 1428.53  128.96 1487.98  129.73 1502.93  132.27 1522.93  129.95 1542.92  130.33
 1557.91  132.51  1592.9  129.85 1632.89  132.21 1935.47  134.06 1957.78   132.7
 1979.96  134.03 2000.95   127.3 2025.66  126.71 2046.93   133.1 2052.11   133.3
 2069.85  130.72 2088.36  129.79  2134.1   131.4 2167.93  129.75 2204.58  132.85
#Mann= 4 ,-1 , 0
       0     .15       0 1935.47     .07       0 1979.96     .04       0
 2052.11     .07       0
#XS Ineff= 5 ,-1
       0  1897.8     132  1897.8 1979.96  134.03 1979.96 2009.96   129.5
 2015.96 2052.11   129.5 2052.11 2204.58   133.3
Permanent Ineff=
       F       F       F       F       F
#Block Obstruct= 2 , 0
       0  1897.8     132               0
Bank Sta=1979.96,2052.11
XS Rating Curve= 0 ,0
Exp/Cntr=0.5,0.3

Type RM Length L Ch R = 1 ,3093.946,738.64,743.67,745.08
XS GIS Cut Line= 3
2998564.2271337813859159.58565642998559.8498459513859034.8900396
2998560.7146736113858871.4792772
#Sta/Elev= 30
       0  133.58   14.97   132.8   49.42  132.97   64.88  133.32   69.87  132.68
   74.86  132.43   84.85  133.04   94.83  132.62   99.82  131.77  119.78  127.15
  129.72  126.19  134.68  126.18  139.63  126.47  144.58  127.24  164.39  132.26
  169.34  133.07  174.29  133.17  187.03  130.93  194.66  131.08  205.34  130.73
  205.79  130.16   241.4  130.81  242.05  130.84   242.6  131.36  245.55  131.54
  252.08  131.53  261.71     131  262.24  130.55  279.46  130.14  288.19  133.07
#Mann= 4 ,-1 , 0
       0     .15       0   49.42     .07       0   84.85     .04       0
  174.29     .07       0
#XS Ineff= 2 , 0
       0   84.85  133.04  174.29       0  133.17
Permanent Ineff=
       F       F
Bank Sta=84.85,174.29
XS Rating Curve= 0 ,0
Exp/Cntr=0.3,0.1

Type RM Length L Ch R = 1 ,2350.281,664.35,661.75,660.64
Node Name=I
XS GIS Cut Line= 3
 2999296.041943113859132.96858362999304.4904170313859039.3677209
2999306.5586543513858856.3808822
#Sta/Elev= 28
       0  131.47    4.95  131.58    9.89  131.63   14.84  131.25   19.79  130.54
   24.73  131.29   29.68  131.78   34.62  131.85   37.12  131.85   43.14  131.69
   78.31   124.5   93.98  127.59  115.03  131.74  124.66  131.62  126.59   131.6
  130.66  131.04  137.79  129.91  141.87  130.44  150.46  130.43  163.02  130.05
  190.87  130.72  195.22  131.25  218.82  130.19  230.76     130  252.81 130.639
  255.95  130.73  272.03  131.16  276.98  131.15
#Mann= 4 ,-1 , 0
       0     .07       0   37.12     .04       0  115.03     .07       0
  252.81     .15       0
#XS Ineff= 2 , 0
       0   37.12  131.85  115.03       0  131.74
Permanent Ineff=
       F       F
Bank Sta=37.12,115.03
XS Rating Curve= 0 ,0
Exp/Cntr=0.3,0.1

Type RM Length L Ch R = 1 ,1688.528,564.1,565.3,566.36
Node Name=H
XS GIS Cut Line= 2
2999962.6616728613859152.1821278 2999967.336204213858921.1963694
#Sta/Elev= 30
       0  130.25    4.92  130.47   14.75  129.47   19.66   129.6   29.49   130.5
   39.32  130.75   44.24  129.76   63.47  124.64   73.81  123.46   83.05  124.48
    93.4  126.34  103.23  129.26  108.14  130.32  113.06  130.91  115.32  130.91
  122.89  130.58  132.72   129.3  134.49  129.24  138.18  129.67  142.96  129.68
  143.55  129.39  156.82  129.33  171.95  129.63  172.53   129.9  184.82  130.75
  203.13  129.89  203.77  129.58  207.62  129.46   218.4  129.28  231.03  129.41
#Mann= 3 ,-1 , 0
       0     .07       0   39.32     .04       0  115.32     .07       0
#XS Ineff= 2 , 0
       0   39.32  130.75  115.32       0  130.91
Permanent Ineff=
       F       F
Bank Sta=39.32,115.32
XS Rating Curve= 0 ,0
Exp/Cntr=0.3,0.1

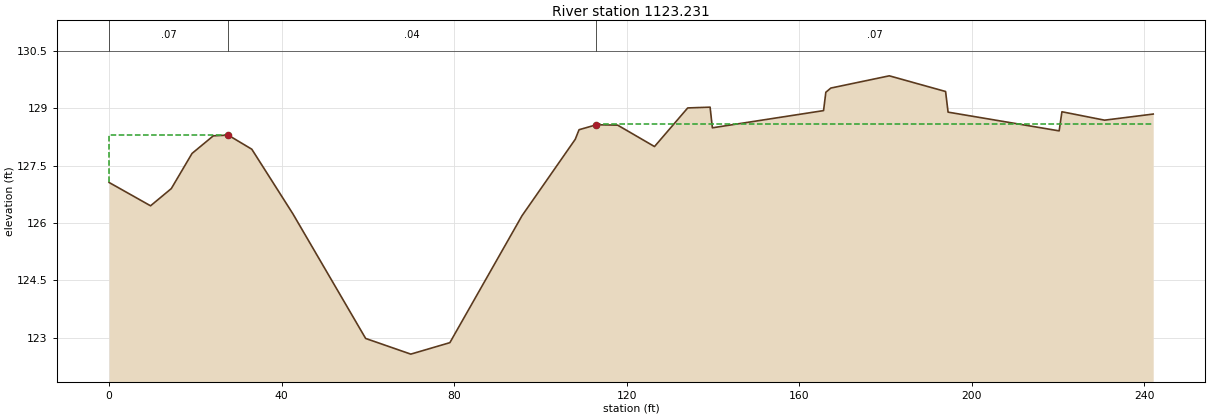
Type RM Length L Ch R = 1 ,1123.231,5.03,5.03,5.03
Node Name=G
XS GIS Cut Line= 4
3000528.4338352813859165.10368993000526.69236894  13859145.95445
3000533.8954385213858998.07219993000538.7468067713858923.3856694
#Sta/Elev= 30
       0  127.06    9.61  126.45   14.42   126.9   19.23  127.82   24.16  128.28
    27.6   128.3   33.09  127.93   42.62  126.24   59.49  122.98   69.96  122.57
   79.02  122.87   95.75  126.19   108.1  128.19  108.98  128.44     113  128.57
  117.93  128.56  126.48     128  134.18  129.01  139.37  129.03   139.9  128.49
  165.68  128.94  166.21  129.42  167.37  129.53  180.93  129.85  193.98  129.44
  194.56   128.9  220.32  128.41  220.96  128.91  230.85  128.69  242.13  128.85
#Mann= 3 ,-1 , 0
       0     .07       0    27.6     .04       0     113     .07       0
#XS Ineff= 2 , 0
       0    27.6   128.3     113       0  128.58
Permanent Ineff=
       F       F
Bank Sta=27.6,113
XS Rating Curve= 0 ,0
Exp/Cntr=0.3,0.1