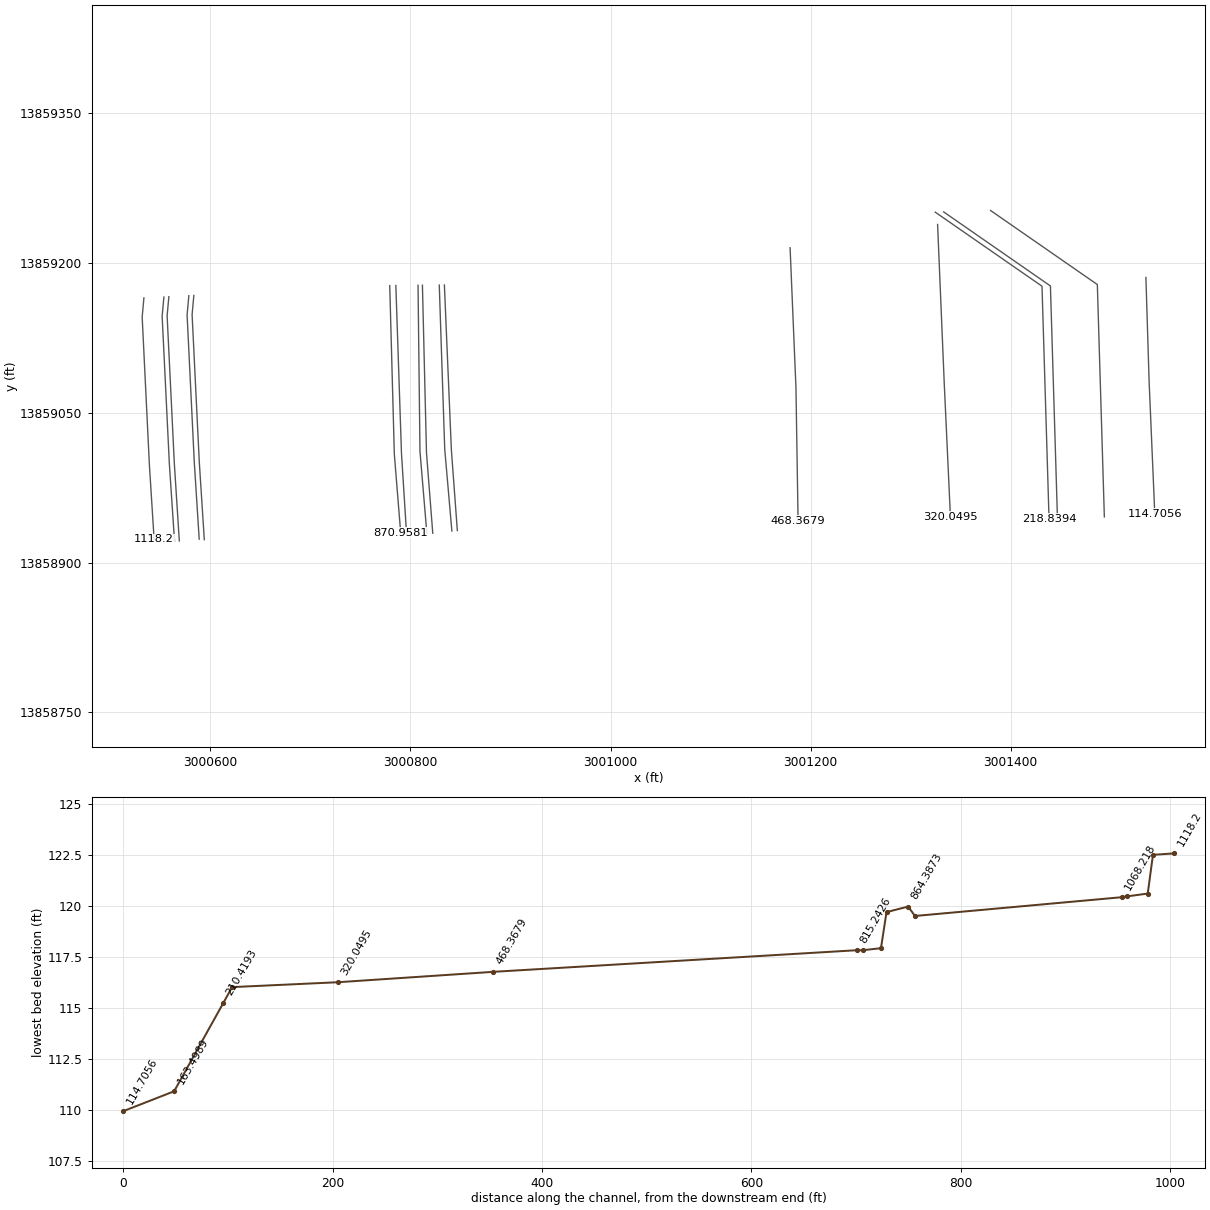
HEC-RAS study U101-07-00.prj: U101-07-00 2019 (Re-Study)

--- U101-07-00.g01 (geometry) --- (continued)

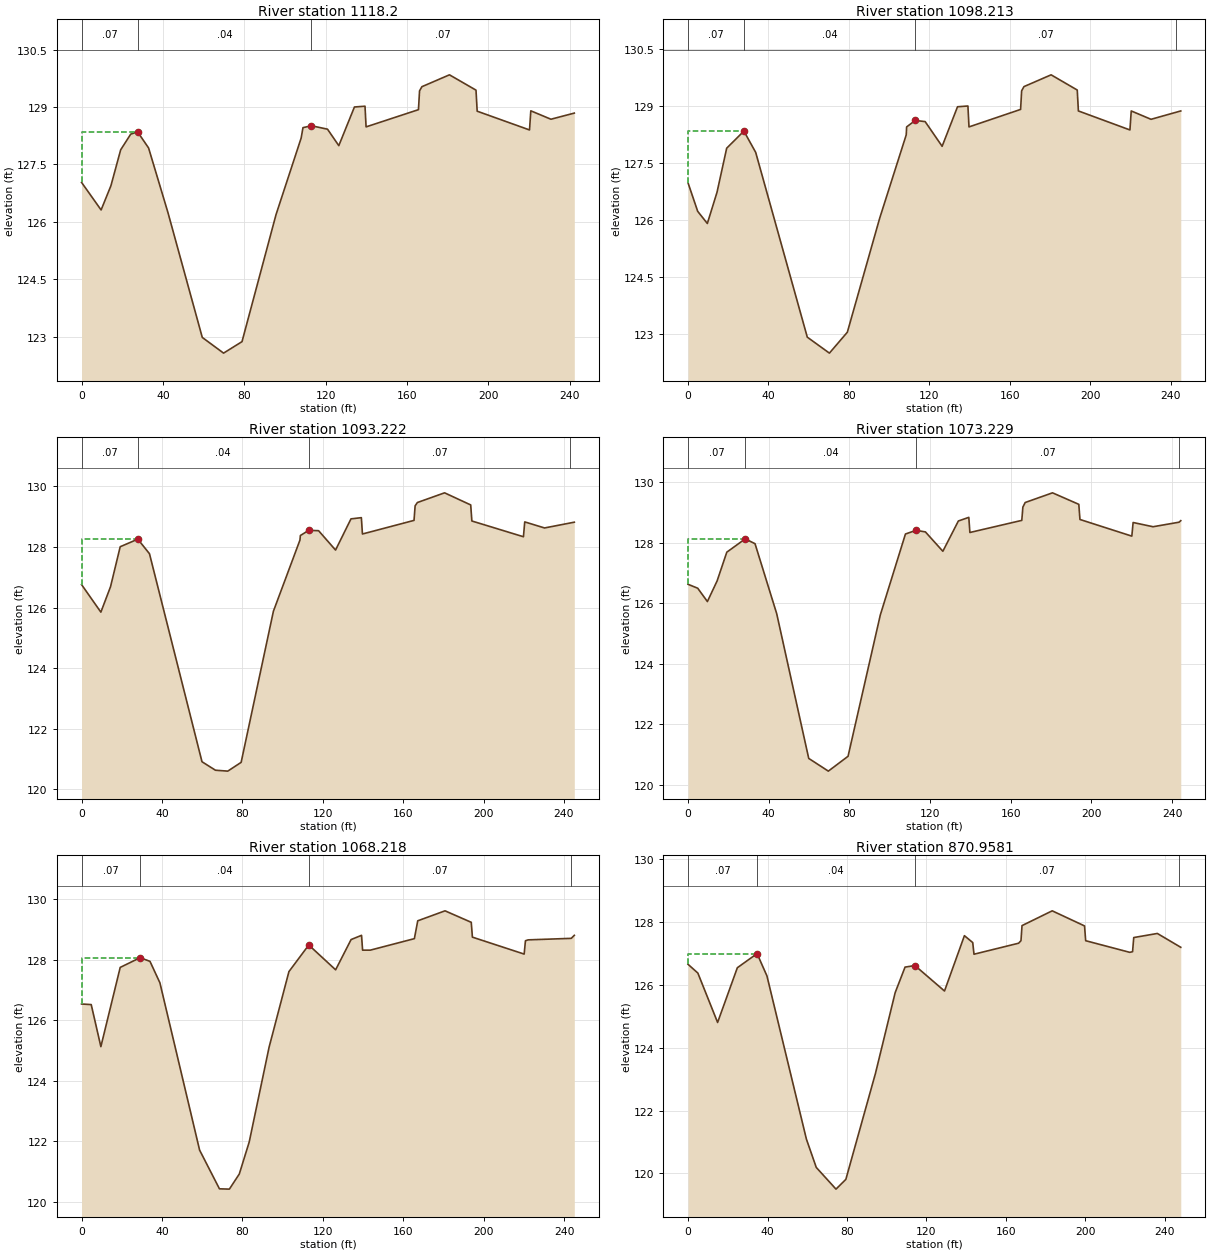
Type RM Length L Ch R = 1 ,1118.2  ,19.99,19.99,19.99
XS GIS Cut Line= 4
3000533.4656493713859165.20900473000531.7241830213859146.0597648
3000538.9272526113858998.17751463000543.6591985213858923.3856694
#Sta/Elev= 30
       0  127.03    9.61  126.31   14.42  126.94   19.23  127.88   24.16  128.29
   27.55  128.35   32.95  127.93   42.48  126.24   59.35  122.98   69.82  122.57
   78.88  122.87   95.61  126.19  107.96  128.19  108.85  128.46     113  128.51
  120.91  128.42  126.46  127.99  134.15     129  139.34  129.02  139.87  128.48
  165.62  128.93  166.15  129.42  167.31  129.53  180.86  129.84   193.9  129.44
  194.48  128.89  220.21   128.4  220.85   128.9  230.74  128.68  242.23  128.84
#Mann= 3 ,-1 , 0
       0     .07       0   27.55     .04       0     113     .07       0
#XS Ineff= 2 , 0
       0   27.55  128.35     113       0  128.51
Permanent Ineff=
       F       F
Bank Sta=27.55,113
XS Rating Curve= 0 ,0
Exp/Cntr=0.3,0.1

Type RM Length L Ch R = 1 ,1098.213,4.99,4.99,4.99
XS GIS Cut Line= 4
3000553.4347695313859166.0518508 3000551.693303213859146.9029389
3000558.8963727813858999.02036073000564.0902600313858921.4102797
#Sta/Elev= 30
       0  126.98    4.81  126.23    9.61  125.91   14.42  126.73   19.23  127.89
   27.79  128.34   33.66  127.78   59.32  122.92   70.32   122.5   79.24  123.05
   95.33  126.05  108.52  128.24  108.73  128.45     113  128.62  117.93  128.59
  126.38  127.94  134.04  128.98  139.21     129  139.74  128.45   165.4  128.91
  165.93   129.4  167.08  129.51  180.58  129.82  193.58  129.42  194.15  128.87
  219.79  128.37  220.43  128.87  230.28  128.65  242.94128.8383  245.07  128.87
#Mann= 4 ,-1 , 0
       0     .07       0   27.79     .04       0     113     .07       0
  242.94     .15       0
#XS Ineff= 2 , 0
       0   27.79  128.34     113       0  128.62
Permanent Ineff=
       F       F
Bank Sta=27.79,113
XS Rating Curve= 0 ,0
Exp/Cntr=0.3,0.1

Type RM Length L Ch R = 1 ,1093.222,20,19.99,19.99
Node Name=F
XS GIS Cut Line= 4
 3000558.413762213859166.42061643000556.6726239513859147.2717046
3000563.8753654513858999.38912633000568.8661691113858921.6845573
#Sta/Elev= 30
       0  126.76    9.61  125.85   14.42  126.69   19.23  128.01      28  128.26
   33.79  127.78   59.92  120.91   66.61  120.63   72.75   120.6    79.4  120.89
   95.45  125.88  108.66  128.23  108.86  128.38     113  128.55  117.92  128.54
  126.37   127.9  134.04  128.93  139.21  128.97  139.74  128.43  165.41  128.88
  165.95  129.36  167.09  129.47  180.61  129.79  193.61  129.39  194.18  128.86
  219.84  128.34  220.49  128.83  230.34  128.63  243.14128.7944  245.15  128.82
#Mann= 4 ,-1 , 0
       0     .07       0      28     .04       0     113     .07       0
  243.14     .15       0
#XS Ineff= 2 , 0
       0      28  128.26     113       0  128.55
Permanent Ineff=
       F       F
Bank Sta=28,113
XS Rating Curve= 0 ,0
Exp/Cntr=0.3,0.1

Type RM Length L Ch R = 1 ,1073.229,5.01,5.01,5.01
XS GIS Cut Line= 4
3000578.3832104513859167.39568013000576.6417441113859148.2464402
3000583.84481369  13859000.364193000588.7476910213858923.4762204
#Sta/Elev= 30
       0  126.63    4.81   126.5    9.61  126.06   14.42  126.74   19.23  127.69
   28.37  128.13   33.23  127.97   43.97  125.66   59.85  120.88   69.58  120.46
   79.35  120.95   95.36  125.62  107.81  128.29     113  128.41   117.7  128.36
  126.36  127.72  134.05  128.72  139.23  128.84  139.76  128.34   165.5  128.74
  166.04  129.18  167.18  129.33  180.73  129.65  193.77  129.27  194.34  128.77
  220.06  128.22   220.7  128.67  230.59  128.53  243.47  128.68  244.33  128.73
#Mann= 4 ,-1 , 0
       0     .07       0   28.37     .04       0     113     .07       0
  243.47     .15       0
#XS Ineff= 2 , 0
       0   28.37  128.13     113       0  128.41
Permanent Ineff=
       F       F
Bank Sta=28.37,113
XS Rating Curve= 0 ,0
Exp/Cntr=0.3,0.1

Type RM Length L Ch R = 1 ,1068.218,198.12,197.26,196.5
XS GIS Cut Line= 4
3000583.3884497713859167.63255633000581.6473115213859148.4836444
3000588.8500530313859000.60106623000593.8408566913858922.9844235
#Sta/Elev= 30
       0  126.54    4.81  126.52    9.61  125.13   19.23  127.75    29.1  128.07
   34.03  127.95   38.97  127.24   58.71  121.71   68.58  120.43   73.52  120.42
   78.45  120.92   83.39  121.98   93.26  125.11  103.13  127.61     113  128.49
  126.36  127.67  134.05  128.67  139.24  128.81  139.77  128.32   143.6  128.32
  165.52   128.7   167.2  129.29  180.77  129.62  193.81  129.24  194.38  128.75
  220.12  128.19  220.76  128.63  222.07  128.66  243.54  128.71  245.06  128.81
#Mann= 4 ,-1 , 0
       0     .07       0    29.1     .04       0     113     .07       0
  243.54     .15       0
#XS Ineff= 2 , 0
       0    29.1  128.07     113       0  128.49
Permanent Ineff=
       F       F
Bank Sta=29.1,113
XS Rating Curve= 0 ,0
Exp/Cntr=0.3,0.1

Type RM Length L Ch R = 1 ,870.9581,6.32,6.57,6.78
Node Name=E
XS GIS Cut Line= 3
 3000779.245997713859177.51508243000783.8385081913859008.7818241
3000790.1918419513858929.8502234
#Sta/Elev= 30
       0  126.65    4.96  126.37   14.89   124.8   24.82  126.54   34.75  126.99
   39.72  126.28   59.58  121.09   64.54  120.19   74.47   119.5   79.43  119.81
   94.33  123.18  104.26  125.75  109.22  126.56  114.19  126.61  129.08   125.8
   139.1  127.56  143.29  127.34  143.91  126.97  166.37  127.32  167.56   127.4
  168.09  127.88  183.28  128.35  199.55  127.87  200.12   127.4  222.31  127.03
  223.72  127.05  224.31   127.5  236.19  127.63     247127.2266  247.98  127.19
#Mann= 4 ,-1 , 0
       0     .07       0   34.75     .04       0  114.19     .07       0
     247     .15       0
#XS Ineff= 2 , 0
       0   34.75  126.99  114.19       0  126.61
Permanent Ineff=
       F       F
Bank Sta=34.75,114.19
XS Rating Curve= 0 ,0
Exp/Cntr=0.3,0.1

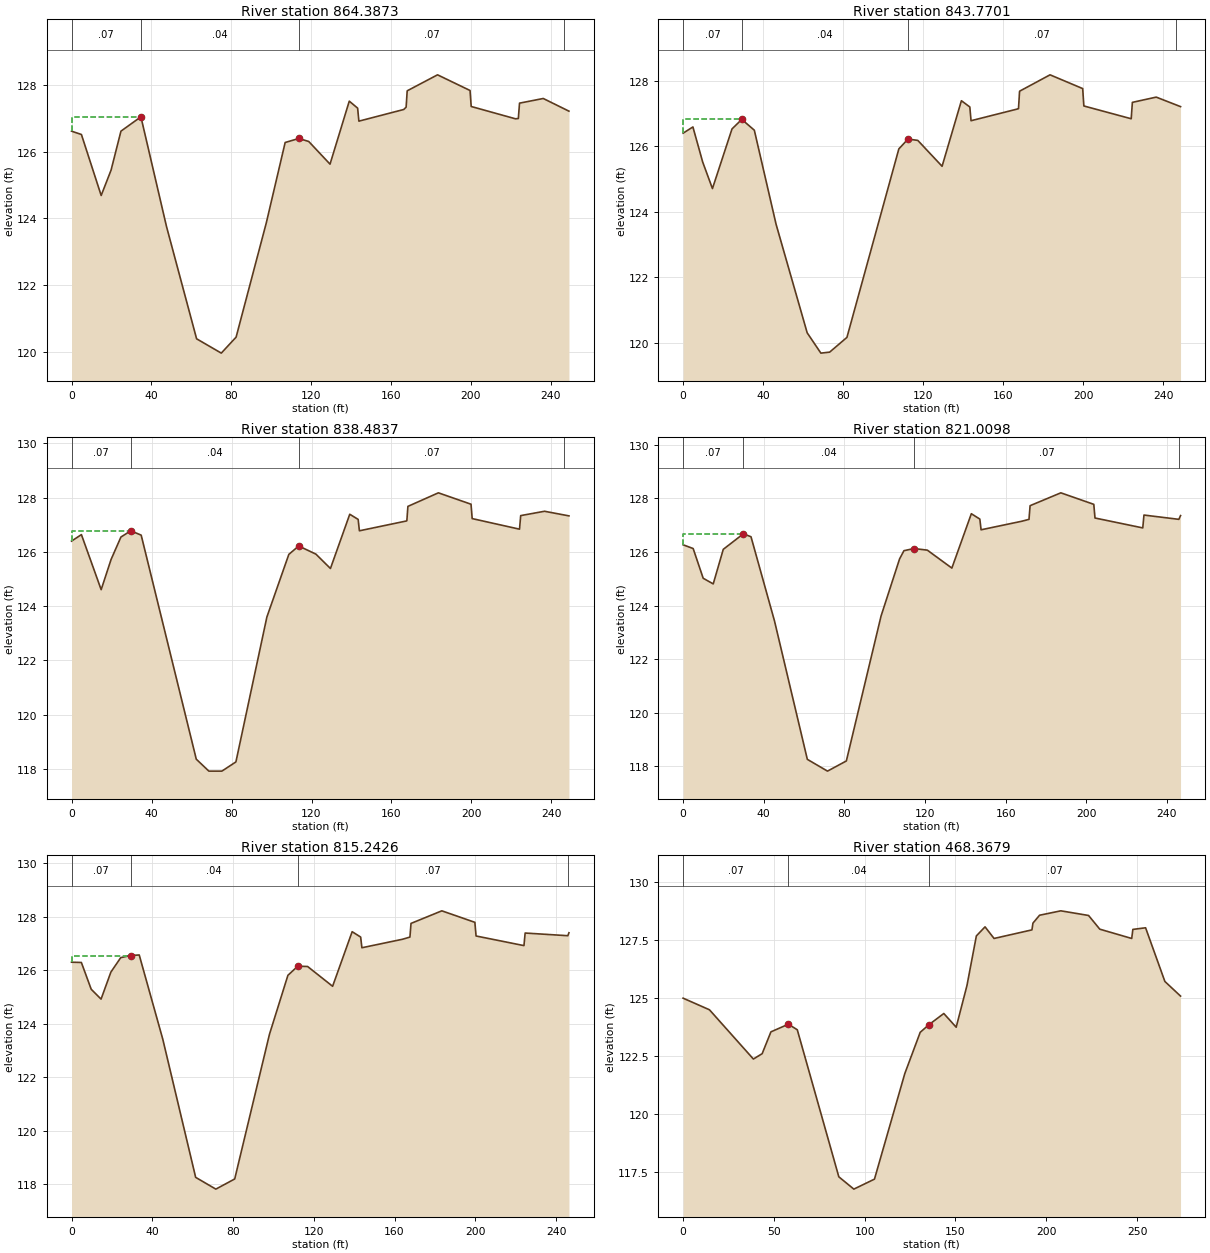
Type RM Length L Ch R = 1 ,864.3873,21.48,20.62,19.88
XS GIS Cut Line= 3
3000785.3657361113859177.58299573000790.9963022813859009.3697494
3000796.0756884413858928.6947139
#Sta/Elev= 30
       0  126.62    4.95  126.52   14.85  124.69    19.8  125.45   24.75  126.62
   34.75  127.05   47.56  123.76   62.64  120.39   75.01  119.96   82.43  120.44
   97.56  123.87     107  126.28  113.86   126.4  118.81  126.31  129.47  125.63
  139.11  127.52   143.3  127.31  143.92  126.92   166.4  127.27  167.59  127.34
  168.12  127.83  183.32  128.31   199.6  127.84  200.18  127.36  222.38  126.99
  223.79     127  224.38  127.46  236.27   127.6  246.81127.2888  249.14  127.22
#Mann= 4 ,-1 , 0
       0     .07       0   34.75     .04       0  113.86     .07       0
  246.81     .15       0
#XS Ineff= 2 , 0
       0   34.75  127.05  113.86       0   126.4
Permanent Ineff=
       F       F
Bank Sta=34.75,113.86
XS Rating Curve= 0 ,0
Exp/Cntr=0.3,0.1

Type RM Length L Ch R = 1 ,843.7701,4.79,5.29,5.71
XS GIS Cut Line= 3
3000807.5481064513859177.8297144 3000809.474283713859011.6423827
3000816.3545192813858929.4348699
#Sta/Elev= 30
       0   126.4    4.89  126.59    9.78  125.52   14.66  124.71   24.44  126.53
   29.33  126.82    35.6  126.49   46.48  123.62   62.02  120.31   68.87  119.69
   73.25  119.72    81.9  120.17  107.85  125.92  112.43  126.22  117.32  126.18
  129.47  125.39  139.13  127.39  143.33   127.2  143.95  126.78  167.32  127.14
  167.68  127.15  168.21  127.68  183.45  128.18  199.77  127.76  200.35  127.23
  224.02  126.84  224.61  127.34  236.53   127.5  246.45127.2634  248.69  127.21
#Mann= 4 ,-1 , 0
       0     .07       0   29.33     .04       0  112.43     .07       0
  246.45     .15       0
#XS Ineff= 2 , 0
       0   29.33  126.82  112.43       0  126.22
Permanent Ineff=
       F       F
Bank Sta=29.33,112.43
XS Rating Curve= 0 ,0
Exp/Cntr=0.3,0.1

Type RM Length L Ch R = 1 ,838.4837,17.11,17.47,17.78
Node Name=D
XS GIS Cut Line= 3
3000811.9349086913859177.87827073000815.9942837813859009.9973729
3000822.2754391913858929.4348699
#Sta/Elev= 30
       0   126.4    4.94  126.64   14.82  124.61   19.76  125.72    24.7  126.55
   29.63  126.78   34.83  126.62   62.38  118.36   68.68  117.92   75.19  117.92
    82.2  118.26   97.68   123.6  108.66  125.91   113.6  126.22  122.21  125.92
  129.47  125.39  139.13  127.39  143.33   127.2  143.95  126.78  167.32  127.14
  167.68  127.15  168.21  127.68  183.45  128.18  199.77  127.76  200.35  127.23
  224.02  126.84  224.61  127.34  236.53   127.5   246.3 127.364  248.74  127.33
#Mann= 4 ,-1 , 0
       0     .07       0   29.63     .04       0   113.6     .07       0
   246.3     .15       0
#XS Ineff= 2 , 0
       0   29.63  126.78   113.6       0  126.22
Permanent Ineff=
       F       F
Bank Sta=29.63,113.6
XS Rating Curve= 0 ,0
Exp/Cntr=0.3,0.1

Type RM Length L Ch R = 1 ,821.0098,5.41,5.77,6.07
XS GIS Cut Line= 3
3000828.7655836913859178.0652782 3000834.225874613859013.8057642
3000841.3702172813858931.6553379
#Sta/Elev= 30
       0  126.27    4.98  126.13    9.96  125.02   14.94  124.81   19.92   126.1
   29.88  126.68   33.68  126.57   45.36  123.42   61.63  118.26   71.64  117.82
   80.99   118.2   98.21  123.61  107.39  125.74  109.57  126.05  114.55  126.13
  121.17  126.07  133.34   125.4  143.01  127.43  147.22  127.23  147.84  126.83
  168.09  127.15  171.62  127.22  172.16  127.73  187.42  128.21  203.77  127.78
  204.36  127.27  228.07   126.9  228.66  127.38  245.98  127.22  246.81  127.36
#Mann= 4 ,-1 , 0
       0     .07       0   29.88     .04       0  114.55     .07       0
  245.98     .15       0
#XS Ineff= 2 , 0
       0   29.88  126.68  114.55       0  126.13
Permanent Ineff=
       F       F
Bank Sta=29.88,114.55
XS Rating Curve= 0 ,0
Exp/Cntr=0.3,0.1

Type RM Length L Ch R = 1 ,815.2426,346.91,346.87,346.86
XS GIS Cut Line= 3
3000833.8974631913859178.12236473000840.8931841113859012.6213834
3000846.8469123513858932.0992347
#Sta/Elev= 30
       0   126.3    4.87  126.29    9.74  125.29   14.62  124.92   19.49  125.93
   24.36  126.47   29.23  126.55   33.53  126.57   45.21  123.42   61.48  118.26
   71.48  117.82   80.83   118.2   98.06  123.61  107.18  125.81  112.06  126.15
  116.93  126.14  129.32   125.4     139  127.44  143.21  127.24  143.83  126.84
  164.09  127.16  167.62  127.24  168.16  127.75  183.43  128.22  199.79  127.79
  200.38  127.28   224.1  126.92  224.69  127.39  245.83  127.29  246.39   127.4
#Mann= 4 ,-1 , 0
       0     .07       0   29.23     .04       0  112.06     .07       0
  245.83     .15       0
#XS Ineff= 2 , 0
       0   29.23  126.55  112.06       0  126.15
Permanent Ineff=
       F       F
Bank Sta=29.23,112.06
XS Rating Curve= 0 ,0
Exp/Cntr=0.3,0.1

Type RM Length L Ch R = 1 ,468.3679,148.33,148.32,148.32
XS GIS Cut Line= 3
3001179.5490028613859215.43396993001185.4052903713859075.3187645
3001187.5352073613858941.6205411
#Sta/Elev= 30
       0  124.98   14.51  124.48   38.69  122.36   43.52  122.59   48.36  123.53
   57.97  123.86   62.87  123.62   85.75  117.29   94.02  116.76  105.38  117.19
  122.07  121.73  130.57  123.51   135.4  123.84  143.57  124.32  150.39  123.73
  156.31  125.52   161.5  127.66  166.28  128.05  171.25  127.55  192.11  127.92
  192.66  128.21   196.3  128.55  208.03  128.74  223.29  128.54  229.48  127.95
  247.06  127.55  247.69  127.94   254.7  128.01  265.32   125.7  273.95  125.07
#Mann= 3 ,-1 , 0
       0     .07       0   57.97     .04       0   135.4     .07       0
#XS Ineff= 2 , 0
       0   57.97  123.86   135.4       0  123.84
Permanent Ineff=
       F       F
Bank Sta=57.97,135.4
XS Rating Curve= 0 ,0
Exp/Cntr=0.3,0.1

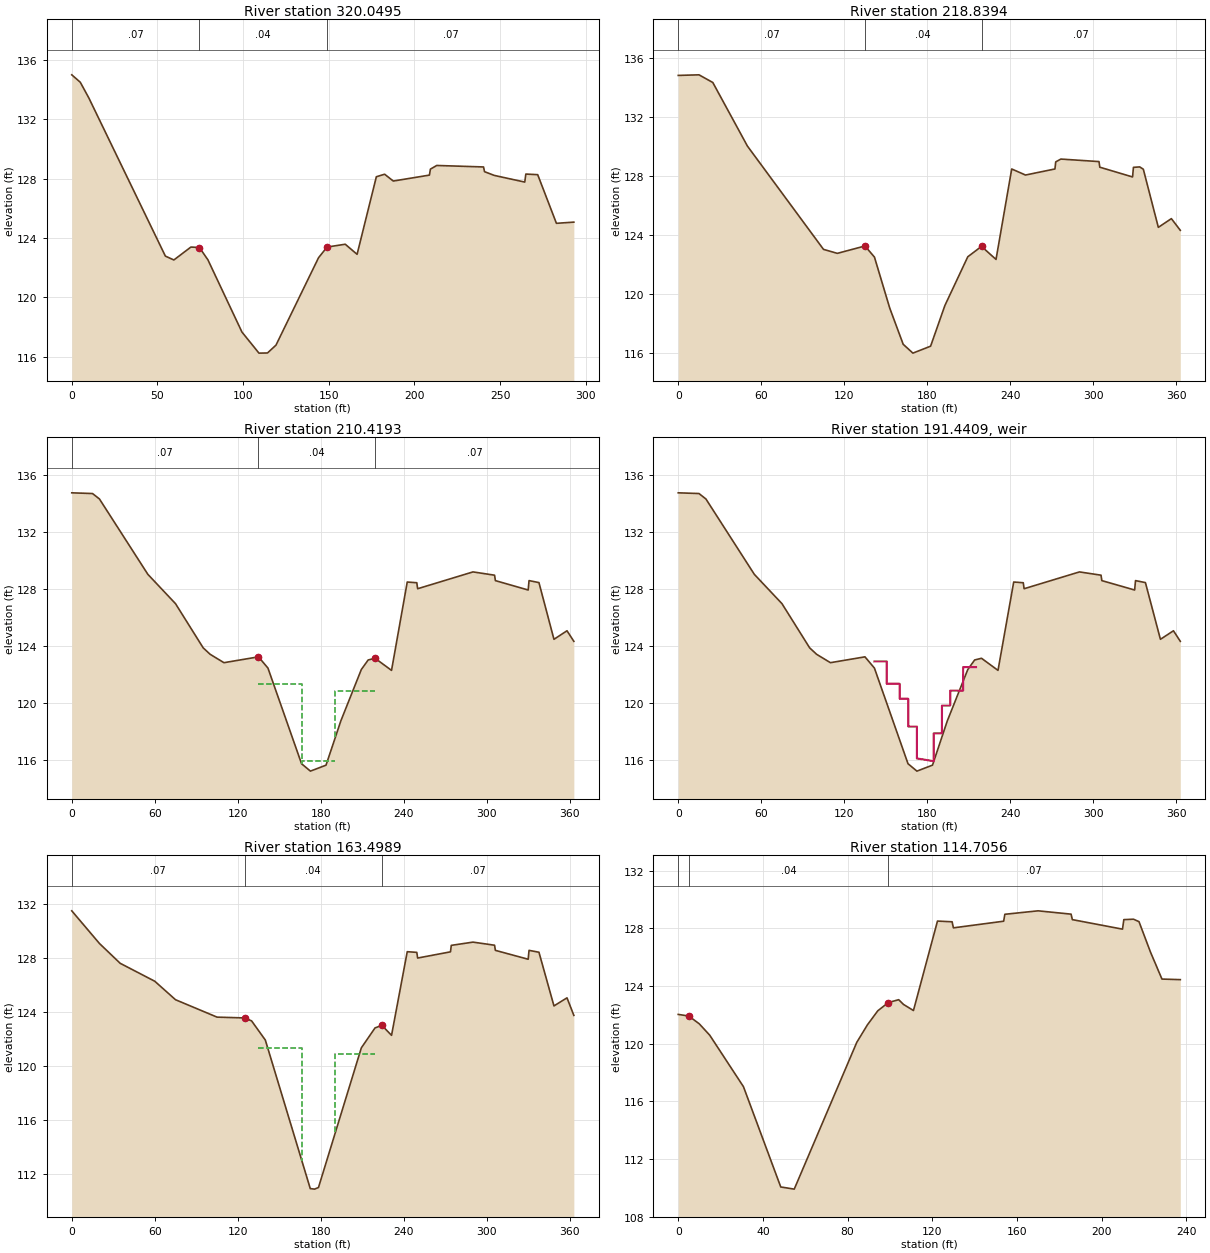
Type RM Length L Ch R = 1 ,320.0495,101.6,101.21,100.83
XS GIS Cut Line= 3
3001327.0211488613859238.77545863001333.6586027713859079.9709862
3001339.8541284513858945.9952043
#Sta/Elev= 30
       0  135.01    4.97  134.51    9.93  133.46   54.64  122.79    59.6  122.53
   69.54   123.4    74.5  123.37   79.47  122.54   99.34  117.67  109.27  116.25
  114.24  116.26  119.21  116.79  144.04  122.68  149.01   123.4  159.63  123.59
  166.54  122.91  177.79  128.14  182.62  128.31  187.66  127.85  208.77  128.25
  209.33  128.65  213.02   128.9  240.34   128.8  240.93  128.48  246.61  128.23
  264.41  127.78  265.04  128.32  271.96  128.28  282.89     125  293.06  125.08
#Mann= 3 ,-1 , 0
       0     .07       0    74.5     .04       0  149.01     .07       0
#XS Ineff= 2 , 0
       0    74.5  123.37  149.01       0   123.4
Permanent Ineff=
       F       F
Bank Sta=74.5,149.01
XS Rating Curve= 0 ,0
Exp/Cntr=0.3,0.1

Type RM Length L Ch R = 1 ,218.8394,8.42,8.42,8.42
XS GIS Cut Line= 3
3001324.6710879513859251.11631323001431.4195621213859176.9222358
3001438.44185777 13858944.124145
#Sta/Elev= 30
       0   134.8      15  134.84      25  134.32      50  130.02     105  123.03
     115  122.76  134.96  123.26  141.82  122.51  152.87  119.06  162.59  116.61
  169.62  116.01  182.41  116.48  192.73  119.23  209.29  122.53   219.2  123.23
   229.7  122.35  241.04  128.47     251  128.06  272.28  128.47  272.85  128.95
  276.57  129.14  304.12  128.97  304.71  128.59  328.39  127.93  329.02  128.58
  333.57  128.61  336.18  128.45  347.02  124.52  356.44  125.11   362.9  124.32
#Mann= 3 ,-1 , 0
       0     .07       0  134.96     .04       0   219.2     .07       0
#XS Ineff= 2 , 0
       0  134.96  123.26   219.2       0  123.23
Permanent Ineff=
       F       F
Bank Sta=134.96,219.2
XS Rating Curve= 0 ,0
Exp/Cntr=0.5,0.3

Type RM Length L Ch R = 1 ,210.4193,46.92,46.92,46.92
BEGIN DESCRIPTION:
Upstream Section - INLINE WEIR
END DESCRIPTION:
Node Name=C
XS GIS Cut Line= 3
3001333.0867535313859251.3702497 3001439.835227713859177.1761723
3001446.8575233713858944.3780815
#Sta/Elev= 30
       0  134.76      15  134.71      20  134.33      55  129.04      75  126.98
      95  123.88     100  123.43     110  122.84  134.96  123.25  141.81  122.46
  166.08  115.75  172.51  115.23  183.79  115.65  194.42  118.74  209.29  122.36
  214.24  123.03   219.2  123.15  231.13   122.3  242.48   128.5  249.39  128.45
     250  128.03  290.01  129.21   305.6  128.98  306.19   128.6  329.89  127.94
  330.52   128.6  337.68  128.46  348.53  124.48  357.95  125.08   362.9  124.34
#Mann= 3 ,-1 , 0
       0     .07       0  134.96     .04       0   219.2     .07       0
#XS Ineff= 3 ,-1
  134.96  166.28  121.36  166.28  190.61  115.93  190.61   219.2  120.88
Permanent Ineff=
       F       F       F
Bank Sta=134.96,219.2
XS Rating Curve= 0 ,0
Exp/Cntr=0.5,0.3

Type RM Length L Ch R = 5 ,191.4409,,,
BEGIN DESCRIPTION:
INLINE WEIR
END DESCRIPTION:
Node Name=INLINE WEIR
IW Pilot Flow=0
#Inline Weir SE= 18
   141.8  122.93   150.7  122.93  150.71  121.36  160.05  121.36  160.06  120.31
  166.28  120.31  166.29  118.36  172.51  118.36  172.52  116.12  184.61  115.93
  184.62  117.88  190.61  117.88  190.62  119.83  196.61  119.83  196.62  120.88
  205.91  120.88  205.92  122.53  215.22  122.53
IW Dist,WD,Coef,Skew,MaxSub,Min_El,Is_Ogee,SpillHt,DesHd
17,2,2.6,0,0.98,, 0 ,,,0,0,

Type RM Length L Ch R = 1 ,163.4989,48.77,48.79,48.82
BEGIN DESCRIPTION:
Downstream Section - INLINE WEIR
END DESCRIPTION:
Node Name=B
XS GIS Cut Line= 3
3001379.98593794 13859252.784945 3001486.734412113859178.5908677
3001493.7567077713858945.7927769
#Sta/Elev= 30
       0  131.53      20  129.11      35  127.64      60  126.31      75  124.94
     105  123.65     125  123.59     130  123.37  139.91  121.95  172.39  110.94
  175.46   110.9  178.32  111.02  209.29  121.37   219.2  122.85  224.15  123.04
  231.13   122.3  242.48   128.5  249.39  128.45     250  128.03  273.74  128.49
  274.31  128.97  290.01  129.21   305.6  128.98  306.19   128.6  329.89  127.94
  330.52   128.6  337.68  128.46  348.53  124.48  357.95  125.08   362.9  123.78
#Mann= 3 ,-1 , 0
       0     .07       0     125     .04       0  224.15     .07       0
#XS Ineff= 2 ,-1
  134.96  166.28  121.36  190.61   219.2  120.88
Permanent Ineff=
       F       F
Bank Sta=125,224.15
XS Rating Curve= 0 ,0
Exp/Cntr=0.5,0.3

Type RM Length L Ch R = 1 ,114.7056,,,
Node Name=A
XS GIS Cut Line= 3
3001535.3041968613859185.73586653001538.5089148613859081.5966391
3001544.1818037813858948.7045164
#Sta/Elev= 29
       0  122.03    4.96  121.92    9.92  121.38   14.88  120.59   30.82  117.02
   48.43  110.07   54.81  109.92   84.34  120.09    89.3  121.29   94.27  122.28
   99.23  122.85  104.15  123.05  106.45  122.72  111.13   122.3  122.48   128.5
  129.39  128.45     130  128.03  153.74  128.49  154.31  128.97  170.01  129.21
   185.6  128.98  186.19   128.6  209.89  127.94  210.52   128.6  215.07  128.63
  217.68  128.46  223.11  126.35  228.53  124.48   237.2  124.44
#Mann= 3 ,-1 , 0
       0     .07       0    4.96     .04       0   99.23     .07       0
Bank Sta=4.96,99.23
XS Rating Curve= 0 ,0
Exp/Cntr=0.3,0.1

Chan Stop Cuts=-1
Use User Specified Reach Order=0
Composite Channel Slope=5